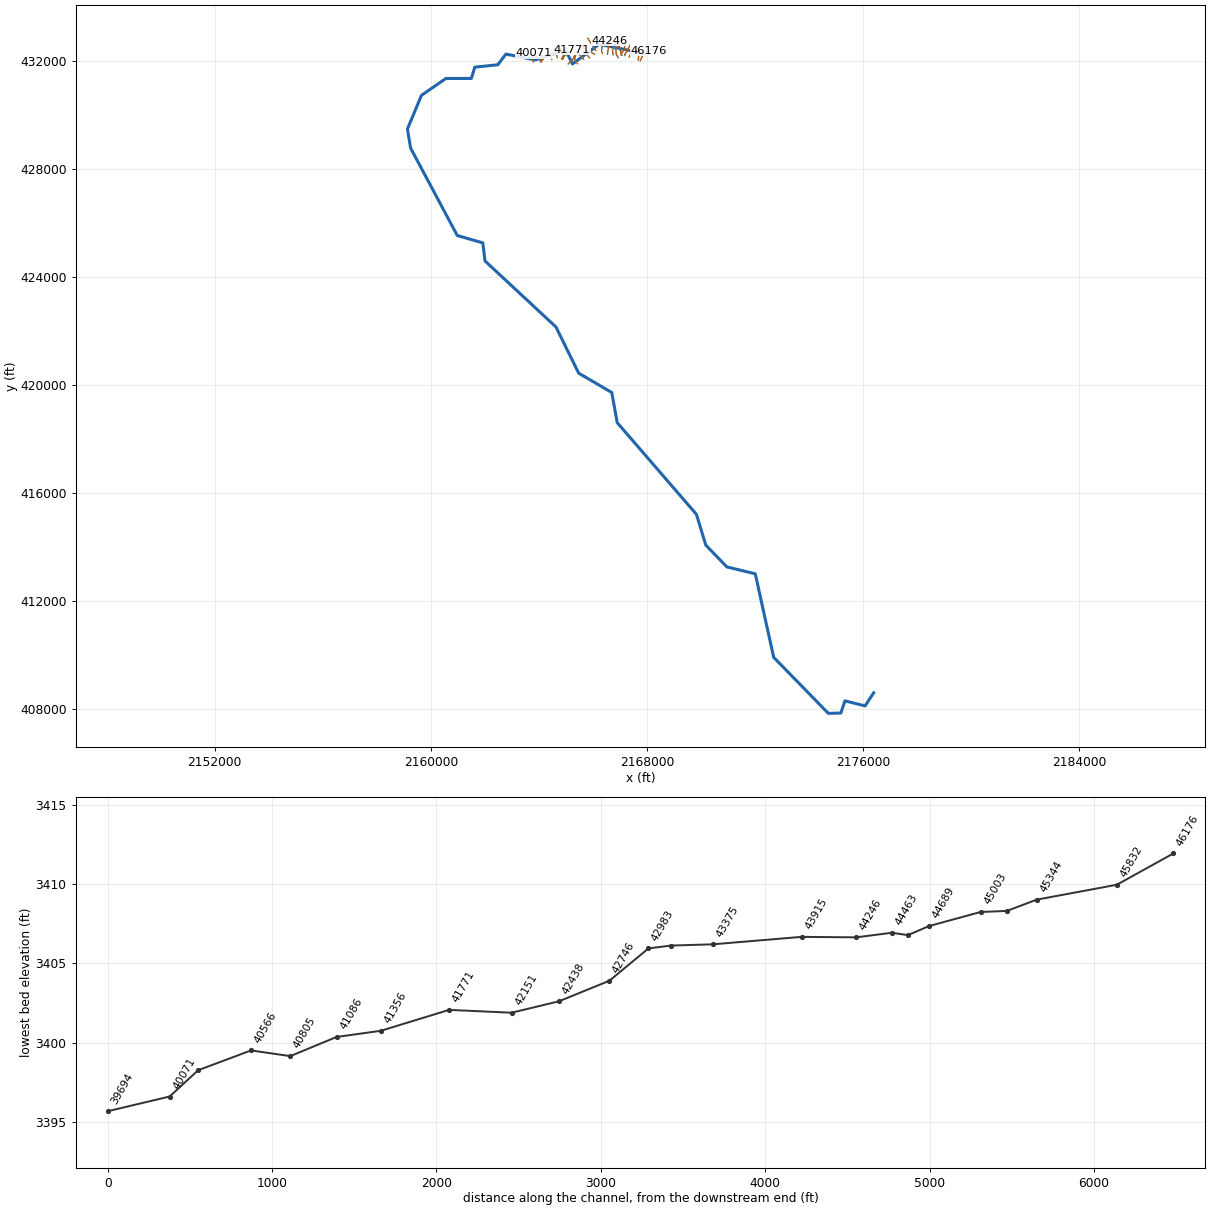
--- HLLSCK.prj (project) ---

Proj Title=HLLSCK
Current Plan=p01
Default Exp/Contr=0.3,0.1
English Units
Geom File=g01
Flow File=f01
Plan File=p01
Background Map Layer=Inundation Boundary (01pct Value_0)
Y Axis Title=Elevation
X Axis Title(PF)=Main Channel Distance
X Axis Title(XS)=Station
BEGIN DESCRIPTION:
----------MODEL BY WOOD PLC 2021----------
Stream Name: Hills Creek
Flood Zone: Enhanced Approximate
Pocahontas County, WV
HEC-RAS Version: RAS 6.1
Vertical Datum: NAVD88
Projection: NAD 1983 StatePlane West Virginia S FIPS 4702 (US Feet)
Terrain: 1-meter LIDAR (FEMA Region III 3DEP collected 2016-2018)
Land Use: 2019 NLCD
Hydrologic Method:
WV SIR2010-5033 regression equations
END DESCRIPTION:
DSS File=dss
DSS Export Rating Curves= 0
DSS Export Rating Curve Sorted= 0
DSS Export Volume Flow Curves= 0
DXF OffsetX= 0
DXF OffsetY= 0
DXF ScaleX= 1
DXF ScaleY= 10

--- HLLSCK.p01 (plan) ---

Plan Title=Floodplain
Program Version=6.10
Short Identifier=Floodplain
Geom File=g01
Flow File=f01
Subcritical Flow
K Sum by GR= 0
Std Step Tol= 0.01
Critical Tol= 0.01
Num of Std Step Trials= 20
Max Error Tol= 0.3
Flow Tol Ratio= 0.001
Split Flow NTrial= 30
Split Flow Tol= 0.02
Split Flow Ratio= 0.02
Log Output Level= 0
Friction Slope Method= 1
Unsteady Friction Slope Method= 2
Unsteady Bridges Friction Slope Method= 1
Parabolic Critical Depth
Global Vel Dist= 0 , 0 , 0
Global Log Level= 0
CheckData=True
Encroach Param=-1 ,0,0, 0
Computation Interval=1MIN
Output Interval=1HOUR
Instantaneous Interval=1HOUR
Mapping Interval=1HOUR
Computation Time Step Use Courant=        0
Computation Time Step Use Time Series=    0
Computation Time Step Count To Double=0
Computation Time Step Max Doubling=0
Computation Time Step Max Halving=0
Computation Time Step Residence Courant=0
Run HTab= 0
Run UNet= 0
Run Sediment= 0
Run PostProcess= 0
Run WQNet= 0
Run RASMapper= 0
UNET Theta= 1
UNET Theta Warmup= 1
UNET ZTol= 0.02
UNET ZSATol= 0.02
UNET MxIter= 20
UNET Max Iter WO Improvement= 0
UNET MaxInSteps= 0
UNET DtIC= 0
UNET DtMin= 0
UNET MaxCRTS= 20
UNET WFStab= 2
UNET SFStab= 1
UNET WFX= 1
UNET SFX= 1
UNET Gravity=32.174
UNET 1D Methodology=Finite Difference
UNET DSS MLevel= 4
UNET Pardiso=0
UNET DZMax Abort= 100
UNET Use Existing IB Tables=-1
UNET Froude Reduction=False
UNET Froude Limit= 0.8
UNET Froude Power= 4
UNET D1 Cores= 0
UNET WindReference=Eulerian
UNET WindDragFormulation=Hsu (1988)
UNET D2 Coriolis=0
UNET D2 Cores= 0
UNET D2 Theta= 1
UNET D2 Theta Warmup= 1
UNET D2 Z Tol= 0.01
UNET D2 Volume Tol= 0.01
UNET D2 Max Iterations= 20
UNET D2 Equation= 0
UNET D2 RampUpFraction=0.1
UNET D2 TimeSlices= 1
UNET D2 Turbulence Formulation=None
UNET D2 Eddy Viscosity=0.3
UNET D2 Transverse Eddy Viscosity=0.1
UNET D2 Smagorinsky Mixing=0.05
UNET D2 BCVolumeCheck=0
UNET D2 Cores=0
UNET D2 SolverType=PARDISO (Direct)
UNET D2 Minimum Iterations= 2147483647
UNET D2 Maximum Iterations= 2147483647
UNET D2 Restart Number= 10
UNET D2 Relaxation Coeff=1.3
UNET D2 SOR Precondition Iterations= 10
UNET D2 ILUT Maximum Fill= 8
UNET D2 ILUT Tolerance=1E-08
UNET D1D2 MaxIter= 0
UNET D1D2 ZTol=0.01
UNET D1D2 QTol=0.1
UNET D1D2 MinQTol=1
DSS File=dss
Write IC File= 0
Write IC File at Fixed DateTime=0
Write IC File at Sim End=0
Echo Input=False
Echo Parameters=False
Echo Output=False
Write Detailed= 0
HDF Write Warmup=0
HDF Write Time Slices=0
HDF Flush=0
HDF Compression= 1
HDF Chunk Size= 1
HDF Spatial Parts= 1
HDF Use Max Rows=0
HDF Fixed Rows= 1
Calibration Method= 0
Calibration Iterations= 20
Calibration Max Change=0.05
Calibration Tolerance=0.2
Calibration Maximum=1.5
Calibration Minimum=0.5
Calibration Optimization Method= 1
WQ AD Non Conservative
WQ ULTIMATE=-1
WQ Max Comp Step=1HOUR
WQ Output Interval=15MIN
WQ Output Selected Increments= 0
WQ Output face flow=0
WQ Output face velocity=0
WQ Output face area=0
WQ Output face dispersion=0
WQ Output cell volume=0
WQ Output cell surface area=0
WQ Output cell continuity=0
WQ Output cumulative cell continuity=0
WQ Output face conc=0
WQ Output face dconc_dx=0
WQ Output face courant=0
WQ Output face peclet=0
WQ Output face adv mass=0
WQ Output face disp mass=0
WQ Output cell mass=0
WQ Output cell source sink temp=0
WQ Output nsm pathways=0
WQ Output nsm derived pathways=0
WQ Create Restart=0
WQ Fixed Restart=0
WQ System Summary=0
WQ Write To DSS=0
Sorting and Armoring Iterations= 10
XS Update Threshold= 0.02
Bed Roughness Predictor= 0
Hydraulics Update Threshold= 0.02
Energy Slope Method= 1
Volume Change Method= 1
Sediment Retention Method= 0
Sediment TS Multiplier= 1
Warm Up Method= 0
XS Weighting Method= 0
Number of US Weighted Cross Sections= 1
Number of DS Weighted Cross Sections= 1
Upstream XS Weight=0
Main XS Weight=1
Downstream XS Weight=0
Number of DS XS's Weighted with US Boundary= 1
Upstream Boundary Weight= 1
Weight of XSs Associated with US Boundary= 0
Number of US XS's Weighted with DS Boundary= 1
Downstream Boundary Weight= 0.5
Weight of XSs Associated with DS Boundary= 0.5
Percentile Method= 0
Sediment Output Level= 3
Mass or Volume Output= 0
Output Increment Type= 1
Profile and TS Output Increment= 1
Transport Output Increment 1
XS Output Flag= 0
XS Output Increment= 10
Read HDF5 Sediment Hotstart= 0
Sediment Hotstart Type= 0
Write Gradation File= 0
Read Gradation Hotstart= 0
Write HDF5 File= 1
Write Binary Output= 1
Write DSS Sediment File= 0
DSS Sediment Output Type= 1
SV Curve= 0
Specific Gage Flag= 0
Subcell Erosion Methods= 0
Subcell Deposition Methods= 0
Advection Scheme= 1
Matrix Solver= 0
Implicit Weighting Factor= 1
Maximum Outer Loop Convergence Iterations= 5
Convergence Maximum Absolute= 0.001
Convergence RMSE= 0.0001
Grain Fractions Max Abs Error= 0.001
Max Subgrid Regions= 1
Max Subgrid Length Scale= 3.402823E+38
Initial Layer Thickness= 3.402823E+38
Min Layer Thickness= 3.402823E+38
Max Layer Thickness= 3.402823E+38
Number of Layers= 5

--- HLLSCK.f01 (steady flow) ---

Flow Title=Flow
Program Version=6.10
Number of Profiles= 6
Profile Names=01pct,10pct,04pct,02pct,0_2pct,01plus
River Rch & RM=HLLSCK,Main            ,46176
     556     294     391     471     778     823
River Rch & RM=HLLSCK,Main            ,43915
     628     333     442     532     875     928
River Rch & RM=HLLSCK,Main            ,41771
     813     436     575     691    1130    1200
River Rch & RM=HLLSCK,Main            ,38853
     923     497     655     785    1280    1360
River Rch & RM=HLLSCK,Main            ,34134
    1030     555     730     873    1420    1520
River Rch & RM=HLLSCK,Main            ,30452
    1150     626     821     982    1590    1700
River Rch & RM=HLLSCK,Main            ,28436
    1440     790    1030    1230    1980    2130
River Rch & RM=HLLSCK,Main            ,23396
    1640     905    1180    1400    2250    2430
River Rch & RM=HLLSCK,Main            ,19912
    2050    1140    1470    1750    2790    3030
River Rch & RM=HLLSCK,Main            ,13996
    2330    1300    1680    1990    3170    3440
River Rch & RM=HLLSCK,Main            ,1189
    3220    1820    2340    2770    4360    4770
Boundary for River Rch & Prof#=HLLSCK,Main            , 1
Up Type= 0
Dn Type= 3
Dn Slope=0.00247
Boundary for River Rch & Prof#=HLLSCK,Main            , 2
Up Type= 0
Dn Type= 3
Dn Slope=0.00247
Boundary for River Rch & Prof#=HLLSCK,Main            , 3
Up Type= 0
Dn Type= 3
Dn Slope=0.00247
Boundary for River Rch & Prof#=HLLSCK,Main            , 4
Up Type= 0
Dn Type= 3
Dn Slope=0.00247
Boundary for River Rch & Prof#=HLLSCK,Main            , 5
Up Type= 0
Dn Type= 3
Dn Slope=0.00247
Boundary for River Rch & Prof#=HLLSCK,Main            , 6
Up Type= 0
Dn Type= 3
Dn Slope=0.00247
DSS Import GetInterval= 0
DSS Import GetPeak= 0
DSS Import FillOption= 0

--- HLLSCK.g01 (geometry) ---

Geom Title=Geometry
Program Version=6.10

River Reach=HLLSCK          ,Main
Reach XY= 30
 2167914.7772703432290.0154035542166224.48865613432633.145950899
2165239.16976064431903.6323180652164981.18668081432426.521692231
2163862.25256696432053.0221111482162775.98111747432269.557767317
2162476.38821273431875.2340808962161622.67994639431783.687347978
2161498.94528572431366.9070135652160556.39467739 431367.19900772
2159649.54544123430739.8042651412159131.01662263429493.165354222
2159248.23128322 428789.361971812160975.62021689425550.714577734
2161923.21740305425276.011386976 2162002.2831898424606.847042888
2164628.53482705422161.9674182242165469.60729189 420451.08107622
2166693.59795414419734.5421549832166896.74223289418616.556530058
2169827.12416738415223.6745363182170174.72681864414080.699460059
2170954.56679438 413275.664652812172005.17558555413019.933536977
2172686.52888164 409926.478765892174709.73710555407850.935344815
2175171.19517213407863.2617637222175323.13975014408315.032513723
2176068.93648689408126.6487041412176386.33414605408610.865583479

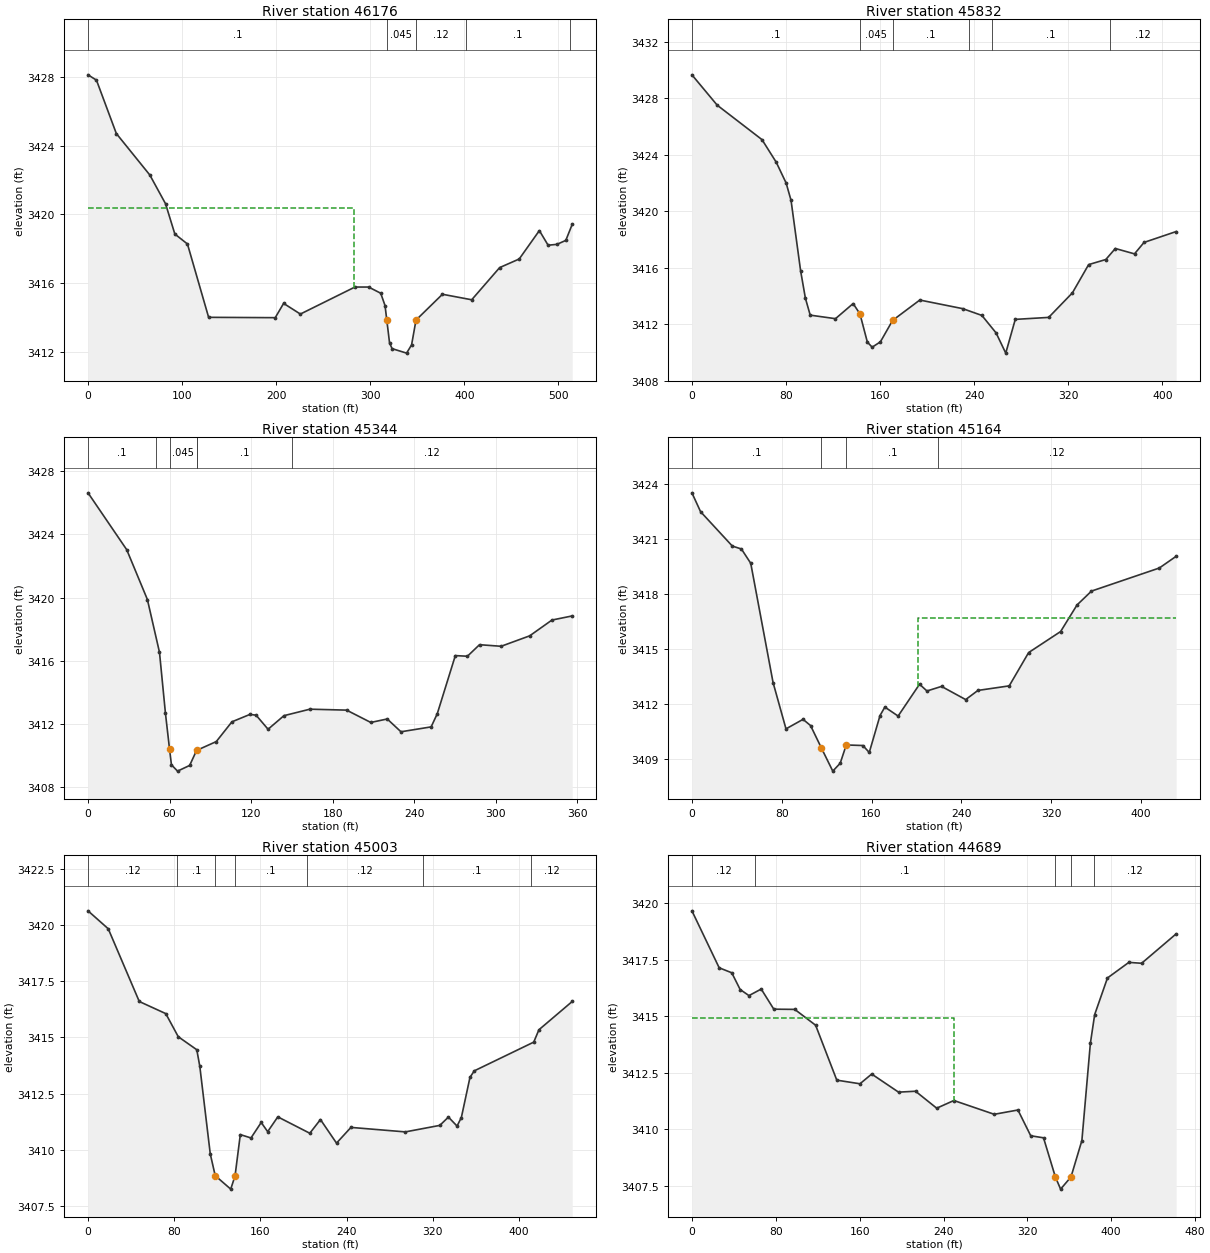
Type RM Length L Ch R = 1 ,46176   ,309.8,344.5,357.7
XS GIS Cut Line= 3
2167744.25158609432018.0754158212167867.13967414432271.690285046
2168066.05972309432392.680200302
#Sta/Elev= 30
       0 3428.11       9  3427.8    30.1  3424.7    65.7 3422.29    82.4 3420.62
    92.3 3418.86   105.7 3418.28   128.2 3414.02     199    3414   207.9 3414.83
   225.7 3414.21   283.7 3415.78   298.2 3415.78   311.1 3415.42   315.7  3414.7
   317.63413.839   320.5 3412.53   323.2  3412.2   338.6 3411.94   343.9 3412.42
   348.6 3413.86   376.7 3415.36   407.8 3415.04   437.5 3416.91   458.3 3417.41
   479.7 3419.06     489 3418.21   498.4 3418.26   507.8 3418.49   514.6 3419.42
#Mann= 5 ,-1,0
       0      .1       0   317.6    .045       0   348.6     .12       0
  401.82      .1       0  511.82     .12       0
#XS Ineff= 2 , 0
          282.32 3420.35
Permanent Ineff=
       F       F
Bank Sta=317.6,348.6
XS Rating Curve= 0 ,0
Exp/Cntr(USF)=0,0
Exp/Cntr=0.3,0.1

Type RM Length L Ch R = 1 ,45832   ,492.8,487.5,474.8
XS GIS Cut Line= 3
2167666.14471081432052.6580619672167691.43541659432134.278066994
2167637.40527242 432456.15977696
#Sta/Elev= 30
       0 3429.67    21.5 3427.52    59.6 3425.08    71.7 3423.48    80.1 3422.01
    84.3 3420.78    92.4 3415.81    96.5 3413.85   100.6 3412.65   122.1  3412.4
   137.1 3413.47   142.9 3412.74   149.2 3410.74   153.3 3410.38   160.3 3410.76
   170.7 3412.28   193.8 3413.72   230.3 3413.11   246.6 3412.63   258.7 3411.39
   266.9 3409.96     275 3412.35   303.4 3412.49   323.6 3414.23   337.4 3416.23
     352 3416.59   360.1 3417.37   376.4 3416.99   384.5  3417.8   411.8 3418.57
#Mann= 6 ,-1,0
       0      .1       0   142.9    .045       0   170.7      .1       0
  235.45     .12       0  255.45      .1       0  355.45     .12       0
Bank Sta=142.9,170.7
XS Rating Curve= 0 ,0
Exp/Cntr(USF)=0,0
Exp/Cntr=0.3,0.1

Type RM Length L Ch R = 1 ,45344   ,182.9,180.3,177.6
XS GIS Cut Line= 2
2167337.36553563432161.8679278482167492.55850293432482.600060278
#Sta/Elev= 30
       0 3426.63    28.5 3423.03    43.7 3419.88    52.6 3416.54      57 3412.67
      603410.415    61.4 3409.42    65.9 3409.02    74.8 3409.38    79.9 3410.33
    94.4 3410.89   105.9 3412.14   119.2 3412.61   123.7 3412.56   132.5 3411.67
   144.2 3412.53   163.3 3412.94   190.3 3412.88   208.1  3412.1   220.2 3412.32
   230.3 3411.51   252.5 3411.82     257 3412.65   270.3 3416.33   279.2 3416.29
   288.1 3417.02     304 3416.92     325 3417.58   341.4 3418.58   356.3 3418.84
#Mann= 6 ,-1,0
       0      .1       0      50     .12       0      60    .045       0
    79.9     .12       0      80      .1       0     150     .12       0
Bank Sta=60,79.9
XS Rating Curve= 0 ,0
Exp/Cntr(USF)=0,0
Exp/Cntr=0.3,0.1

Type RM Length L Ch R = 1 ,45164   ,160.5,161,155.4
XS GIS Cut Line= 4
2167184.14230406432213.5669276982167176.03888304432265.378289042
2167276.90708144432398.495630201 2167356.1338854432595.045830173
#Sta/Elev= 30
       0 3423.52     7.7 3422.49      36 3420.61    44.1 3420.45    52.4 3419.67
    72.3 3413.15    83.8 3410.62      99 3411.14   105.7  3410.8   115.43409.569
   125.5 3408.31   132.1 3408.74   137.5 3409.74   152.3 3409.71     158 3409.33
   167.6 3411.35   171.9 3411.81   183.7 3411.32   202.8 3413.06   209.4 3412.69
   222.4 3412.94   243.9 3412.22   254.8 3412.72   282.7 3412.97     300 3414.79
   328.5 3415.94   343.1 3417.39     356 3418.15   416.4 3419.41   431.4 3420.05
#Mann= 4 ,-1,0
       0      .1       0   115.4    .045       0   137.5      .1       0
  219.46     .12       0
#XS Ineff= 2 , 0
                          201.42          3416.7
Permanent Ineff=
       F       F
Bank Sta=115.4,137.5
XS Rating Curve= 0 ,0
Exp/Cntr(USF)=0,0
Exp/Cntr=0.3,0.1

Type RM Length L Ch R = 1 ,45003   ,285.6,313.8,319.4
XS GIS Cut Line= 4
 2167068.3643923432222.795537234 2167052.2703068432294.069344441
2167169.52721543432453.860621888 2167171.8263705432632.045139905
#Sta/Elev= 30
       0 3420.64    18.8 3419.84    47.6  3416.6    72.2 3416.06    83.8 3415.03
     101 3414.45   103.8 3413.71   113.5 3409.81   118.1 3408.84   132.5 3408.24
   136.5 3408.83   141.4 3410.67   151.3 3410.52   160.8 3411.21   166.8  3410.8
   176.2 3411.46   205.9 3410.73   215.8 3411.34   230.7 3410.29   244.1 3410.99
   294.6 3410.79   326.6 3411.08   334.6 3411.45   342.6 3411.05   346.6 3411.43
   354.6 3413.22   358.6 3413.51   413.8 3414.79   418.6 3415.34   449.5  3416.6
#Mann= 7 ,-1,0
       0     .12       0   83.07      .1       0   118.1    .045       0
   136.5      .1       0  203.07     .12       0  311.27      .1       0
  411.27     .12       0
Bank Sta=118.1,136.5
XS Rating Curve= 0 ,0
Exp/Cntr(USF)=0,0
Exp/Cntr=0.3,0.1

Type RM Length L Ch R = 1 ,44689   ,129.9,128,126.5
XS GIS Cut Line= 4
2167040.48717949432239.2950259612167030.26436608432379.858710415
2166985.53955739432423.3056674282166938.25904534432677.598151122
#Sta/Elev= 30
       0 3419.66      26 3417.14      38 3416.92      46 3416.18    54.4 3415.91
    66.1  3416.2    78.1 3415.31    98.1  3415.3     118  3414.6   138.2 3412.17
   160.3 3412.01   171.5 3412.44   197.1 3411.64   213.3 3411.68   233.5 3410.93
   249.9 3411.27   288.4 3410.66     311 3410.85   323.2 3409.71   335.4 3409.62
   346.7 3407.89   351.7 3407.35   361.63407.888     372  3409.5   380.1  3413.8
   384.2 3415.07   396.4 3416.69   416.8 3417.38     429 3417.34   461.9 3418.64
#Mann= 5 ,-1,0
       0     .12       0      60      .1       0   346.7    .045       0
   361.6      .1       0  383.29     .12       0
#XS Ineff= 2 , 0
          249.76 3414.93
Permanent Ineff=
       F       F
Bank Sta=346.7,361.6
XS Rating Curve= 0 ,0
Exp/Cntr(USF)=0,0
Exp/Cntr=0.3,0.1

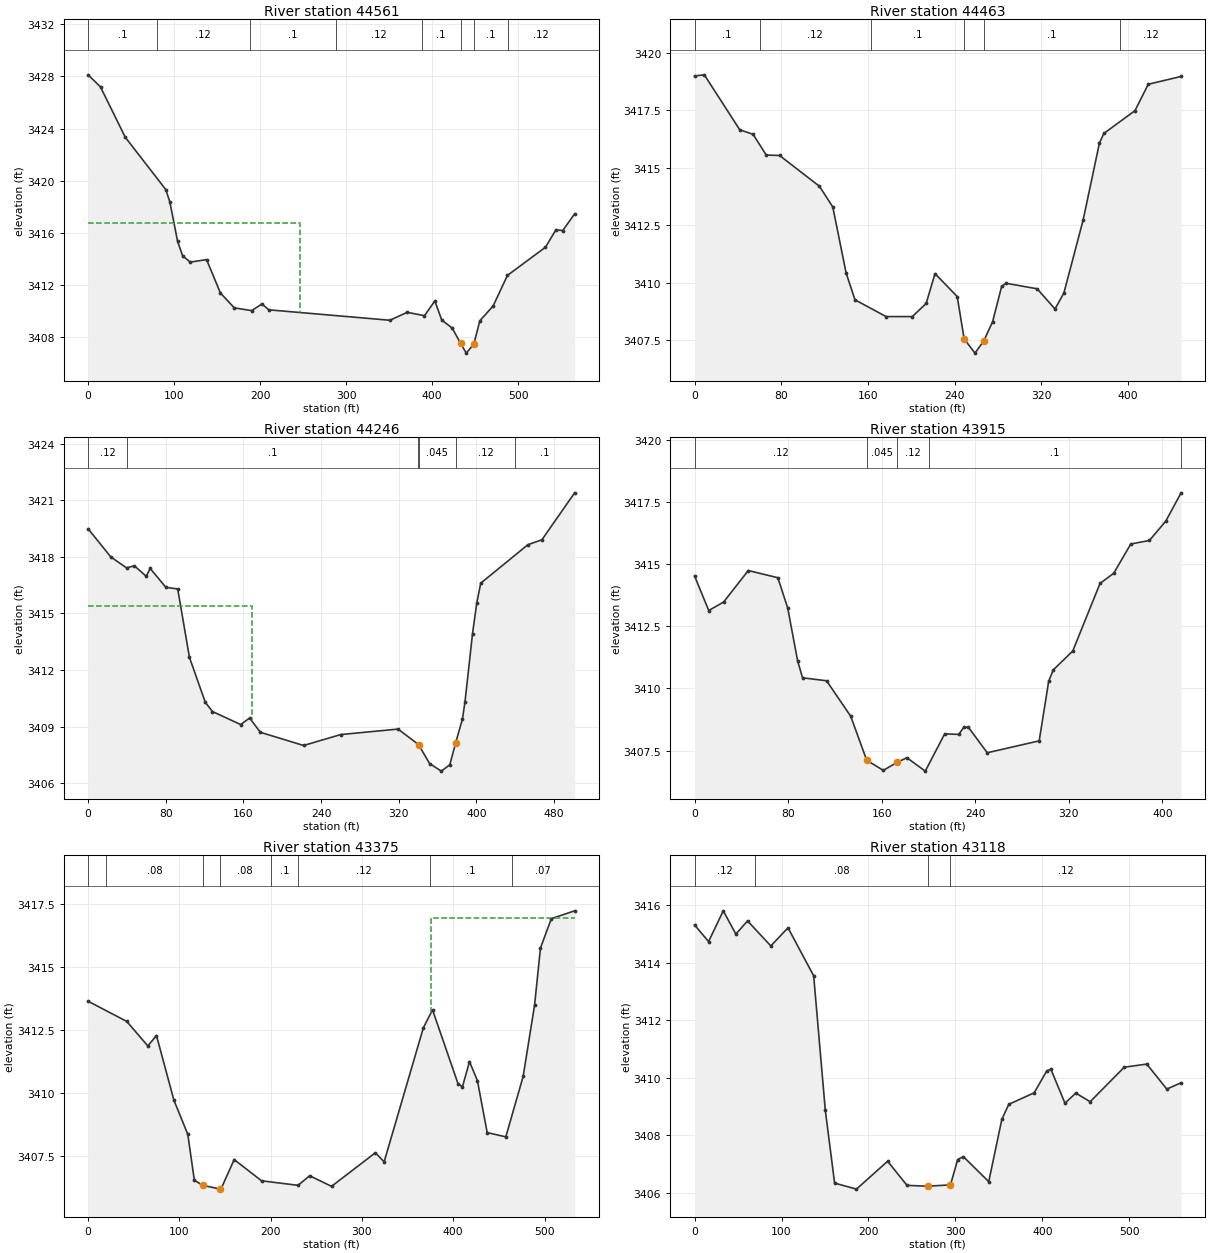
Type RM Length L Ch R = 1 ,44561   ,104,98.1,87.4
XS GIS Cut Line= 3
2166935.70334199432137.0668918132166861.58794473432253.351394406
 2166819.4188394432678.876002799
#Sta/Elev= 30
       0 3428.12    14.4 3427.19    43.2 3423.33    90.3 3419.32      95 3418.37
     104 3415.35   109.8 3414.25   118.7 3413.76   137.7 3413.95   153.8 3411.39
   169.9 3410.25   190.2 3410.04     202 3410.55   210.1  3410.1   350.8  3409.3
   370.9 3409.91     391 3409.65     403 3410.78   411.1 3409.31   423.1 3408.71
     4333407.533   439.5 3406.78   448.4 3407.48   455.3 3409.26   470.8  3410.4
   487.4 3412.74   531.6  3414.9   543.7 3416.23   551.7 3416.18   565.5 3417.46
#Mann= 8 ,-1,0
       0      .1       0      80     .12       0   187.9      .1       0
   287.9     .12       0   387.9      .1       0     433    .045       0
   448.4      .1       0   487.9     .12       0
#XS Ineff= 2 , 0
          246.38 3416.77
Permanent Ineff=
       F       F
Bank Sta=433,448.4
XS Rating Curve= 0 ,0
Exp/Cntr(USF)=0,0
Exp/Cntr=0.3,0.1

Type RM Length L Ch R = 1 ,44463   ,215,216.6,220.7
XS GIS Cut Line= 3
2166747.85914549432244.4064326682166722.30211195432364.524490293
2166795.13965754432682.709557829
#Sta/Elev= 30
       0 3418.99       9 3419.04    41.7 3416.65      54 3416.45    66.2 3415.55
    78.5 3415.53   115.3 3414.19   127.6 3413.29   139.9 3410.42   148.1 3409.25
   176.8 3408.52     201 3408.52   213.8 3409.09     222 3410.39   242.5 3409.39
   248.9 3407.55   258.9 3406.93   267.1 3407.47   275.2  3408.3   283.5 3409.83
   287.6 3409.97   316.3 3409.73   332.8 3408.85     341 3409.55   358.7 3412.71
   373.8 3416.07   377.9 3416.49   406.6 3417.48   418.9 3418.63   449.2 3418.97
#Mann= 6 ,-1,0
       0      .1       0      60     .12       0  162.81      .1       0
   248.9    .045       0   267.1      .1       0  392.81     .12       0
Bank Sta=248.9,267.1
XS Rating Curve= 0 ,0
Exp/Cntr(USF)=0,0
Exp/Cntr=0.3,0.1

Type RM Length L Ch R = 1 ,44246   ,327.3,331.7,336.6
XS GIS Cut Line= 2
 2166531.9022121432266.1299111752166613.68471942432760.658510117
#Sta/Elev= 30
       0 3419.49    23.4    3418    39.6 3417.42    47.7 3417.53    59.9 3416.97
    63.9 3417.39    80.1 3416.39    92.3  3416.3   104.4 3412.67   120.7 3410.29
   128.1  3409.8   157.2 3409.11   166.4 3409.46   177.4  3408.7     222    3408
   260.3 3408.58   319.3 3408.87   340.4 3408.05   351.8 3407.04   363.9 3406.64
   372.6 3406.98   378.6 3408.13   385.6  3409.4   388.3 3410.33     396 3413.93
   400.4 3415.56   404.5 3416.61   453.1 3418.65   467.5 3418.91   501.2  3421.4
#Mann= 6 ,-1,0
       0     .12       0      40      .1       0     340     .12       0
   340.4    .045       0   378.6     .12       0     440      .1       0
#XS Ineff= 2 , 0
           168.7 3415.39
Permanent Ineff=
       F       F
Bank Sta=340.4,378.6
XS Rating Curve= 0 ,0
Exp/Cntr(USF)=0,0
Exp/Cntr=0.3,0.1

Type RM Length L Ch R = 1 ,43915   ,502.6,539.7,543.3
XS GIS Cut Line= 4
 2166347.0253353432301.6583816842166315.13944794 432397.01822608
2166345.33586728432611.1498639252166395.72348037432696.426371635
#Sta/Elev= 30
       0 3414.53    12.1 3413.14    24.8 3413.48    45.9 3414.75    71.2 3414.46
    79.6 3413.24    88.1 3411.11    92.3 3410.43   112.8 3410.31   133.5 3408.88
   147.13407.111   161.3  3406.7   173.23407.026   181.5 3407.21   197.2 3406.67
   213.8 3408.17   225.9 3408.15     230 3408.43     234 3408.44   250.2 3407.41
   294.6 3407.89   302.7 3410.29   306.7 3410.75   323.3 3411.51   346.6 3414.23
   358.3 3414.64   372.9 3415.82   388.8 3415.96   402.8 3416.74   415.9 3417.88
#Mann= 5 ,-1,0
       0     .12       0   147.1    .045       0   173.2     .12       0
  200.55      .1       0  415.85     .12       0
Bank Sta=147.1,173.2
XS Rating Curve= 0 ,0
Exp/Cntr(USF)=0,0
Exp/Cntr=0.3,0.1

Type RM Length L Ch R = 1 ,43375   ,243.7,256.9,256.1
XS GIS Cut Line= 3
2166100.42010733432406.7279429292165904.99192628432702.169369577
2165808.43311131432852.668717699
#Sta/Elev= 30
       0 3413.64    42.4 3412.84    65.4 3411.87    74.9 3412.28    94.1 3409.71
   109.2 3408.37   116.4 3406.55   125.43406.354   144.23406.206   145.5  3406.2
     160 3407.37     190 3406.53     230 3406.35   242.7 3406.73   266.7 3406.31
   314.7 3407.64   324.3 3407.28   367.3 3412.59   377.3  3413.3   405.3 3410.37
   410.1 3410.25   417.8 3411.25   426.5  3410.5   437.2 3408.44   457.6 3408.27
   476.6 3410.66   489.1 3413.48   495.6 3415.75   507.5 3416.91     533 3417.22
#Mann= 8 ,-1,0
       0     .12       0      20     .08       0   125.4    .045       0
   144.2     .08       0     200      .1       0     230     .12       0
  374.23      .1       0  464.23     .07       0
#XS Ineff= 2 , 0
                          375.65         3416.94
Permanent Ineff=
       F       F
Bank Sta=125.4,144.2
XS Rating Curve= 0 ,0
Exp/Cntr(USF)=0,0
Exp/Cntr=0.3,0.1

Type RM Length L Ch R = 1 ,43118   ,139.7,135.3,135.1
XS GIS Cut Line= 4
2166058.57720411432267.3009421642165811.95183048432391.252554819
2165801.72901706432410.4203299722165583.21638032432554.817569456
#Sta/Elev= 30
       0 3415.31    16.1 3414.73      33  3415.8    47.5 3414.99    60.9 3415.45
    87.7 3414.58   107.5 3415.21     137 3413.54   150.4 3408.86   161.1 3406.33
   186.2 3406.12   222.1 3407.09   244.4 3406.25   268.13406.222   294.43406.268
   302.7 3407.15   309.2 3407.25   338.4 3406.38   353.5 3408.55   361.5 3409.07
   390.7 3409.47   405.1 3410.23   409.9 3410.29   426.1 3409.11   438.6 3409.46
   455.1 3409.16   494.3 3410.36   520.2 3410.47   543.3  3409.6   559.7 3409.82
#Mann= 4 ,-1,0
       0     .12       0      70     .08       0   268.1    .045       0
   294.4     .12       0
Bank Sta=268.1,294.4
XS Rating Curve= 0 ,0
Exp/Cntr(USF)=0,0
Exp/Cntr=0.3,0.1

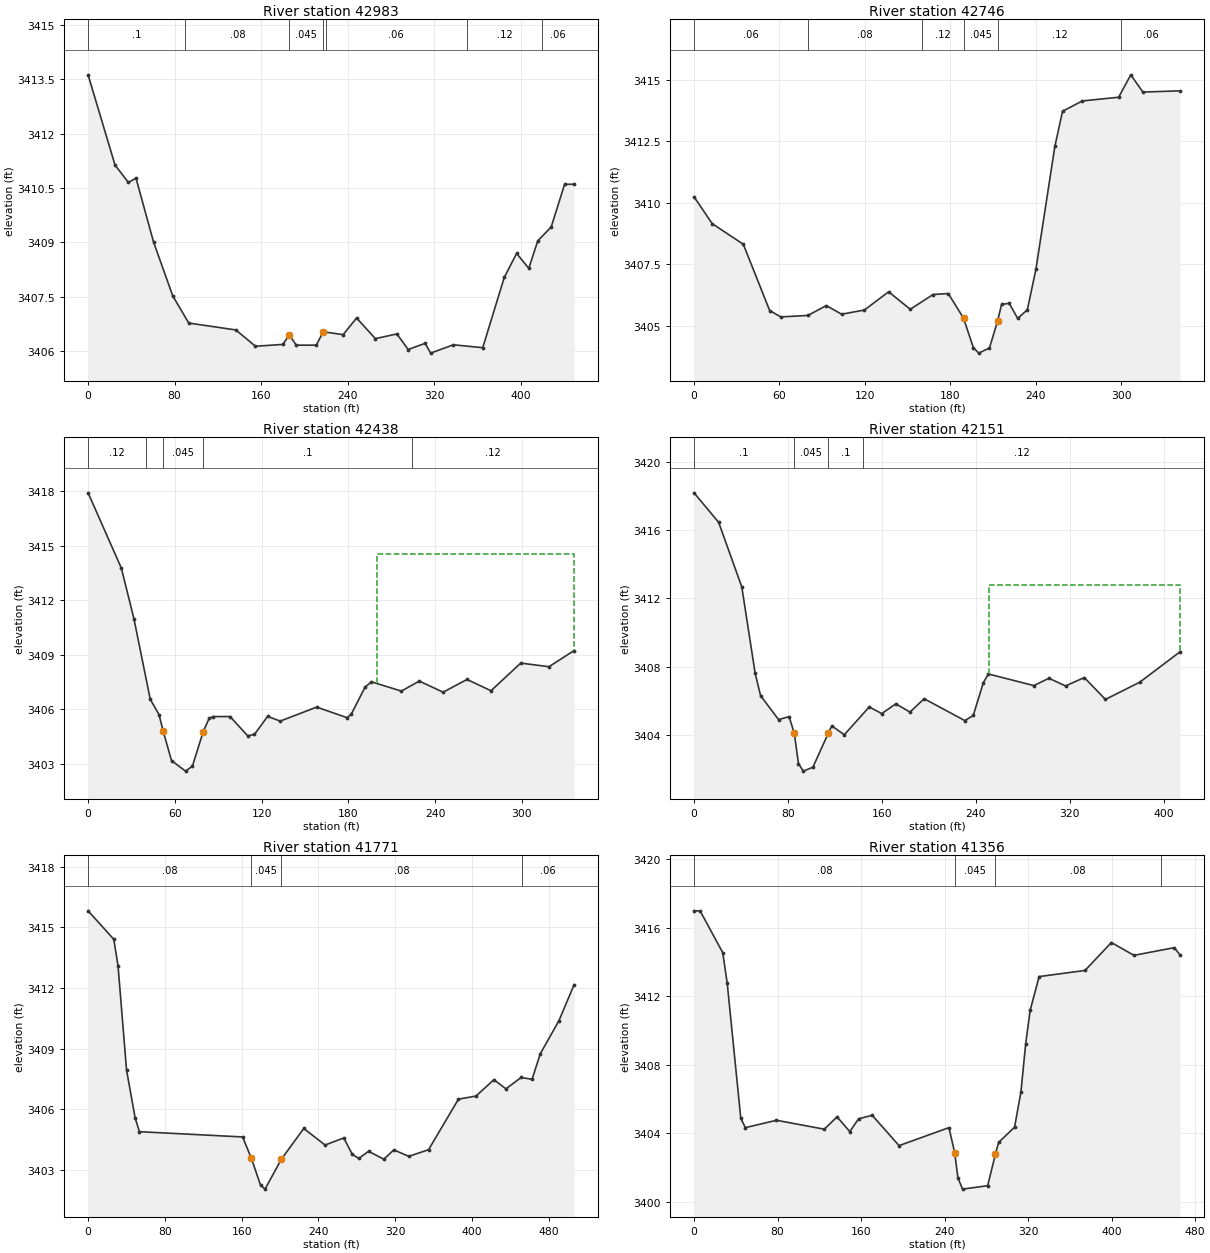
Type RM Length L Ch R = 1 ,42983   ,233.8,237.2,234.2
XS GIS Cut Line= 2
2165868.20544514432130.8293343872165578.51190617432474.553017529
#Sta/Elev= 30
       0 3413.62    24.9 3411.13    37.3 3410.65    44.3 3410.77    60.6    3409
    78.3 3407.52    93.1 3406.77   136.6 3406.58   154.8 3406.13     180 3406.18
   186.2 3406.44   192.5 3406.16   211.1 3406.16   217.4 3406.53   235.9 3406.45
   248.3 3406.91   265.7 3406.34   285.6 3406.47     296 3406.04   311.7 3406.21
   316.8 3405.94   337.9 3406.17     365 3406.09   384.9 3408.03   396.3 3408.69
   407.6 3408.28   415.9 3409.04   428.3 3409.42   440.7  3410.6   449.5  3410.6
#Mann= 7 ,-1,0
       0      .1       0      90     .08       0   186.2    .045       0
   217.4     .08       0     220     .06       0     350     .12       0
     420     .06       0
Bank Sta=186.2,217.4
XS Rating Curve= 0 ,0
Exp/Cntr(USF)=0,0
Exp/Cntr=0.3,0.1

Type RM Length L Ch R = 1 ,42746   ,308.7,307.6,300.7
XS GIS Cut Line= 2
2165651.41788002432079.6433120122165425.05028902432334.889073056
#Sta/Elev= 30
       0 3410.25    12.7 3409.16    34.6 3408.32    53.1 3405.63    60.9 3405.37
    79.9 3405.43    92.9 3405.83   103.6 3405.48   119.6 3405.65   136.6 3406.39
   151.8 3405.68   167.8 3406.28   178.5 3406.32   189.2 3405.32   196.1 3404.12
   199.9  3403.9   207.4 3404.11   213.1  3405.2   215.9 3405.88   221.3 3405.92
   227.2 3405.31     234 3405.66     240  3407.3   253.3 3412.29   258.7 3413.72
   272.6 3414.14   298.1 3414.29   306.6  3415.2   315.1  3414.5   341.2 3414.55
#Mann= 6 ,-1,0
       0     .06       0      80     .08       0     160     .12       0
   189.2    .045       0   213.1     .12       0     300     .06       0
Bank Sta=189.2,213.1
XS Rating Curve= 0 ,0
Exp/Cntr(USF)=0,0
Exp/Cntr=0.3,0.1

Type RM Length L Ch R = 1 ,42438   ,309.1,287.3,252.8
XS GIS Cut Line= 3
2165423.65226522431912.7620250162165317.75727514432074.998580336
2165353.73441921432212.797830251
#Sta/Elev= 30
       0  3417.9      23 3413.76    31.7 3410.98      43 3406.55    49.1  3405.7
    51.9 3404.81    57.7 3403.18    67.4  3402.6    72.2 3402.88    79.5 3404.74
    83.7  3405.5    86.5  3405.6    98.2  3405.6   110.4 3404.54   115.1 3404.62
   124.2 3405.61   132.9 3405.35   158.1 3406.12   179.1 3405.54     182 3405.72
   191.6 3407.22     196 3407.51   216.7    3407   229.1 3407.55   245.6 3406.94
   262.1 3407.64   278.7 3407.02   299.3 3408.54   318.8 3408.34   336.2 3409.23
#Mann= 5 ,-1,0
       0     .12       0      40      .1       0    51.9    .045       0
    79.5      .1       0  223.74     .12       0
#XS Ineff= 2 , 0
                          199.52         3414.51
Permanent Ineff=
       F       F
Bank Sta=51.9,79.5
XS Rating Curve= 0 ,0
Exp/Cntr(USF)=0,0
Exp/Cntr=0.3,0.1

Type RM Length L Ch R = 1 ,42151   ,373.5,380.1,373.9
XS GIS Cut Line= 4
2165083.84577903431900.444669587 2165116.4288529431943.209954044
2165253.60236477432063.7082919642165318.85697251432229.079124451
#Sta/Elev= 30
       0 3418.18      21 3416.45    40.7 3412.67    52.1  3407.6    56.7  3406.3
      72  3404.9      81 3405.07    85.4  3404.1      89 3402.32    93.1 3401.88
   101.3 3402.11   114.5 3404.12   117.4 3404.53     128 3404.01   149.3 3405.64
   159.9 3405.25   171.9 3405.82     184 3405.34   196.1 3406.12   230.7 3404.84
   237.9 3405.14   246.5 3407.06   250.8 3407.57   289.5 3406.89   302.4 3407.32
   316.5 3406.87   332.5 3407.36   350.5 3406.08   379.8 3407.09   414.1 3408.87
#Mann= 4 ,-1,0
       0      .1       0    85.4    .045       0   114.5      .1       0
  143.76     .12       0
#XS Ineff= 2 , 0
                          251.69         3412.81
Permanent Ineff=
       F       F
Bank Sta=85.4,114.5
XS Rating Curve= 0 ,0
Exp/Cntr(USF)=0,0
Exp/Cntr=0.3,0.1

Type RM Length L Ch R = 1 ,41771   ,364.6,415,436.3
XS GIS Cut Line= 3
2164876.35953159432081.1548530412164925.79366478432181.864742624
2165228.33718144432434.808586936
#Sta/Elev= 30
       0 3415.82    26.8 3414.41    31.2  3413.1    40.1 3407.94      49 3405.59
    53.5  3404.9     161 3404.64   170.2 3403.58   179.7 3402.26   184.4 3402.06
   201.4 3403.54   224.8 3405.06   246.9 3404.24   266.5 3404.59   275.3 3403.78
   282.1 3403.58   292.3 3403.93   308.2 3403.54   318.6    3404   334.3 3403.68
   354.8 3404.01     386 3406.51   404.2 3406.66   422.9 3407.47   435.4 3407.02
   451.3 3407.58   462.7 3407.49   471.2 3408.75   490.7 3410.39   506.5 3412.17
#Mann= 4 ,-1,0
       0     .08       0   170.2    .045       0   201.4     .08       0
  452.19     .06       0
Bank Sta=170.2,201.4
XS Rating Curve= 0 ,0
Exp/Cntr(USF)=0,0
Exp/Cntr=0.3,0.1

Type RM Length L Ch R = 1 ,41356   ,267.1,269.5,264.8
XS GIS Cut Line= 3
2164841.99980863432087.8591892292164903.17687634432232.840459285
2164786.30491267432518.051353444
#Sta/Elev= 30
       0 3416.98     5.8 3416.99    27.5 3414.55    31.8 3412.76    44.8 3404.87
    49.2 3404.33      79 3404.76   124.8 3404.24     137 3404.96   149.2  3404.1
   157.7 3404.85   170.7 3405.05   196.4 3403.28   244.2 3404.33   249.7 3402.87
   252.8  3401.4   257.2 3400.74   281.3 3400.94   288.7 3402.78   291.8 3403.47
   307.1 3404.36   313.2 3406.43   317.7 3409.22     322 3411.18   330.6 3413.15
   374.6 3413.51   399.8 3415.14   421.4 3414.39   460.1 3414.84   465.6 3414.41
#Mann= 4 ,-1,0
       0     .08       0   249.7    .045       0   288.7     .08       0
  447.36     .06       0
Bank Sta=249.7,288.7
XS Rating Curve= 0 ,0
Exp/Cntr(USF)=0,0
Exp/Cntr=0.3,0.1

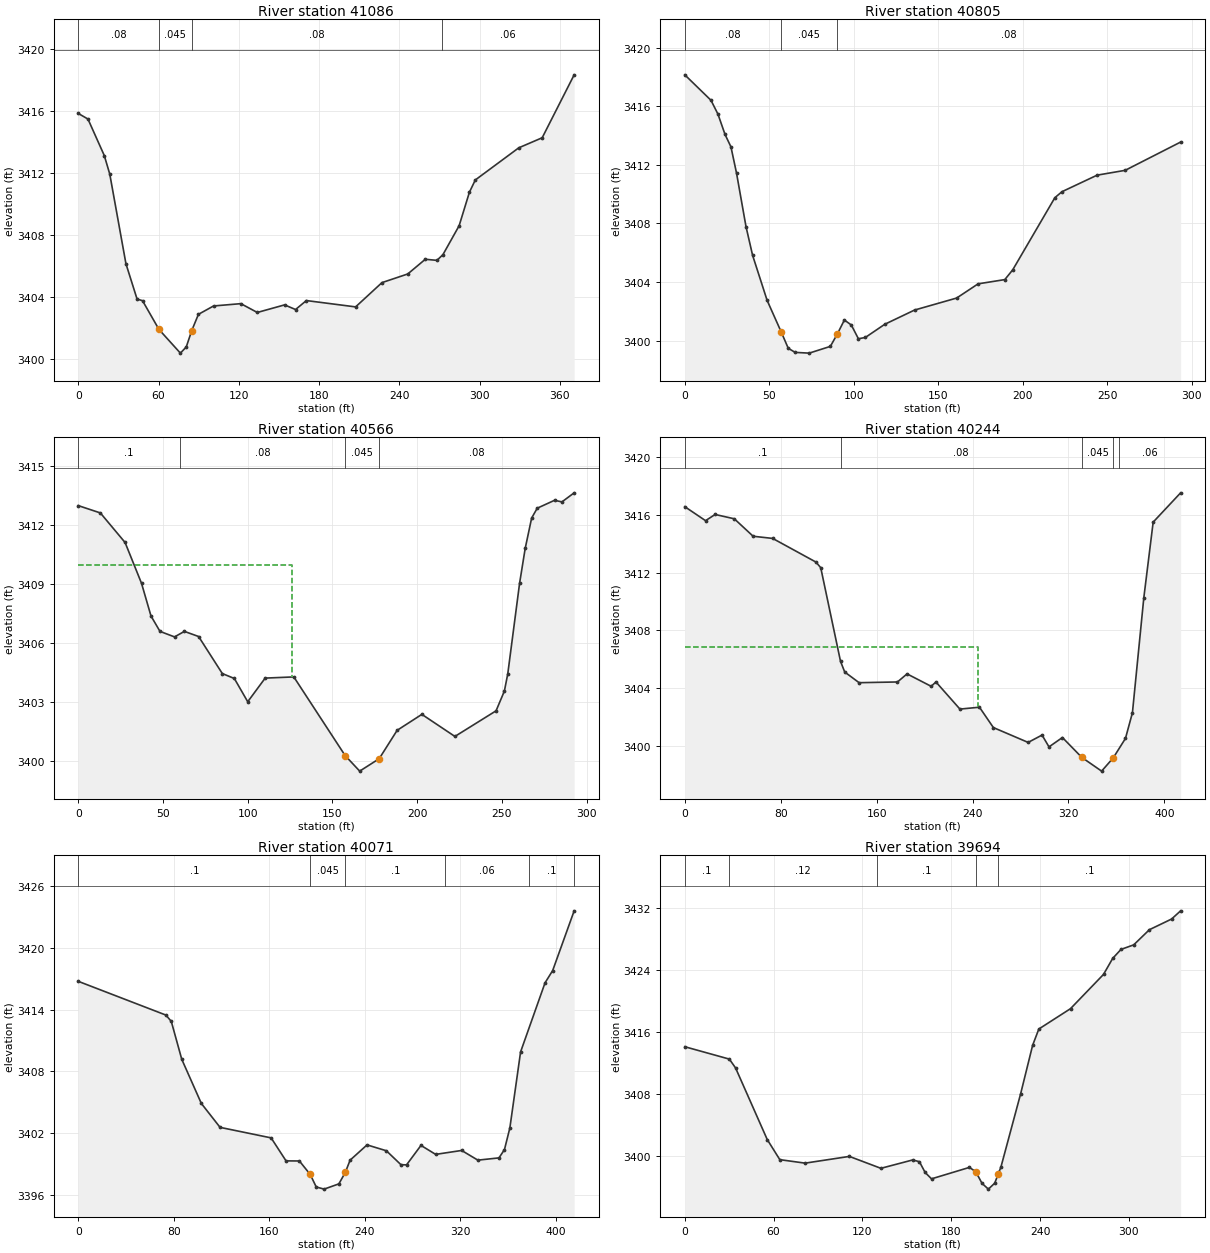
Type RM Length L Ch R = 1 ,41086   ,277.1,281.5,278.7
XS GIS Cut Line= 3
2164675.22944597432138.1417106362164632.48930277 432345.97613245
2164568.64464623432491.077836923
#Sta/Elev= 30
       0 3415.85     7.2 3415.49    19.4 3413.13    23.5 3411.93    35.6 3406.13
    43.9 3403.85      48 3403.74    60.3 3401.88    76.3 3400.35    80.7 3400.75
    84.8 3401.81    89.8 3402.86   101.1  3403.4   121.5 3403.55   133.8 3402.98
   154.2 3403.47   162.4 3403.17   170.5 3403.75   207.3 3403.34     227 3404.91
   246.3 3405.47   259.4 3406.42   268.1 3406.35   272.6 3406.72   284.7 3408.59
   292.4 3410.76   296.8 3411.55   329.3 3413.63   346.8 3414.28   370.7 3418.35
#Mann= 4 ,-1,0
       0     .08       0    60.3    .045       0    84.8     .08       0
  272.18     .06       0
Bank Sta=60.3,84.8
XS Rating Curve= 0 ,0
Exp/Cntr(USF)=0,0
Exp/Cntr=0.3,0.1

Type RM Length L Ch R = 1 ,40805   ,253.9,238.6,219.7
XS GIS Cut Line= 2
2164474.93740236432070.2603067362164396.28655815432352.770210503
#Sta/Elev= 30
       0 3418.14    15.5  3416.4    19.6 3415.46    23.8 3414.07    27.3 3413.22
    30.6 3411.43    36.2 3407.78    40.1 3405.82    48.7 3402.74      573400.593
    61.2 3399.47    65.3 3399.19    73.6 3399.14    86.1  3399.6    90.2 3400.44
    94.4  3401.4    98.5 3401.06   102.7 3400.12   106.8 3400.21   118.3 3401.11
   135.9 3402.08   160.8  3402.9   173.5 3403.87   189.3 3404.16     194 3404.83
   218.9 3409.75   223.1 3410.16   243.9 3411.29   260.5 3411.62   293.3 3413.55
#Mann= 3 ,-1,0
       0     .08       0      57    .045       0    90.2     .08       0
Bank Sta=57,90.2
XS Rating Curve= 0 ,0
Exp/Cntr(USF)=0,0
Exp/Cntr=0.3,0.1

Type RM Length L Ch R = 1 ,40566   ,305,321.8,354.2
XS GIS Cut Line= 2
2164139.72059298432058.5277184082164306.49095565432299.045779137
#Sta/Elev= 30
       0 3412.97      13  3412.6    27.6  3411.1    37.3 3409.03    42.9 3407.37
    48.2 3406.59    56.8 3406.31    62.6 3406.59      71 3406.33      85 3404.45
    92.1  3404.2     100 3403.02   110.3 3404.22   127.2 3404.28   157.5 3400.29
   166.1  3399.5   177.6 3400.13   188.2 3401.57   202.8 3402.38   222.3 3401.26
   246.6 3402.56   251.5 3403.56   253.5 3404.43   260.5 3409.04   263.8  3410.8
   267.6 3412.34   270.9 3412.84   281.1 3413.24   285.5 3413.16   292.7 3413.62
#Mann= 4 ,-1,0
       0      .1       0      60     .08       0   157.5    .045       0
   177.6     .08       0
#XS Ineff= 2 , 0
          126.38 3409.95
Permanent Ineff=
       F       F
Bank Sta=157.5,177.6
XS Rating Curve= 0 ,0
Exp/Cntr(USF)=0,0
Exp/Cntr=0.3,0.1

Type RM Length L Ch R = 1 ,40244   ,171,173.3,178
XS GIS Cut Line= 3
2164094.03756863431979.9033150592164104.06101856432211.524670738
2163972.54282234432336.926514393
#Sta/Elev= 30
       0 3416.58    17.3 3415.61    25.3 3416.04    41.3 3415.74      57 3414.53
    73.3 3414.38   109.4 3412.74   113.4 3412.35   129.9 3405.86   133.4 3405.12
   145.4 3404.38   177.4 3404.43   185.4 3404.99   205.5 3404.13   209.5 3404.43
   229.5 3402.55   245.8 3402.68   257.4 3401.27   286.4 3400.24     298 3400.75
   303.8 3399.93     315 3400.58   331.2  3399.2   347.7 3398.25   357.4 3399.17
   367.6 3400.52   373.4  3402.3   382.9 3410.27   390.7 3415.51   413.6 3417.54
#Mann= 5 ,-1,0
       0      .1       0     130     .08       0   331.2    .045       0
   357.4     .08       0  361.84     .06       0
#XS Ineff= 2 , 0
          244.44 3406.83
Permanent Ineff=
       F       F
Bank Sta=331.2,357.4
XS Rating Curve= 0 ,0
Exp/Cntr(USF)=0,0
Exp/Cntr=0.3,0.1

Type RM Length L Ch R = 1 ,40071   ,389.9,377.2,351.3
XS GIS Cut Line= 4
2164060.96146279431987.0335163212164010.40603413432091.917166817
2163865.53077589432183.2187618542163807.42976087 432297.15711599
#Sta/Elev= 30
       0 3416.74    73.4 3413.47    77.9 3412.86    86.7 3409.18   103.1  3404.9
   118.8 3402.58   161.6 3401.56   174.1 3399.33   185.3 3399.32   194.4 3398.01
   199.4  3396.8     206 3396.59   218.4  3397.1   223.8 3398.22   227.8  3399.4
     242 3400.88   258.2 3400.31   270.4 3398.96   275.1 3398.94   287.2 3400.83
   299.5 3399.96   321.3 3400.34   334.9  3399.4   352.6 3399.62   357.2 3400.43
   361.7 3402.52   370.7  3409.9   391.2  3416.6   397.6 3417.79   415.6 3423.58
#Mann= 6 ,-1,0
       0      .1       0   194.4    .045       0   223.8      .1       0
  307.68     .06       0  377.68      .1       0  415.57     .06       0
Bank Sta=194.4,223.8
XS Rating Curve= 0 ,0
Exp/Cntr(USF)=0,0
Exp/Cntr=0.3,0.1

Type RM Length L Ch R = 1 ,39694   ,230.4,232.1,233.8
XS GIS Cut Line= 2
2163787.81123631431980.9970472272163670.85464763 432294.89344008
#Sta/Elev= 30
       0 3414.07    30.1 3412.47    34.3 3411.33    55.7 3402.07    64.2 3399.47
    81.3 3399.02   111.2 3399.89   132.5 3398.35   153.9 3399.43   158.5 3399.21
   162.4 3397.81   166.7 3396.99   192.3 3398.47   196.6 3397.91   200.8 3396.41
   205.1 3395.66   209.4 3396.43   211.8 3397.63   213.6 3398.52   226.9 3407.98
     235 3414.25   239.2 3416.36   260.6 3418.99   282.9 3423.42   289.1 3425.49
   294.7 3426.65   303.3 3427.24   313.9  3429.2   328.9 3430.58     335 3431.64
#Mann= 5 ,-1,0
       0      .1       0      30     .12       0     130      .1       0
   196.6    .045       0   211.8      .1       0
Bank Sta=196.6,211.8
XS Rating Curve= 0 ,0
Exp/Cntr(USF)=0,0
Exp/Cntr=0.3,0.1