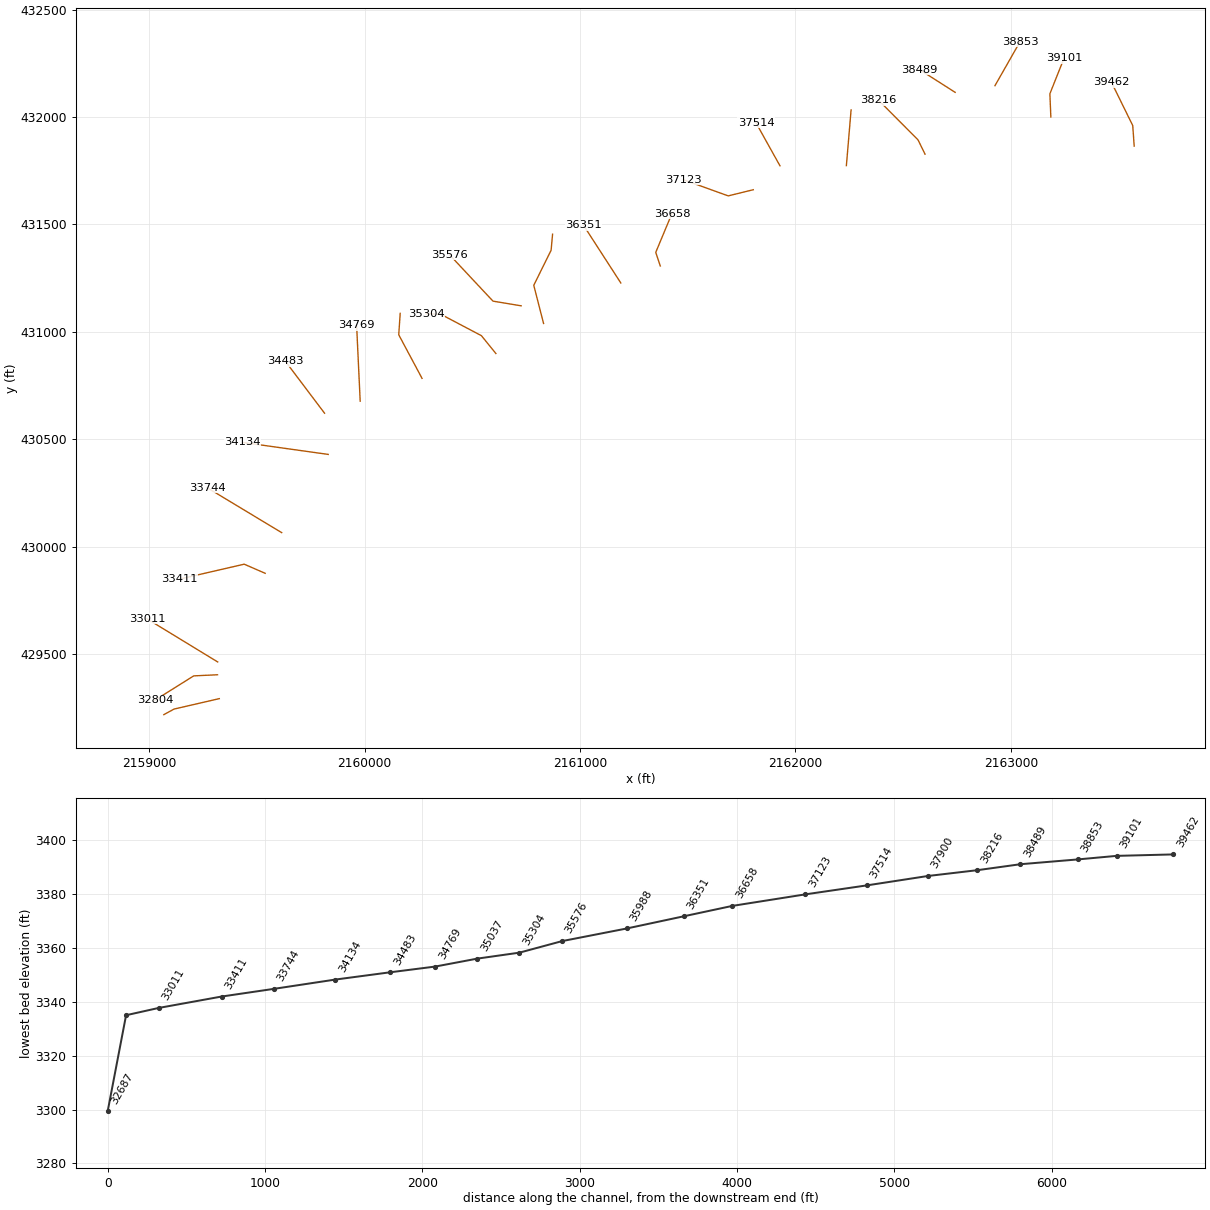
HEC-RAS study HLLSCK.prj: HLLSCK

--- HLLSCK.g01 (geometry) --- (continued)

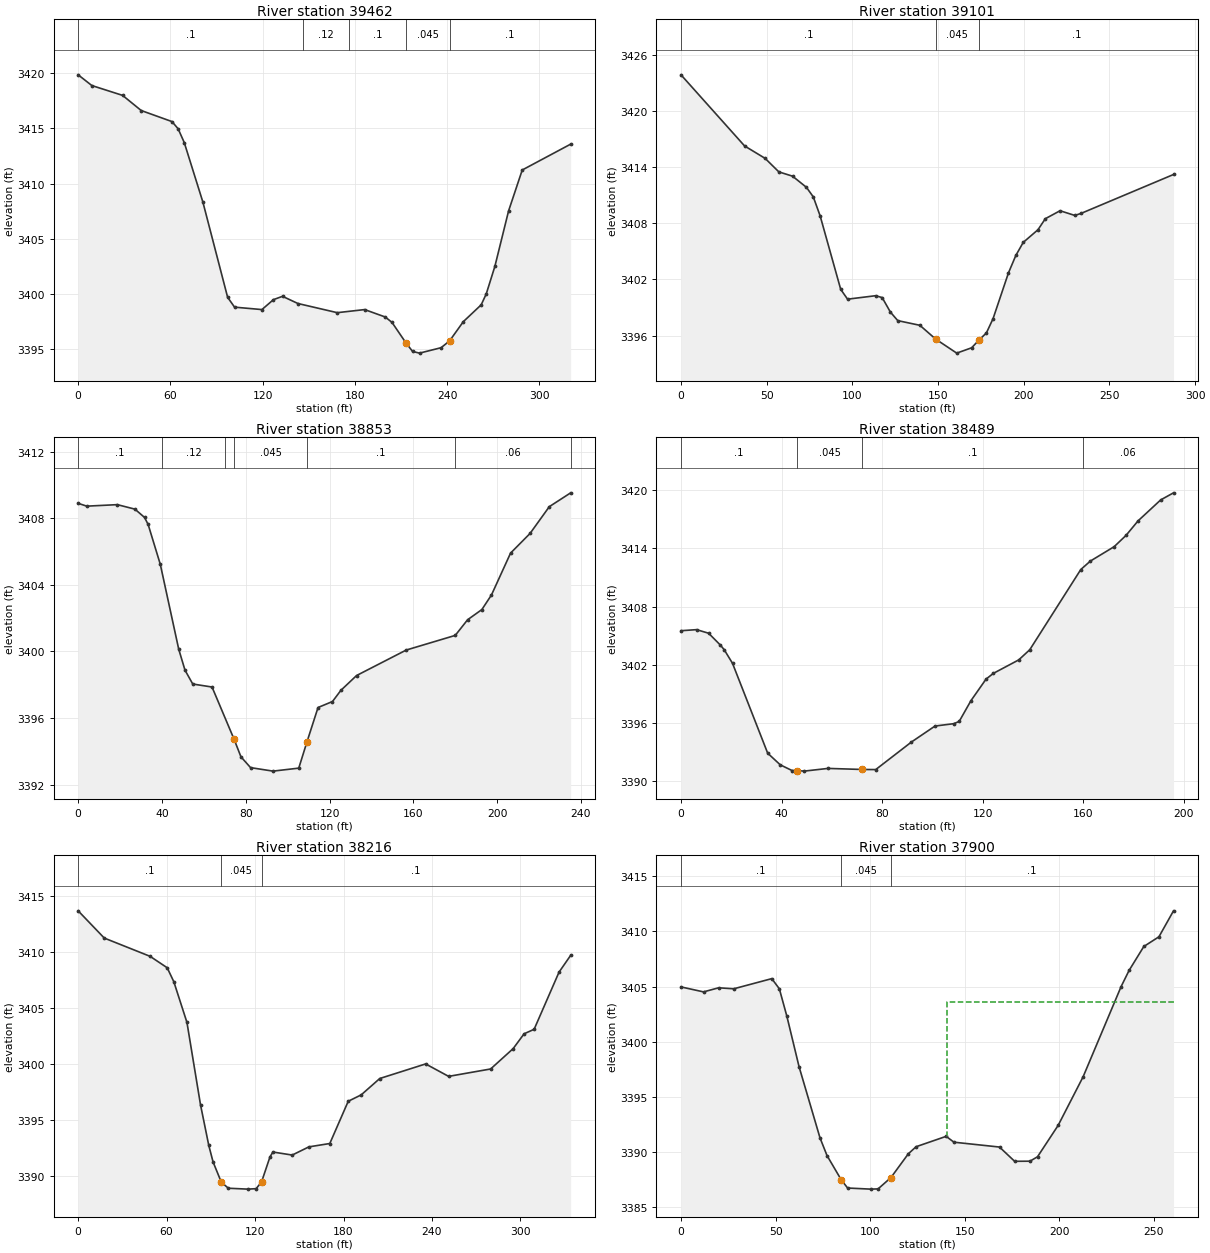
Type RM Length L Ch R = 1 ,39462   ,375.9,361,344.1
XS GIS Cut Line= 3
2163572.60226289431864.325382465 2163565.8141225431960.113585745
2163467.00896793432161.495083979
#Sta/Elev= 30
       0 3419.85     8.9 3418.88    28.9 3417.99      41 3416.62      61 3415.62
      65 3414.97      69 3413.72    81.1 3408.34    97.2 3399.72   101.7 3398.83
   119.5 3398.61     127 3399.51   132.9 3399.81   142.9 3399.16   168.5 3398.33
   186.3 3398.61   199.7 3397.94   204.1 3397.45   213.1 3395.61   217.5 3394.82
     222 3394.67     236 3395.16   241.5 3395.77   250.5 3397.52   262.1 3399.04
   265.4 3400.03     271 3402.52   279.9 3407.53   288.8 3411.24   320.3 3413.58
#Mann= 5 ,-1,0
       0      .1       0  146.03     .12       0  176.03      .1       0
   213.1    .045       0   241.5      .1       0
Bank Sta=213.1,241.5
XS Rating Curve= 0 ,0
Exp/Cntr(USF)=0,0
Exp/Cntr=0.3,0.1

Type RM Length L Ch R = 1 ,39101   ,250.5,247.4,244
XS GIS Cut Line= 3
2163185.67826066432000.0881902642163181.15155047432107.958635382
2163247.49560533432274.669896643
#Sta/Elev= 30
       0 3423.84    37.1 3416.25    49.1 3414.92    57.1 3413.48    65.1 3413.02
    73.2 3411.83    77.2 3410.81    81.2 3408.78    93.2 3400.94    97.2 3399.89
   113.6 3400.26   117.4 3400.06   122.2 3398.51   126.5  3397.6   139.4  3397.1
   148.6 3395.63   160.9 3394.13   169.6  3394.7   173.9 3395.53   178.2 3396.28
   182.1 3397.81   191.1  3402.7   195.4 3404.56   199.7 3405.95   208.3  3407.3
   212.6 3408.48   221.2 3409.33   229.8 3408.83   233.5 3409.05   287.4  3413.2
#Mann= 3 ,-1,0
       0      .1       0   148.6    .045       0   173.9      .1       0
Bank Sta=148.6,173.9
XS Rating Curve= 0 ,0
Exp/Cntr(USF)=0,0
Exp/Cntr=0.3,0.1

Type RM Length L Ch R = 1 ,38853   ,330.9,364.3,392.7
XS GIS Cut Line= 2
 2162926.2204502432145.6560897362163042.37307465432350.054539255
#Sta/Elev= 30
       0 3408.89     4.1 3408.72    18.7 3408.81    27.1 3408.54    31.7 3408.04
    33.4 3407.62    39.2 3405.23      48 3400.13      51 3398.87    54.7 3398.04
    63.9 3397.86    74.4 3394.73    77.7 3393.67    82.3 3393.02      93 3392.81
   105.3 3392.99   109.2 3394.56   114.5 3396.63   121.4 3396.99   125.4 3397.66
   132.9 3398.55   156.6 3400.08     180 3400.96   185.9  3401.9   192.7 3402.51
   197.3 3403.39   206.4  3405.9   215.7 3407.08   224.9 3408.69   235.1 3409.52
#Mann= 7 ,-1,0
       0      .1       0      40     .12       0      70      .1       0
    74.4    .045       0   109.2      .1       0     180     .06       0
   235.1      .1       0
Bank Sta=74.4,109.2
XS Rating Curve= 0 ,0
Exp/Cntr(USF)=0,0
Exp/Cntr=0.3,0.1

Type RM Length L Ch R = 1 ,38489   ,276.9,273.2,268.7
XS GIS Cut Line= 2
2162741.43218403432114.7323390712162576.25410121432220.325634025
#Sta/Elev= 30
       0 3405.51     6.2 3405.62      11 3405.25    15.7 3404.02    17.2 3403.55
    20.5 3402.15    34.5 3392.88    39.5 3391.68    44.2 3391.09    46.1 3391.09
      49 3391.03    58.5 3391.31    72.2  3391.2    77.5 3391.19    91.7 3394.03
   101.1 3395.68   108.5 3395.92   110.7 3396.15   115.4  3398.3   121.4 3400.52
   124.3 3401.11   134.4  3402.5   138.8 3403.55   159.1 3411.82   162.9 3412.69
   172.4 3414.18   177.1 3415.34   181.9 3416.84   190.9    3419     196 3419.73
#Mann= 4 ,-1,0
       0      .1       0    46.1    .045       0    72.2      .1       0
     160     .06       0
Bank Sta=46.1,72.2
XS Rating Curve= 0 ,0
Exp/Cntr(USF)=0,0
Exp/Cntr=0.3,0.1

Type RM Length L Ch R = 1 ,38216   ,328.7,315.3,296.7
XS GIS Cut Line= 3
2162601.58643447431826.9053946932162569.15420817 431893.27832295
2162385.87441764432078.066589119
#Sta/Elev= 30
       0 3413.65    17.7 3411.22    48.8 3409.59    60.4 3408.57    64.9 3407.32
    73.8 3403.69      83 3396.34    88.6 3392.72    91.5 3391.25    97.1 3389.44
   101.9  3388.9     115 3388.82   120.7 3388.86   124.4 3389.46   130.1 3391.69
   132.1 3392.13   145.2 3391.86   156.5 3392.59   170.7 3392.89   183.2 3396.66
     192 3397.23   204.6 3398.69   235.7 3399.99   251.3 3398.88   279.8 3399.54
   295.1 3401.36   302.5 3402.68   309.3 3403.08   326.2 3408.18   334.1 3409.68
#Mann= 3 ,-1,0
       0      .1       0    97.1    .045       0   124.4      .1       0
Bank Sta=97.1,124.4
XS Rating Curve= 0 ,0
Exp/Cntr(USF)=0,0
Exp/Cntr=0.3,0.1

Type RM Length L Ch R = 1 ,37900   ,377.3,386.1,394.2
XS GIS Cut Line= 2
2162236.53532906431773.3545093942162258.40822587432032.812319853
#Sta/Elev= 30
       0 3404.97    11.9 3404.52    19.9 3404.89    27.9  3404.8      48 3405.72
      52  3404.8      56  3402.3    62.4 3397.76    73.5  3391.3    77.2  3389.7
    84.7 3387.51    88.1 3386.76   100.2 3386.66   104.2 3386.68     1113387.707
   120.2 3389.86   124.3  3390.5   140.2 3391.44   144.3 3390.91   168.4 3390.47
   176.4 3389.18   184.5 3389.19   188.5 3389.59   199.4 3392.43   212.6 3396.83
   232.7    3405   236.9 3406.46   244.7 3408.63   252.7 3409.51   260.4 3411.86
#Mann= 3 ,-1,0
       0      .1       0    84.7    .045       0     111      .1       0
#XS Ineff= 2 , 0
                          140.58         3403.58
Permanent Ineff=
       F       F
Bank Sta=84.7,111
XS Rating Curve= 0 ,0
Exp/Cntr(USF)=0,0
Exp/Cntr=0.3,0.1

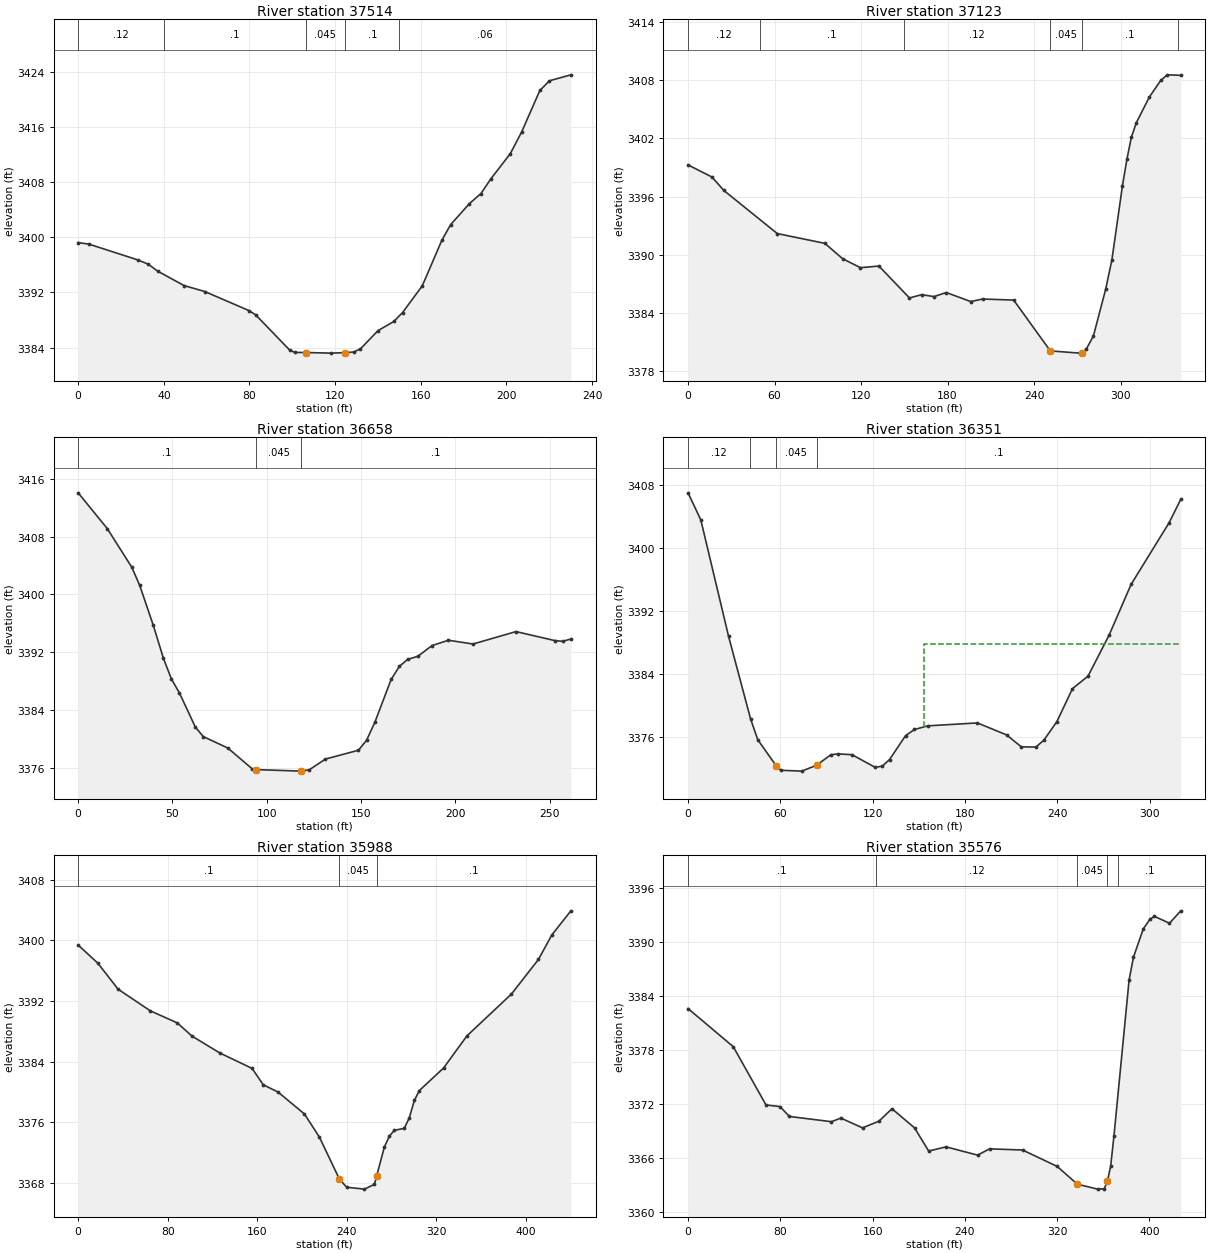
Type RM Length L Ch R = 1 ,37514   ,382.6,391.7,405.5
XS GIS Cut Line= 2
2161928.16461652431772.7430594492161816.42568006431973.873145076
#Sta/Elev= 30
       0 3399.23     5.1    3399      28  3396.7    32.7  3396.1    37.1 3395.09
    49.4    3393    59.1 3392.13    79.7 3389.37    82.9 3388.74    98.8 3383.62
   101.2 3383.29   106.2 3383.28     118 3383.19   124.7 3383.26   128.6 3383.35
   131.8  3383.8     140 3386.45   147.4 3387.78   151.5 3389.08   160.7 3392.96
   169.8 3399.54   173.9 3401.82   182.7 3404.88   188.1 3406.35   192.7 3408.47
   201.8 3412.13   207.1 3415.28   215.6  3421.3   220.1 3422.71   230.1 3423.57
#Mann= 5 ,-1,0
       0     .12       0      40      .1       0   106.2    .045       0
   124.7      .1       0     150     .06       0
Bank Sta=106.2,124.7
XS Rating Curve= 0 ,0
Exp/Cntr(USF)=0,0
Exp/Cntr=0.3,0.1

Type RM Length L Ch R = 1 ,37123   ,494.6,464.3,440
XS GIS Cut Line= 3
2161804.29043304431661.2499282132161688.13780859431632.588891012
2161479.21393214431708.012673122
#Sta/Elev= 30
       0 3399.26    16.6 3398.01    24.8 3396.63    61.9 3392.18    94.9 3391.17
   107.2 3389.59   119.6 3388.66   132.4 3388.83   153.6 3385.54   162.1 3385.88
   170.6 3385.68   179.1  3386.1   196.1 3385.17   204.4 3385.43   225.9 3385.32
   251.3 3380.08   271.7 3379.85   273.2 3379.87   276.3 3380.28   281.2 3381.62
   289.7 3386.44     294 3389.45   301.3 3397.06   304.4 3399.82   307.5  3402.1
     311 3403.62     320 3406.26     328 3407.99   332.5 3408.55   341.8  3408.5
#Mann= 6 ,-1,0
       0     .12       0      50      .1       0  149.64     .12       0
   251.3    .045       0   273.2      .1       0  339.64     .06       0
Bank Sta=251.3,273.2
XS Rating Curve= 0 ,0
Exp/Cntr(USF)=0,0
Exp/Cntr=0.3,0.1

Type RM Length L Ch R = 1 ,36658   ,285.9,307.3,319.2
XS GIS Cut Line= 3
2161372.75421905431306.2691461392161351.63556006431369.625123112
2161426.30510435431549.133724533
#Sta/Elev= 30
       0 3414.06    15.4 3409.12    28.4 3403.78    32.6 3401.27    39.8 3395.75
    45.2 3391.17    49.4 3388.33    53.7 3386.37    62.1 3381.67    66.3 3380.35
    79.3 3378.77    92.3 3375.88    94.4 3375.78   118.3 3375.57   122.6 3375.77
   131.1 3377.24   148.6 3378.46   152.9 3379.85   157.3 3382.34   165.9 3388.25
   170.3 3390.07   174.6 3391.01   180.1 3391.46   187.6 3392.94   196.3 3393.67
   209.3 3393.15   232.1 3394.87   252.6 3393.63   256.9 3393.52   261.2 3393.85
#Mann= 3 ,-1,0
       0      .1       0    94.4    .045       0   118.3      .1       0
Bank Sta=94.4,118.3
XS Rating Curve= 0 ,0
Exp/Cntr(USF)=0,0
Exp/Cntr=0.3,0.1

Type RM Length L Ch R = 1 ,36351   ,382.4,362.9,341.6
XS GIS Cut Line= 2
2161189.47442852431227.0741749242161015.99972967431496.337077056
#Sta/Elev= 30
       0 3406.95     8.3 3403.52    26.3 3388.82    40.6 3378.37    45.3 3375.71
    57.4 3372.38    60.3 3371.84    73.9 3371.73    83.5 3372.47    92.9 3373.81
    97.7 3373.91   106.6 3373.81   121.5 3372.22   126.2 3372.35     131  3373.2
   141.4 3376.22   147.2    3377   155.8 3377.46   188.1 3377.83   207.1 3376.31
   216.6 3374.81   226.1 3374.77   231.4 3375.67   239.8 3378.01   249.9 3382.17
     260 3383.75   273.7 3388.94     288 3395.36   312.6 3403.13   320.3 3406.13
#Mann= 4 ,-1,0
       0     .12       0      40      .1       0    57.4    .045       0
    83.5      .1       0
#XS Ineff= 2 , 0
                          153.53         3387.82
Permanent Ineff=
       F       F
Bank Sta=57.4,83.5
XS Rating Curve= 0 ,0
Exp/Cntr(USF)=0,0
Exp/Cntr=0.3,0.1

Type RM Length L Ch R = 1 ,35988   ,390.5,412.2,436.7
XS GIS Cut Line= 4
2160830.84542618431038.6087783222160785.40608907431216.376843363
2160865.90640327431379.4302147862160872.69454366431454.099759075
#Sta/Elev= 30
       0 3399.38    17.5 3397.01    35.7 3393.56    64.6  3390.7    88.6 3389.12
   101.7 3387.38   126.5 3385.16   155.4 3383.12   165.4 3380.96   178.6    3380
   202.2 3377.11   215.6 3374.05   233.4 3368.53   239.9 3367.45   255.8  3367.2
   264.7 3367.83   266.8 3368.98   273.6 3372.75   278.1 3374.19   282.5 3374.95
   291.4 3375.22   295.9 3376.61   300.4 3378.89   304.8 3380.19   326.5 3383.17
   347.4 3387.41   387.2 3392.93   411.3 3397.49   423.3 3400.73   440.3  3403.9
#Mann= 3 ,-1,0
       0      .1       0   233.4    .045       0   266.8      .1       0
Bank Sta=233.4,266.8
XS Rating Curve= 0 ,0
Exp/Cntr(USF)=0,0
Exp/Cntr=0.3,0.1

Type RM Length L Ch R = 1 ,35576   ,265,271.7,278.6
XS GIS Cut Line= 3
2160726.83426064431120.7378160422160596.09970498431142.526908652
2160394.96961935431357.903708677
#Sta/Elev= 30
       0 3382.58    39.2 3378.34    67.6 3371.86    79.7 3371.68    87.9 3370.58
   124.3    3370   132.5  3370.4   151.3 3369.31   165.5 3370.06   176.8 3371.44
   196.4 3369.31   208.6 3366.74   223.7  3367.2   251.1 3366.28   261.4 3366.98
     290 3366.85     320 3365.03   337.5 3363.05   355.1  3362.5   360.8 3362.53
   363.6 3363.39   366.4 3365.05   369.3 3368.45   382.4 3385.77   386.2  3388.3
   394.7 3391.44   400.4  3392.5   404.3 3392.84   417.4 3392.07   427.2 3393.45
#Mann= 5 ,-1,0
       0      .1       0  162.54     .12       0   337.5    .045       0
   363.6     .12       0  372.54      .1       0
Bank Sta=337.5,363.6
XS Rating Curve= 0 ,0
Exp/Cntr(USF)=0,0
Exp/Cntr=0.3,0.1

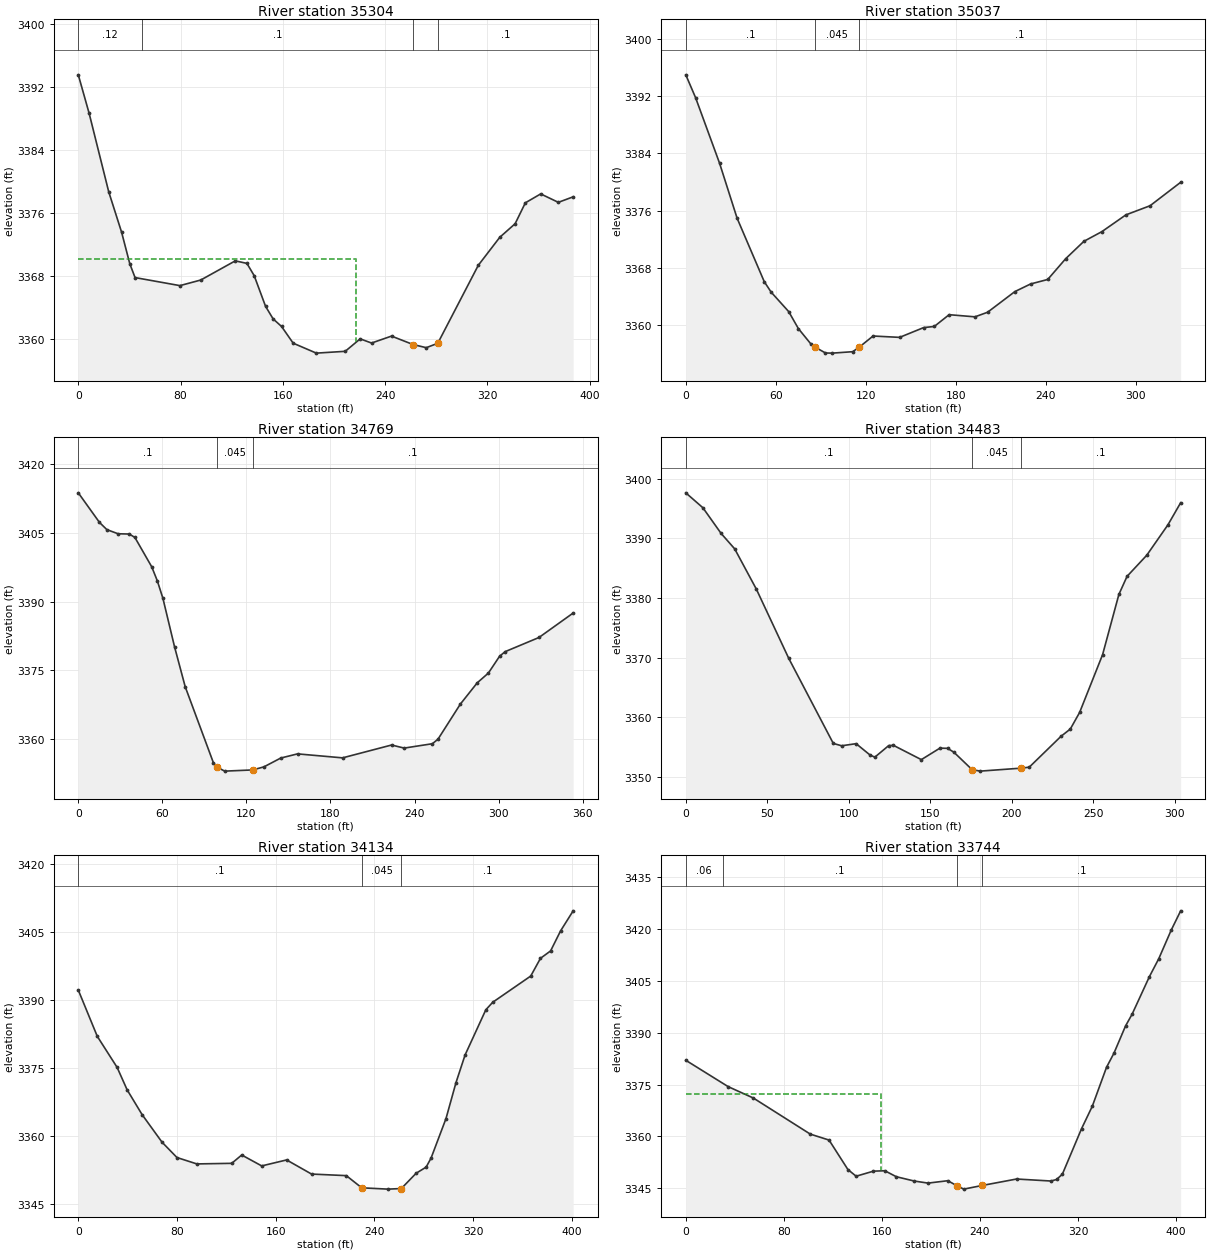
Type RM Length L Ch R = 1 ,35304   ,277.2,267.5,256.9
XS GIS Cut Line= 4
2160609.50837735430898.6566798292160542.46501548 430981.62284015
 2160353.9055602 431081.349840942160286.86219833431083.863967011
#Sta/Elev= 30
       0  3393.5     8.5 3388.61    23.8 3378.67    33.9 3373.53    40.3 3369.54
    44.4 3367.79    79.5 3366.77    95.8 3367.48   122.8 3369.91   131.9 3369.59
   137.6 3368.03   146.5 3364.14   152.4 3362.55     159 3361.59   168.1 3359.47
   186.2 3358.21   208.8 3358.44   220.5 3360.02   229.4 3359.49     245 3360.37
   261.9  3359.3   272.2  3358.9   281.2 3359.46   312.9 3369.35   329.7  3372.9
   341.7 3374.62   349.7 3377.27   361.7  3378.4   375.5 3377.33   387.1 3378.03
#Mann= 4 ,-1,0
       0     .12       0      50      .1       0   261.9    .045       0
   281.2      .1       0
#XS Ineff= 2 , 0
           217.2 3370.13
Permanent Ineff=
       F       F
Bank Sta=261.9,281.2
XS Rating Curve= 0 ,0
Exp/Cntr(USF)=0,0
Exp/Cntr=0.3,0.1

Type RM Length L Ch R = 1 ,35037   ,274.4,267.6,258.7
XS GIS Cut Line= 3
2160266.74918977430783.0068805942160158.64176874430985.813050268
2160165.34610493431085.540051058
#Sta/Elev= 30
       0 3395.03     6.5 3391.84    22.5 3382.64    34.2 3374.92    52.3 3366.02
    56.9 3364.55    68.6 3361.82      75 3359.45    83.3  3357.3    86.3 3356.82
    93.1 3356.02    97.7    3356   111.2  3356.2   115.5 3356.82   124.8  3358.4
   142.5 3358.21   158.5 3359.58   165.6 3359.74   175.5 3361.39   192.7 3361.09
   201.1 3361.73   219.3 3364.63   229.8  3365.7   241.2 3366.33   253.2 3369.25
   265.3 3371.68   277.3 3373.04   293.3 3375.39   309.4 3376.67   329.8 3379.96
#Mann= 3 ,-1,0
       0      .1       0    86.3    .045       0   115.5      .1       0
Bank Sta=86.3,115.5
XS Rating Curve= 0 ,0
Exp/Cntr(USF)=0,0
Exp/Cntr=0.3,0.1

Type RM Length L Ch R = 1 ,34769   ,270.7,285.7,295.1
XS GIS Cut Line= 2
2159979.64220025430676.8031599692159963.08828374431029.608505641
#Sta/Elev= 30
       0 3413.69    15.1 3407.25    20.4 3405.67    28.4 3404.77    36.4 3404.71
    40.4 3403.97    52.4 3397.58    56.4 3394.52    60.4  3390.7    68.7 3380.14
    76.3 3371.45    96.5 3354.82    99.3 3353.87   104.5 3353.05   124.5 3353.31
   132.5 3353.98   144.5  3355.9   156.5 3356.81   188.6 3355.94   223.6 3358.74
   232.6 3358.07   252.7 3359.02   256.7    3360   272.7 3367.66   284.7 3372.28
   292.7 3374.42   300.7 3378.09   304.7 3379.09   328.8 3382.17   353.2  3387.5
#Mann= 3 ,-1,0
       0      .1       0    99.3    .045       0   124.5      .1       0
Bank Sta=99.3,124.5
XS Rating Curve= 0 ,0
Exp/Cntr(USF)=0,0
Exp/Cntr=0.3,0.1

Type RM Length L Ch R = 1 ,34483   ,331.6,349.6,363.4
XS GIS Cut Line= 2
2159814.18144767430620.8162345612159631.70555671430863.413881052
#Sta/Elev= 30
       0 3397.67    10.5 3395.16    21.7 3390.84      30 3388.26    43.3 3381.49
    63.2 3369.85    90.5 3355.58    95.6 3355.19   104.5 3355.54   113.1 3353.62
     116 3353.28   124.5 3355.22   127.4 3355.26   144.5 3352.86   155.9 3354.79
   160.6 3354.76   164.5  3354.1   175.6 3351.19   180.6 3350.93   205.7 3351.43
   210.7 3351.59   230.2 3356.78   235.9    3358   241.6 3360.78   255.7 3370.49
   265.7 3380.61   270.7 3383.64   282.8 3387.19   295.8  3392.3   303.6 3396.01
#Mann= 3 ,-1,0
       0      .1       0   175.6    .045       0   205.7      .1       0
Bank Sta=175.6,205.7
XS Rating Curve= 0 ,0
Exp/Cntr(USF)=0,0
Exp/Cntr=0.3,0.1

Type RM Length L Ch R = 1 ,34134   ,394.8,389.6,376.5
XS GIS Cut Line= 2
2159831.38717465430428.8735725992159434.09317835430484.743040829
#Sta/Elev= 30
       0  3392.2    15.4 3381.98    31.5 3375.11    39.6 3370.16    51.7  3364.7
    67.9 3358.59      80  3355.2    96.1 3353.79   124.4 3353.92   132.5 3355.76
   148.7 3353.35   168.9 3354.67   189.1 3351.55   217.3  3351.2   229.8 3348.51
     251 3348.22   261.9 3348.35   273.9 3351.73     282 3353.08     286 3355.08
   298.1 3363.81   306.2 3371.75   313.6 3377.88   330.4 3387.85     336 3389.51
   366.8  3395.3   374.7 3399.22   382.9 3400.85     391 3405.28   401.2 3409.71
#Mann= 3 ,-1,0
       0      .1       0   229.8    .045       0   261.9      .1       0
Bank Sta=229.8,261.9
XS Rating Curve= 0 ,0
Exp/Cntr(USF)=0,0
Exp/Cntr=0.3,0.1

Type RM Length L Ch R = 1 ,33744   ,321.7,333.4,348.1
XS GIS Cut Line= 2
 2159615.1516402430064.687409325  2159269.588633430273.680605295
#Sta/Elev= 30
       0    3382    34.6 3374.38    55.1  3371.1   101.6 3360.67   116.9 3358.95
   132.3 3350.43     139 3348.51   153.1 3349.97   162.4 3350.09   171.8 3348.36
   186.5 3347.11   197.7 3346.52   213.8 3347.21     221  3345.8   226.8 3344.78
   241.9 3345.84   269.9  3347.7     298 3347.12   302.6 3347.57   307.3 3349.12
   322.9 3362.22   331.7 3368.73   343.3 3379.97   349.4 3384.08   358.8  3391.9
   364.2 3395.33   378.3 3406.17   385.9 3411.32   396.1 3419.61   403.8 3425.17
#Mann= 4 ,-1,0
       0     .06       0      30      .1       0     221    .045       0
   241.9      .1       0
#XS Ineff= 2 , 0
          158.94 3372.25
Permanent Ineff=
       F       F
Bank Sta=221,241.9
XS Rating Curve= 0 ,0
Exp/Cntr(USF)=0,0
Exp/Cntr=0.3,0.1

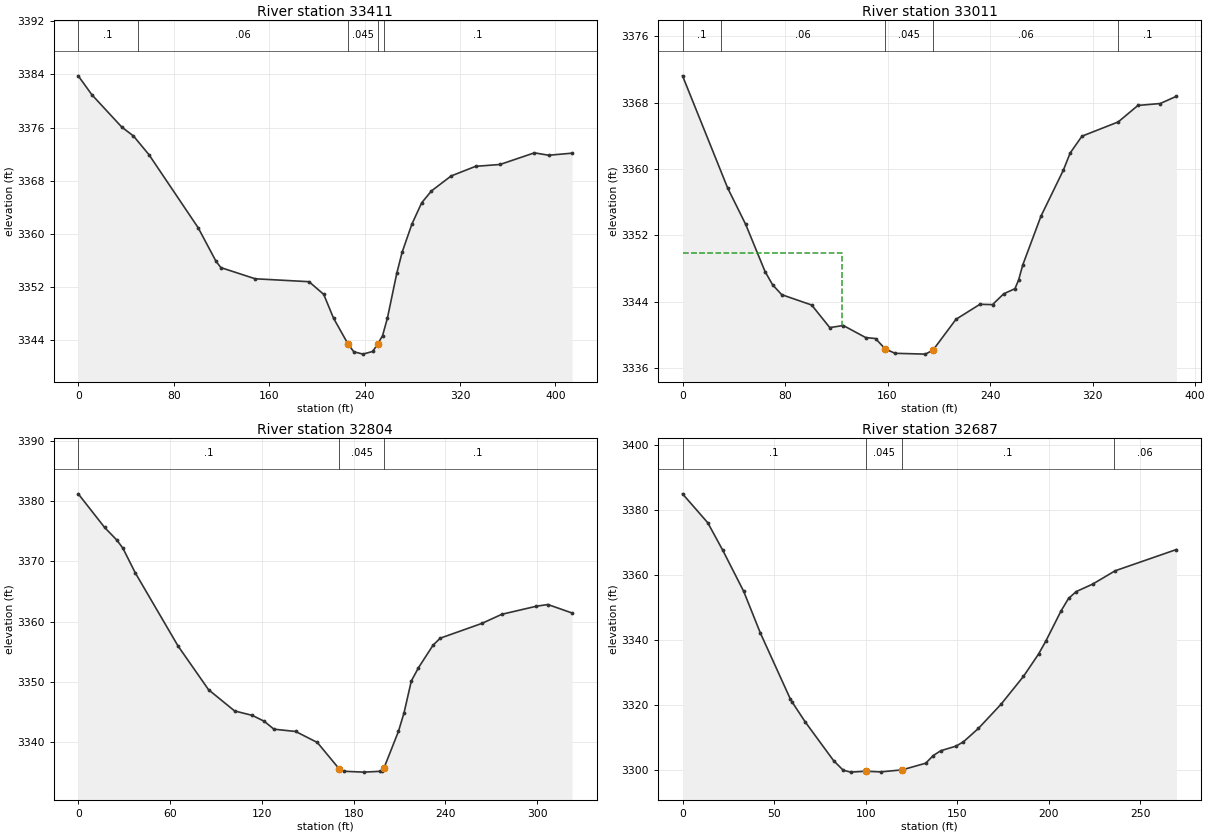
Type RM Length L Ch R = 1 ,33411   ,410.5,399.6,382.4
XS GIS Cut Line= 3
2159538.58977633429875.3519892142159441.33551682429917.771400277
2159141.29578003429848.451874881
#Sta/Elev= 30
       0  3383.8    11.4 3380.96    36.6 3376.07    46.3 3374.75    59.4 3371.91
   100.5 3360.95   115.5 3355.89   119.6 3354.94   148.3 3353.26   193.5 3352.82
   205.8 3350.91     214 3347.34   226.3  3343.4     231 3342.28   238.7 3341.92
   246.9 3342.33   250.9 3343.41   255.1 3344.69   259.2 3347.35     267 3354.06
   271.5 3357.24   279.7 3361.48   287.9 3364.69   296.1 3366.48   312.6 3368.73
   333.1 3370.18   353.6 3370.46   382.4 3372.21   394.4 3371.85     414 3372.16
#Mann= 5 ,-1,0
       0      .1       0      50     .06       0   226.3    .045       0
   250.9     .06       0   256.1      .1       0
Bank Sta=226.3,250.9
XS Rating Curve= 0 ,0
Exp/Cntr(USF)=0,0
Exp/Cntr=0.3,0.1

Type RM Length L Ch R = 1 ,33011   ,189.1,207.2,235.5
XS GIS Cut Line= 2
2159318.18652659429462.5792862052158989.48782184429663.709371832
#Sta/Elev= 30
       0 3371.25    35.2 3357.73    49.3 3353.33    64.4 3347.65    70.3 3346.05
    77.4 3344.86   100.8 3343.61   114.9 3340.89   125.5 3341.14   142.9 3339.69
   150.6 3339.57   158.3  3338.3   165.9 3337.79   189.5 3337.69   195.4 3338.16
   213.4 3341.89   232.1  3343.7   241.9 3343.66   250.6 3344.96   259.4 3345.58
   262.3 3346.64   265.5 3348.44   279.7 3354.32   297.2 3359.88   302.5 3361.94
   311.7 3363.97     340 3365.69   355.4 3367.68   372.8 3367.91   385.4 3368.78
#Mann= 5 ,-1,0
       0      .1       0      30     .06       0   158.3    .045       0
   195.4     .06       0     340      .1       0
#XS Ineff= 2 , 0
          124.06 3349.94
Permanent Ineff=
       F       F
Bank Sta=158.3,195.4
XS Rating Curve= 0 ,0
Exp/Cntr(USF)=0,0
Exp/Cntr=0.3,0.1

Type RM Length L Ch R = 1 ,32804   ,122.8,117.2,114.4
XS GIS Cut Line= 3
2159317.31684709429402.9095270482159206.90942718429397.738752843
2159027.22062744429284.785751475
#Sta/Elev= 30
       0  3381.2    17.2 3375.63    25.2 3373.53    29.2 3372.17    37.2 3368.12
    65.2 3355.95    85.2 3348.67   102.2 3345.15   113.8 3344.41   121.6 3343.43
   127.9 3342.12   142.1 3341.74   156.3 3339.91   170.5 3335.55   173.8 3335.13
   186.7 3334.99     197 3335.12   198.8 3335.23   199.9 3335.71   209.3 3341.75
     213 3344.88   217.7 3350.11   222.4 3352.33   231.9 3356.06   236.6 3357.23
   263.8 3359.68   276.9  3361.2   299.5 3362.54     307 3362.82   322.8 3361.41
#Mann= 3 ,-1,0
       0      .1       0   170.5    .045       0   199.9      .1       0
Bank Sta=170.5,199.9
XS Rating Curve= 0 ,0
Exp/Cntr(USF)=0,0
Exp/Cntr=0.3,0.1

Type RM Length L Ch R = 1 ,32687   ,330.7,329.6,328.2
XS GIS Cut Line= 3
2159325.59139796429291.7862329272159115.60860886429243.188920914
2159068.11956086429217.116502407
#Sta/Elev= 30
       0 3385.07    13.8 3376.14      22 3367.64    33.4 3355.01    42.5 3342.18
    58.9  3321.8      60 3320.76    67.1 3314.69    82.5 3302.83    87.7  3299.9
    91.8 3299.29     100 3299.57   108.2 3299.36     120    3300   132.8 3302.04
   136.9 3304.39     141 3305.88   149.3 3307.29   153.4 3308.63   161.6 3312.77
   173.9 3320.19   186.2 3328.81   194.4 3335.66   198.5 3339.79   206.7 3348.97
   210.8 3352.83     215 3354.94     224 3357.25   236.3 3361.36   269.7  3367.9
#Mann= 4 ,-1,0
       0      .1       0     100    .045       0     120      .1       0
  235.53     .06       0
Bank Sta=100,120
XS Rating Curve= 0 ,0
Exp/Cntr(USF)=0,0
Exp/Cntr=0.3,0.1