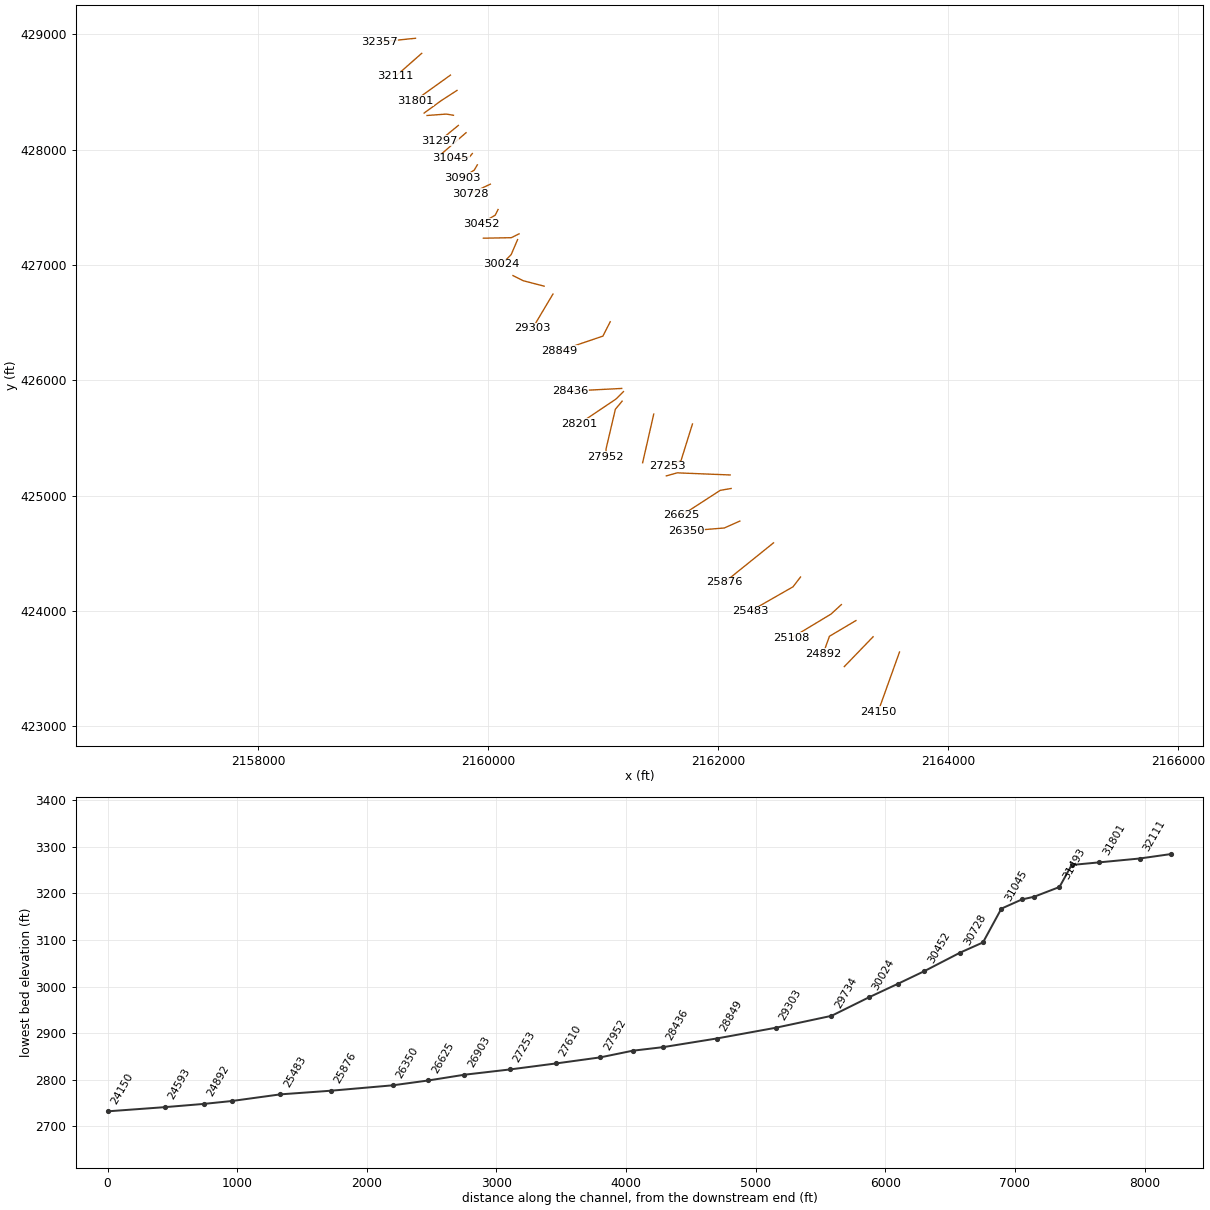
HEC-RAS study HLLSCK.prj: HLLSCK

--- HLLSCK.g01 (geometry) --- (continued)

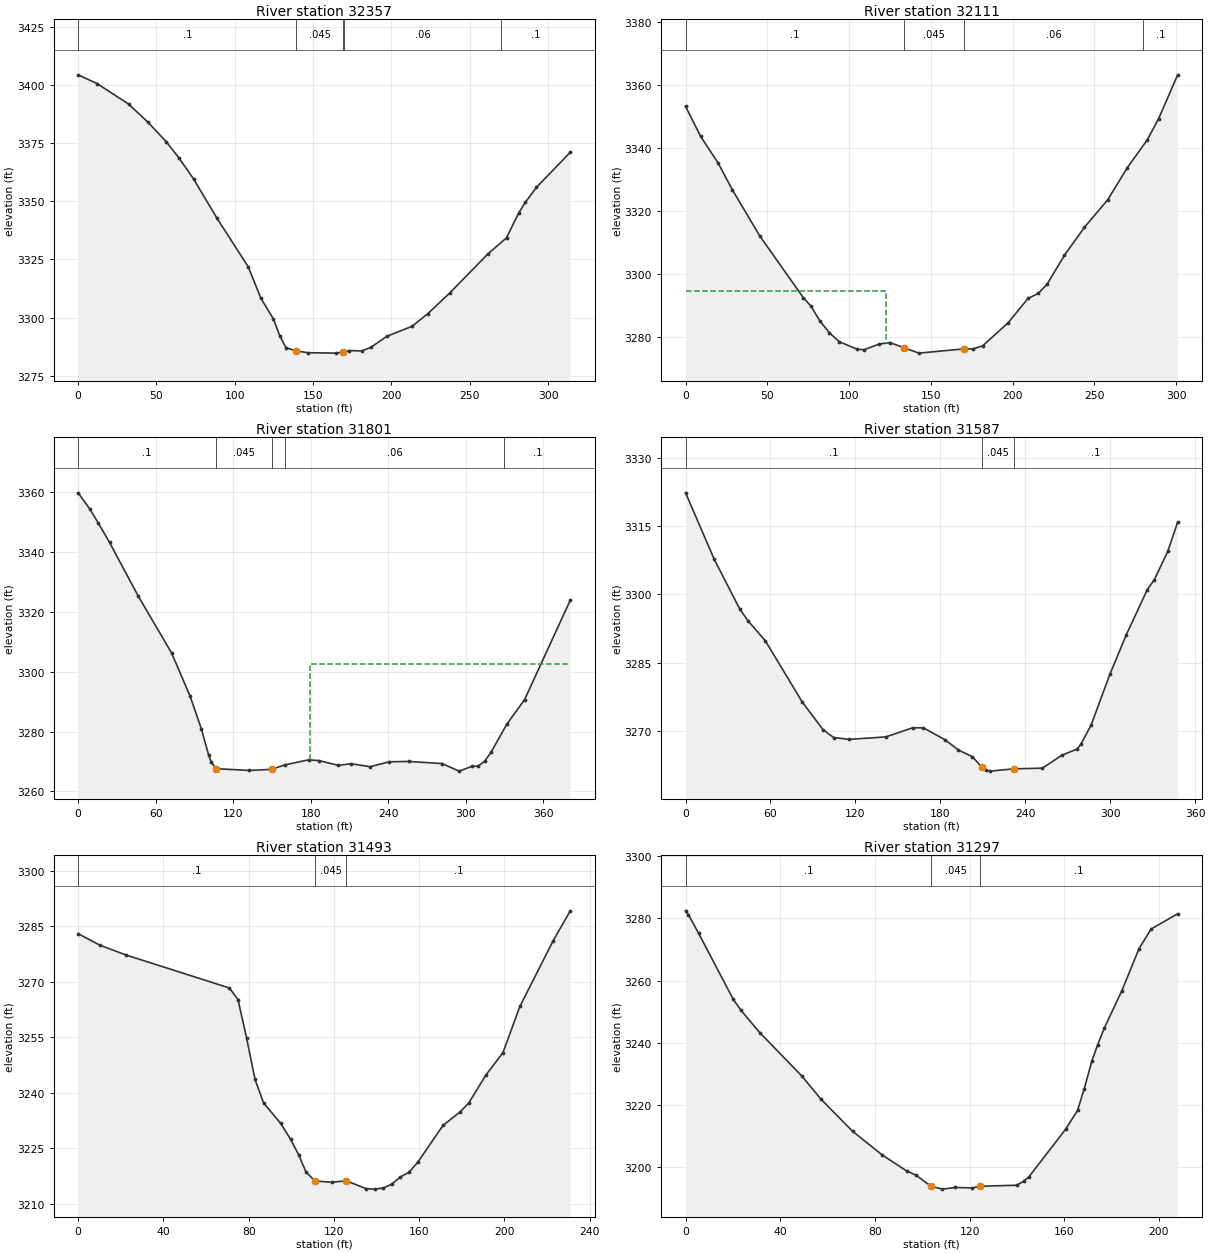
Type RM Length L Ch R = 1 ,32357   ,228.7,245.8,255.5
XS GIS Cut Line= 2
2159368.23797985428965.877098389 2159055.6483051428934.031501498
#Sta/Elev= 30
       0 3404.25    12.1 3400.49    32.2 3391.69    44.3 3384.09    56.4 3375.43
    64.4 3368.51    73.7 3359.54    88.5 3342.83   108.6 3321.82   116.7 3308.29
   124.7 3299.37   128.7 3292.26   132.7 3287.07   139.4 3285.68   146.7 3284.93
   164.9 3284.75   169.4 3285.31     173 3285.85     181  3285.7   186.8 3287.17
   197.1 3291.98   213.2 3296.26   223.3 3301.72   237.3  3310.6   261.4 3327.21
   273.5 3334.24   281.3 3344.98   285.5 3349.47   292.6 3355.92   314.2 3370.98
#Mann= 5 ,-1,0
       0      .1       0   139.4    .045       0   169.4      .1       0
     170     .06       0     270      .1       0
Bank Sta=139.4,169.4
XS Rating Curve= 0 ,0
Exp/Cntr(USF)=0,0
Exp/Cntr=0.3,0.1

Type RM Length L Ch R = 1 ,32111   ,311.4,310.3,304.2
XS GIS Cut Line= 2
2159422.33824825428835.2356585132159196.06690192428636.899046298
#Sta/Elev= 30
       0 3353.32     9.2 3343.82      20 3335.27    28.5 3326.95    45.4 3312.19
      72 3292.64    76.7 3289.94      82 3285.33      88 3281.46    94.1 3278.63
     105 3276.26   109.3 3276.14   118.4 3277.92   124.9 3278.39   133.4 3276.79
   142.7 3275.04   170.2 3276.39   175.9  3276.4   181.6 3277.34   197.3  3284.7
   209.4  3292.4   215.6 3293.96     221 3296.85   231.6 3306.04   243.9 3314.97
   258.1 3323.67   270.1 3333.87   282.3 3342.69   289.3 3349.47   300.9 3363.33
#Mann= 4 ,-1,0
       0      .1       0   133.4    .045       0   170.2     .06       0
     280      .1       0
#XS Ineff= 2 , 0
          122.75  3294.8
Permanent Ineff=
       F       F
Bank Sta=133.4,170.2
XS Rating Curve= 0 ,0
Exp/Cntr(USF)=0,0
Exp/Cntr=0.3,0.1

Type RM Length L Ch R = 1 ,31801   ,219,213.8,201.5
XS GIS Cut Line= 2
2159671.93123637428646.3427447292159362.18839038428424.574198191
#Sta/Elev= 30
       0 3359.85     8.9 3354.53    15.7 3349.66    24.3 3343.26    46.5 3325.33
    72.3 3306.33    86.7  3291.8    95.3 3281.02     101 3272.18     103 3269.85
   106.7 3267.62   132.5 3267.03   149.7 3267.39     160 3268.89   178.4 3270.58
   186.6 3270.31   201.3 3268.72   211.2 3269.28     226 3268.28   240.8 3269.93
   256.2 3270.03   281.6 3269.33   294.9  3266.8   304.7 3268.38   309.6 3268.47
   314.6 3270.11   319.5 3273.03   331.8 3282.49   345.6 3290.74   380.9 3323.94
#Mann= 5 ,-1,0
       0      .1       0   106.7    .045       0   149.7      .1       0
     160     .06       0     330      .1       0
#XS Ineff= 2 , 0
                          179.71         3302.46
Permanent Ineff=
       F       F
Bank Sta=106.7,149.7
XS Rating Curve= 0 ,0
Exp/Cntr(USF)=0,0
Exp/Cntr=0.3,0.1

Type RM Length L Ch R = 1 ,31587   ,102.8,94.1,87.3
XS GIS Cut Line= 3
2159729.24966504428513.8771931362159592.52866668428425.671535599
2159442.81534223428317.063591726
#Sta/Elev= 30
       0 3322.33    20.3 3307.69    38.2 3296.84    44.1 3294.21    56.3 3289.84
    82.3 3276.42    97.2 3270.24   104.6 3268.55   115.5 3268.14   141.5 3268.68
   160.4 3270.68   168.1 3270.68   183.4 3268.04   192.8 3265.79   202.7 3264.32
   209.1 3262.12     212 3261.31   214.9 3261.16   232.3 3261.67   252.1 3261.81
   265.7 3264.62   276.8 3266.04   279.3 3267.07   286.5 3271.25   299.8 3282.45
   311.4 3291.13   326.2 3301.04   331.2 3303.22   340.7 3309.46   347.7 3315.91
#Mann= 3 ,-1,0
       0      .1       0   209.1    .045       0   232.3      .1       0
Bank Sta=209.1,232.3
XS Rating Curve= 0 ,0
Exp/Cntr(USF)=0,0
Exp/Cntr=0.3,0.1

Type RM Length L Ch R = 1 ,31493   ,187.1,195.6,203.1
XS GIS Cut Line= 3
2159698.25376759428298.1239228692159635.90198285428308.515886992
2159468.64084602428296.144501131
#Sta/Elev= 30
       0 3282.94    10.2 3279.82    22.4 3277.18      71 3268.25      75 3265.11
      79 3254.84      83 3243.53      87  3237.2      95 3231.68    99.7 3227.35
   103.4 3223.24   106.9 3218.55   111.1 3216.07   119.1 3215.76   125.8 3216.14
   135.1 3214.03   139.1 3213.89   143.2  3214.2   147.2 3215.25   151.2 3217.18
   155.2 3218.43   159.4  3221.2   171.2 3231.12   179.3  3234.8   183.3  3237.2
   191.3  3244.7   199.3 3250.76   207.3 3263.32   222.9 3281.05   230.9 3289.11
#Mann= 3 ,-1,0
       0      .1       0   111.1    .045       0   125.8      .1       0
Bank Sta=111.1,125.8
XS Rating Curve= 0 ,0
Exp/Cntr(USF)=0,0
Exp/Cntr=0.3,0.1

Type RM Length L Ch R = 1 ,31297   ,94.4,94.7,95.2
XS GIS Cut Line= 2
2159740.42044933428209.9288667132159579.54152209 428078.23894315
#Sta/Elev= 30
       0 3282.42     1.2  3281.2     5.5  3275.2    20.1 3254.02    23.4 3250.44
    31.3 3243.29      49  3229.4    57.2 3221.86    70.6 3211.51    83.1  3203.9
    93.4 3198.78    97.4  3197.4   103.7 3193.85   108.5 3192.93     114 3193.46
   121.2 3193.32   124.4 3193.86   139.9 3194.18   142.8 3195.46   145.1 3196.93
   160.6 3212.23   165.6 3218.24   168.4 3225.17   171.7 3234.25   174.1 3239.36
   176.9 3244.73   184.3 3256.71   191.6 3270.29   196.7 3276.58   207.9 3281.48
#Mann= 3 ,-1,0
       0      .1       0   103.7    .045       0   124.4      .1       0
Bank Sta=103.7,124.4
XS Rating Curve= 0 ,0
Exp/Cntr(USF)=0,0
Exp/Cntr=0.3,0.1

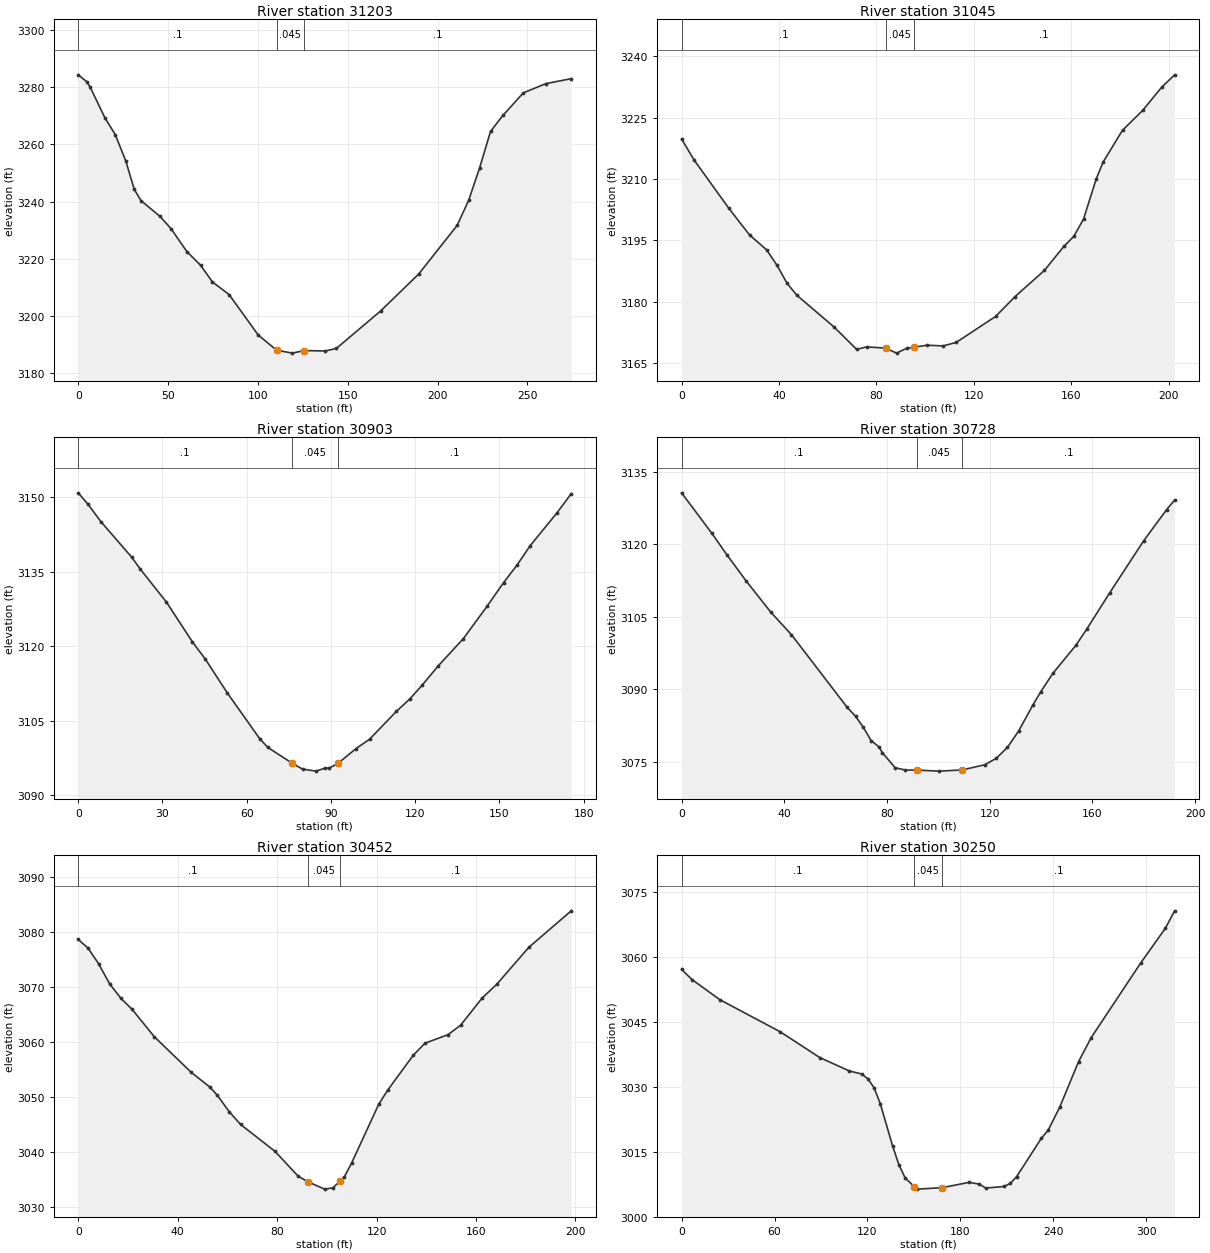
Type RM Length L Ch R = 1 ,31203   ,164.5,157.9,152.8
XS GIS Cut Line= 2
2159807.81576027428146.908401508 2159599.8260537427967.900867169
#Sta/Elev= 30
       0 3284.25     4.8 3281.84     6.6 3280.03    14.9  3269.2    20.6 3263.41
    26.5 3254.15    31.2 3244.27      35 3240.29    45.6  3234.8    51.7 3230.51
    60.5 3222.52    68.1 3217.77    74.7 3211.95      84 3207.52   100.2  3193.4
   110.4 3188.12   119.2 3187.08   125.8 3187.97   137.6 3187.83   143.7 3188.73
   168.4 3201.85   189.5 3214.69   210.9 3231.66   217.3 3240.41   223.4 3251.72
   229.5  3264.5   236.4 3270.09   247.7 3277.92   260.2 3281.16   274.4 3282.91
#Mann= 3 ,-1,0
       0      .1       0   110.4    .045       0   125.8      .1       0
Bank Sta=110.4,125.8
XS Rating Curve= 0 ,0
Exp/Cntr(USF)=0,0
Exp/Cntr=0.3,0.1

Type RM Length L Ch R = 1 ,31045   ,137.6,142,145.8
XS GIS Cut Line= 4
2159862.30198722427966.2929801922159839.75857299427938.801011613
2159757.28266725427921.2061517232159674.80676151427925.604866695
#Sta/Elev= 30
       0 3219.76     5.1 3214.67    19.4 3202.83    27.9 3196.31    34.9 3192.69
    39.2 3188.88    43.3  3184.5    47.4 3181.53    62.5 3173.87    71.9 3168.33
      76 3168.93    83.8 3168.64    88.3 3167.41    92.4 3168.58    95.3 3168.84
   100.8 3169.35   107.4 3169.17   112.8 3170.03     129 3176.39     137 3181.25
     149 3187.62     157  3193.5   161.1 3195.96   165.1  3200.2   170.3 3209.99
   173.1  3214.1   181.1 3221.91   189.4 3226.77   197.2 3232.44   202.5 3235.46
#Mann= 3 ,-1,0
       0      .1       0    83.8    .045       0    95.3      .1       0
Bank Sta=83.8,95.3
XS Rating Curve= 0 ,0
Exp/Cntr(USF)=0,0
Exp/Cntr=0.3,0.1

Type RM Length L Ch R = 1 ,30903   ,176.1,175.2,171.6
XS GIS Cut Line= 3
2159905.88821764427868.1744334582159879.07087289427822.920164193
2159775.99170401427755.876802317
#Sta/Elev= 30
       0 3150.86     3.5 3148.56     8.1 3145.05    19.1 3137.87    22.1 3135.51
    31.4 3128.88    40.7 3120.83    45.3 3117.36    53.1 3110.58    64.6 3101.39
    67.5 3099.61    76.2 3096.41    79.9 3095.23    84.7 3094.82    87.8  3095.4
    89.5 3095.45    92.5 3096.38      99 3099.37   103.8 3101.25   113.3 3106.84
   118.1 3109.35   122.5 3112.12   128.2 3115.99   137.2 3121.51   145.6    3128
   151.5 3132.77   156.3 3136.31     161 3140.23   170.6 3146.88   175.6  3150.7
#Mann= 3 ,-1,0
       0      .1       0    76.2    .045       0    92.5      .1       0
Bank Sta=76.2,92.5
XS Rating Curve= 0 ,0
Exp/Cntr(USF)=0,0
Exp/Cntr=0.3,0.1

Type RM Length L Ch R = 1 ,30728   ,273.8,276.2,275.3
XS GIS Cut Line= 2
2160018.85176073427700.7471510982159845.37706188427618.535228598
#Sta/Elev= 30
       0 3130.64    11.8 3122.26    17.7 3117.78    25.1 3112.44    34.7 3105.98
    42.8 3101.29    64.4 3086.32    67.8 3084.39    70.8  3082.1    73.8  3079.4
    76.8 3078.12    78.2  3076.9    83.1 3073.79    87.1 3073.29    91.5 3073.28
   100.3 3073.07   109.2 3073.31   118.1 3074.39   122.5 3075.71   126.9 3077.97
   131.3 3081.41   136.8 3086.74   139.8 3089.44   144.6  3093.3   153.5 3099.06
   157.9 3102.54   166.7 3109.94     180 3120.76   188.9 3127.17     192 3129.16
#Mann= 3 ,-1,0
       0      .1       0    91.5    .045       0   109.2      .1       0
Bank Sta=91.5,109.2
XS Rating Curve= 0 ,0
Exp/Cntr(USF)=0,0
Exp/Cntr=0.3,0.1

Type RM Length L Ch R = 1 ,30452   ,208.8,201.7,194.9
XS GIS Cut Line= 3
2160085.97892681427480.5097073382160061.08907871427431.484248967
2159937.39407605427359.077418141
#Sta/Elev= 30
       0 3078.72       4 3077.13     8.2 3074.31    12.7 3070.61    17.2 3068.01
    21.7    3066    30.6 3061.03    45.5 3054.53    53.1 3051.81      56 3050.35
    60.7 3047.41    65.3 3045.07    79.2 3040.16    88.5 3035.64    92.4 3034.63
    99.1  3033.3   102.4 3033.53   105.5 3034.82   107.1 3035.58     110 3038.07
   120.9 3048.76   124.6 3051.38   134.8 3057.68   139.5 3059.85   148.7 3061.39
   153.8 3063.11   162.5 3068.08   168.4 3070.59   181.2 3077.27   198.3 3083.93
#Mann= 3 ,-1,0
       0      .1       0    92.4    .045       0   105.5      .1       0
Bank Sta=92.4,105.5
XS Rating Curve= 0 ,0
Exp/Cntr(USF)=0,0
Exp/Cntr=0.3,0.1

Type RM Length L Ch R = 1 ,30250   ,213.9,226,238
XS GIS Cut Line= 3
2160268.52726644427270.0006209522160201.32467658427236.399326022
2159958.17348781427232.122797576
#Sta/Elev= 30
       0 3057.18     6.8 3054.83    24.7 3050.19    63.5 3042.81    89.3  3036.8
   108.3 3033.72   116.3 3033.02   120.3 3031.89   124.3 3029.82   128.3 3026.14
   136.3  3016.3   140.3 3012.05   144.3 3009.02   150.2 3006.98   152.3 3006.41
   168.3 3006.75   185.6 3007.98   192.3 3007.56   196.3 3006.66   208.3 3007.02
   212.3 3007.77   216.3  3009.3   232.3 3018.17   236.7 3020.05   244.1 3025.33
   256.3 3035.88   264.4  3041.4   296.3 3058.62   312.3 3066.68   318.3 3070.73
#Mann= 3 ,-1,0
       0      .1       0   150.2    .045       0   168.3      .1       0
Bank Sta=150.2,168.3
XS Rating Curve= 0 ,0
Exp/Cntr(USF)=0,0
Exp/Cntr=0.3,0.1

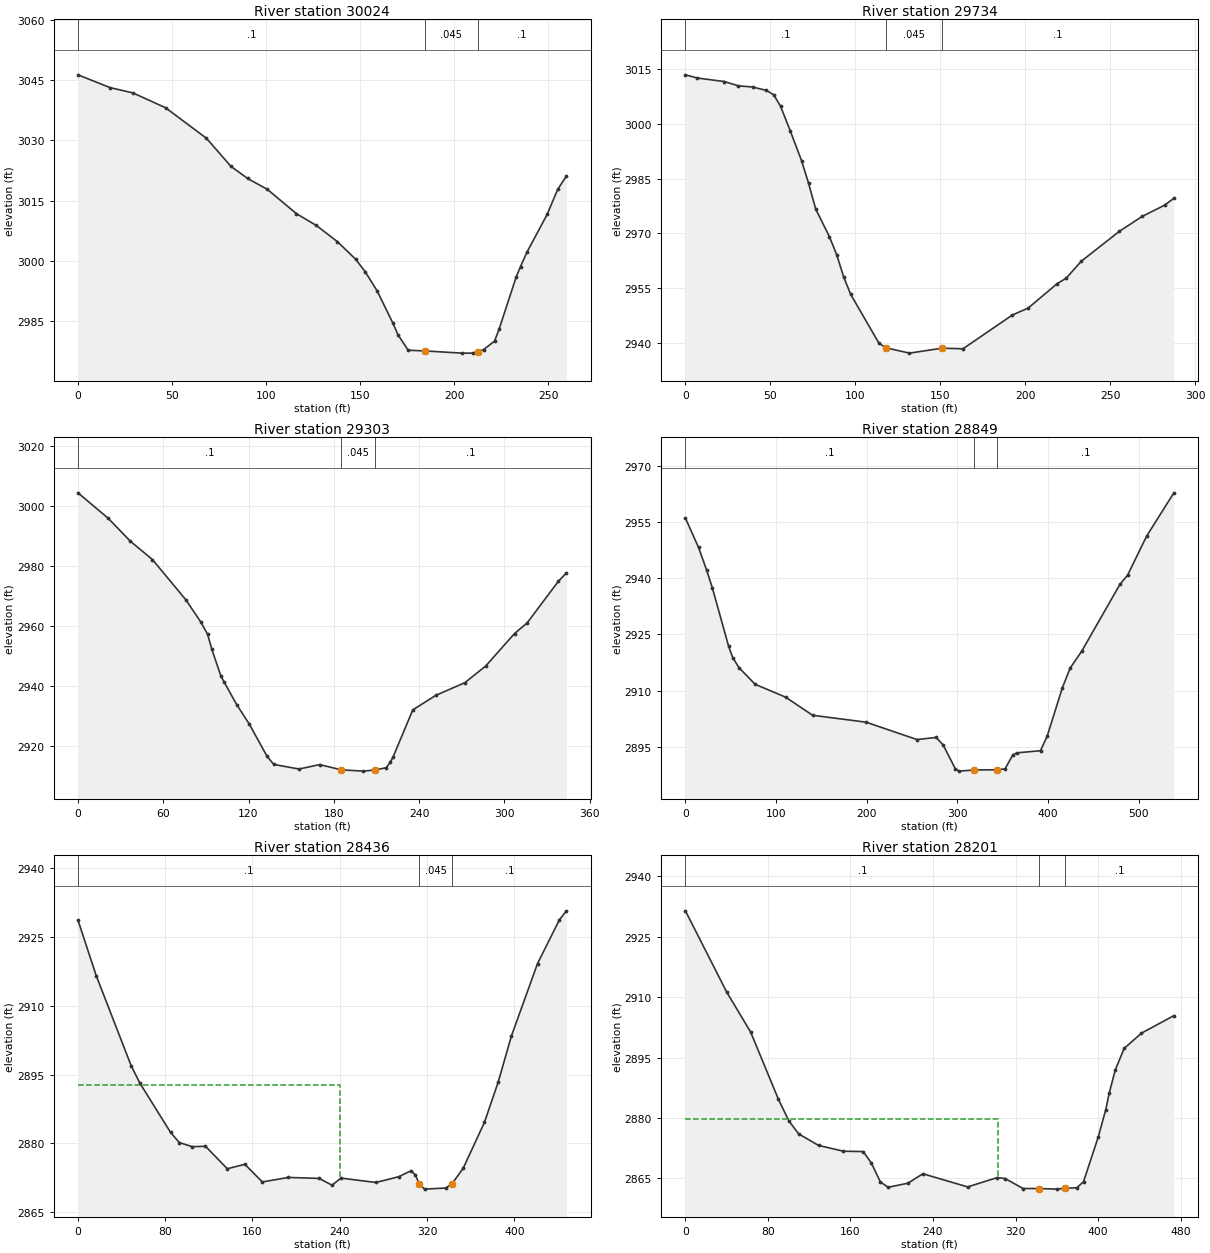
Type RM Length L Ch R = 1 ,30024   ,321.5,289.5,278.3
XS GIS Cut Line= 3
2160255.65944053427220.0015335072160200.50957106427090.657289567
2160117.54341073427005.428415784
#Sta/Elev= 30
       0 3046.35      17 3043.17    29.3 3041.83    46.6 3038.14    68.3 3030.54
    81.3 3023.55    90.2 3020.53   100.7  3017.8   116.1 3011.77   126.7 3008.82
   137.9 3004.79   147.6 3000.41   152.6 2997.33   158.9 2992.62   167.4 2984.48
   170.2 2981.51   175.5 2977.75   184.3 2977.58   204.1 2977.03   209.8 2977.03
   212.6 2977.43   215.6 2977.91   221.4 2980.03   223.9 2983.11   232.8 2995.87
   235.2  2998.6   238.6 3002.16   249.4 3011.63     255 3017.86   259.6 3021.14
#Mann= 3 ,-1,0
       0      .1       0   184.3    .045       0   212.6      .1       0
Bank Sta=184.3,212.6
XS Rating Curve= 0 ,0
Exp/Cntr(USF)=0,0
Exp/Cntr=0.3,0.1

Type RM Length L Ch R = 1 ,29734   ,398.9,431.4,451.4
XS GIS Cut Line= 3
2160486.38406436426816.0536713312160304.84853849426863.161843244
2160215.46629999426907.891303711
#Sta/Elev= 30
       0 3013.49     7.1 3012.61    22.9 3011.65    31.2 3010.47    39.5 3010.16
    47.7 3009.21      52 3008.02      56 3004.88    61.8 2998.03    68.4 2989.92
    72.5 2983.74    76.7  2976.7    84.8 2969.08    89.1 2964.11    93.2 2958.02
    97.3 2953.29   113.9 2939.93     118 2938.65   131.9 2937.19   151.1 2938.55
   163.4 2938.38   192.5 2947.66   201.7 2949.52   218.9 2956.27   224.1 2957.72
     233 2962.38   255.4 2970.57   268.8 2974.66     282 2977.74   287.5 2979.63
#Mann= 3 ,-1,0
       0      .1       0     118    .045       0   151.1      .1       0
Bank Sta=118,151.1
XS Rating Curve= 0 ,0
Exp/Cntr(USF)=0,0
Exp/Cntr=0.3,0.1

Type RM Length L Ch R = 1 ,29303   ,463.5,454.5,438.1
XS GIS Cut Line= 2
2160563.01950652426747.5119723552160387.03479737 426452.31181507
#Sta/Elev= 30
       0 3004.32    21.3 2995.82    36.8 2988.21    52.4 2982.07    75.9 2968.66
    86.5  2961.2    91.2 2957.17    94.2 2952.14   100.5 2943.32     103 2941.08
   111.7  2933.7   120.5 2927.24   133.1 2916.42   137.8 2913.75   155.5 2912.22
   170.1  2913.7   185.2 2911.95   200.8 2911.52   208.7 2911.89   216.9 2912.65
   219.7 2914.47   221.6  2916.1   235.6 2931.95   251.8 2936.79   272.2    2941
   286.8 2946.53   307.2 2957.41     316  2960.9     338 2974.81   343.7 2977.63
#Mann= 3 ,-1,0
       0      .1       0   185.2    .045       0   208.7      .1       0
Bank Sta=185.2,208.7
XS Rating Curve= 0 ,0
Exp/Cntr(USF)=0,0
Exp/Cntr=0.3,0.1

Type RM Length L Ch R = 1 ,28849   ,416.2,412.9,406.8
XS GIS Cut Line= 3
2161061.16977194426507.6618445612160997.30435329426382.769470325
2160619.78876753426255.038633038
#Sta/Elev= 30
       0 2956.04    14.5 2948.19    23.4 2942.16    29.7 2937.44    47.7 2921.81
    52.2 2918.82    59.1 2916.12    76.9 2911.69   110.6 2908.25   140.3 2903.42
   199.2 2901.58   255.5 2896.94   276.6 2897.51   284.4 2895.47   297.7 2889.16
   301.9 2888.52   318.8 2888.83   343.8 2888.88   352.6 2889.12     361 2892.78
   365.3 2893.39   391.7 2893.97   399.1 2897.86   415.9 2910.82   424.4    2916
   437.1 2920.49   479.3 2938.33   487.7 2940.77   508.8 2951.23   538.8 2962.76
#Mann= 3 ,-1,0
       0      .1       0   318.8    .045       0   343.8      .1       0
Bank Sta=318.8,343.8
XS Rating Curve= 0 ,0
Exp/Cntr(USF)=0,0
Exp/Cntr=0.3,0.1

Type RM Length L Ch R = 1 ,28436   ,224.4,234.8,245.2
XS GIS Cut Line= 2
2161160.93777432425929.0076577882160713.75211298425906.016107076
#Sta/Elev= 30
       0 2928.69    16.8 2916.54    48.8  2896.9    56.8  2893.1    84.9 2882.36
    92.9 2880.15   104.9 2879.24   116.9 2879.34   136.9 2874.43     153  2875.4
     169 2871.55     193 2872.53   221.1 2872.32   232.9 2870.84   241.1 2872.39
   273.1 2871.43   293.9 2872.68   305.2 2873.97   309.2 2873.13   312.9 2871.12
   317.7 2869.98   337.2 2870.22     343 2871.16   353.2 2874.56   372.6 2884.54
   385.3 2893.39   397.3 2903.35   421.3 2919.22   441.3 2928.75   447.8 2930.73
#Mann= 3 ,-1,0
       0      .1       0   312.9    .045       0     343      .1       0
#XS Ineff= 2 , 0
           240.1 2892.67
Permanent Ineff=
       F       F
Bank Sta=312.9,343
XS Rating Curve= 0 ,0
Exp/Cntr(USF)=0,0
Exp/Cntr=0.3,0.1

Type RM Length L Ch R = 1 ,28201   ,243,248.9,272.3
XS GIS Cut Line= 3
2161176.43704636425901.5454192282161109.78717075 425836.06483968
2160794.07723364425624.422252213
#Sta/Elev= 30
       0 2931.46      40 2911.29    63.3 2901.31    90.1 2884.68   100.2 2879.29
   109.8 2876.03   129.1 2873.16   153.2 2871.72   172.4 2871.63   180.3 2868.77
   188.9 2864.13   196.5 2862.75   215.8 2863.78   230.2 2866.12   273.6 2862.85
   302.4 2865.18     310 2864.93   327.3 2862.45   342.9 2862.45   360.2  2862.3
   367.7 2862.51   379.5 2862.64     386 2864.18   400.3 2875.35   407.5 2882.08
   410.9 2886.23   416.7 2891.91   425.3 2897.26   442.1 2901.06   473.5 2905.41
#Mann= 3 ,-1,0
       0      .1       0   342.9    .045       0   367.7      .1       0
#XS Ineff= 2 , 0
          303.38 2879.68
Permanent Ineff=
       F       F
Bank Sta=342.9,367.7
XS Rating Curve= 0 ,0
Exp/Cntr(USF)=0,0
Exp/Cntr=0.3,0.1

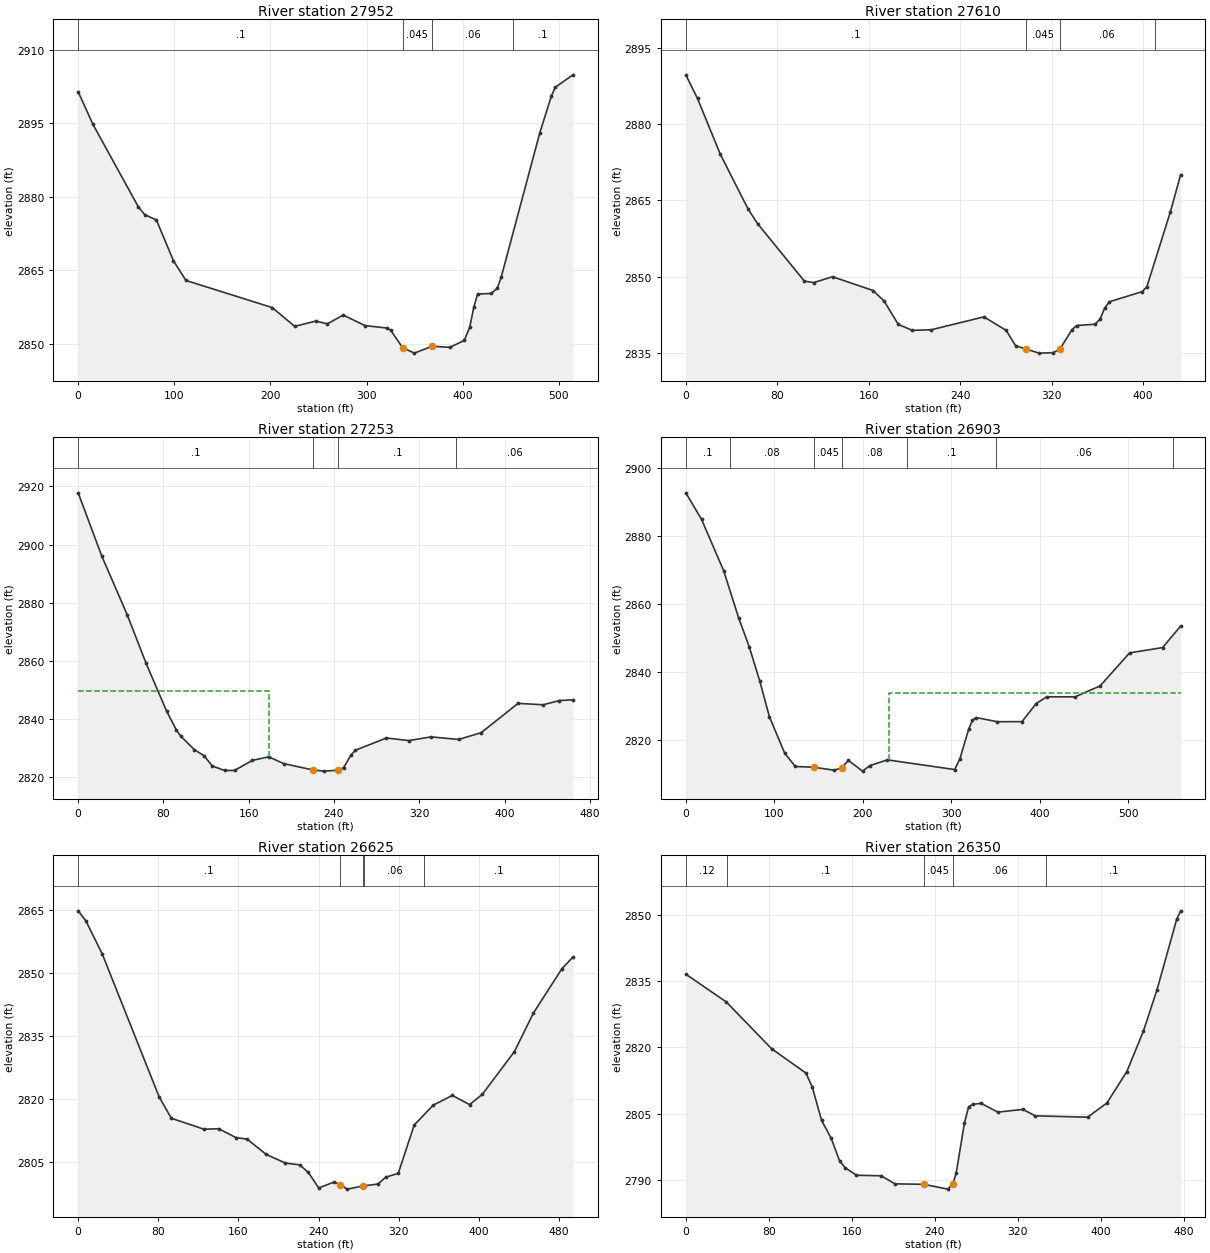
Type RM Length L Ch R = 1 ,27952   ,341.5,342.5,341.1
XS GIS Cut Line= 4
2161164.38650693425818.6482143722161105.75805262425748.523984701
2161025.28762513425407.0994566342161022.98847005425334.676071892
#Sta/Elev= 30
       0 2901.44    15.4 2894.78    62.7 2877.89    69.3 2876.34    81.4 2875.24
    99.1 2866.93   112.1  2862.9   201.7 2857.37   225.2 2853.53   246.9  2854.6
   259.2 2854.05   275.7 2855.83   298.4 2853.68   320.9 2853.19     325 2852.75
   337.3 2849.19   349.6 2848.06     368 2849.46   386.6 2849.24   401.5 2850.66
   407.2 2853.34   411.4 2857.39   415.4 2860.14   429.6 2860.24   435.9 2861.33
     440 2863.61   480.1 2893.07   492.1 2900.55   496.1 2902.35   514.6  2904.9
#Mann= 4 ,-1,0
       0      .1       0   337.3    .045       0     368     .06       0
  452.18      .1       0
Bank Sta=337.3,368
XS Rating Curve= 0 ,0
Exp/Cntr(USF)=0,0
Exp/Cntr=0.3,0.1

Type RM Length L Ch R = 1 ,27610   ,354.7,356.1,354.4
XS GIS Cut Line= 2
2161439.30882435425706.2808211682161342.74431136 425284.38586561
#Sta/Elev= 30
       0 2889.71    10.2 2885.06    30.2 2874.06    54.5 2863.29    62.7 2860.45
   103.7 2849.13   111.9 2848.85   128.3    2850   163.8 2847.28   173.5 2845.19
   185.8 2840.62   198.1 2839.45   214.5 2839.56   260.7  2842.1   280.2 2839.44
   288.4 2836.42   297.4 2835.79   308.9 2834.97   321.2 2835.06   327.2 2835.77
   337.6 2839.53   341.7  2840.4   358.1 2840.66   362.2 2841.63   366.3  2843.8
   370.4 2845.07   399.2 2847.07   403.3 2848.07   423.8 2862.76   432.8 2870.08
#Mann= 4 ,-1,0
       0      .1       0   297.4    .045       0   327.2     .06       0
     410      .1       0
Bank Sta=297.4,327.2
XS Rating Curve= 0 ,0
Exp/Cntr(USF)=0,0
Exp/Cntr=0.3,0.1

Type RM Length L Ch R = 1 ,27253   ,369.4,350.2,317.5
XS GIS Cut Line= 3
2161776.13504228425621.2120835352161676.12179668425301.629528643
2161556.56573298425252.197694613
#Sta/Elev= 30
       0 2917.78    22.3  2895.9    46.1 2875.77    63.8 2859.08      83 2842.66
    92.2 2836.15    96.4 2834.01     109 2829.45   118.1 2827.35   125.8 2823.84
   137.3 2822.27   146.7 2822.28   163.5 2825.76   178.8 2826.97   192.8 2824.63
   220.3 2822.46   230.6 2822.05   244.1 2822.36     249 2823.24   255.7 2827.44
   259.9 2829.21   289.2 2833.45   310.2 2832.56   331.1 2833.83     357 2832.94
   378.1 2835.29   412.7 2845.36   436.2 2844.87   451.5 2846.34   464.2 2846.58
#Mann= 4 ,-1,0
       0      .1       0   220.3    .045       0   244.1      .1       0
  354.87     .06       0
#XS Ineff= 2 , 0
          178.74  2849.7
Permanent Ineff=
       F       F
Bank Sta=220.3,244.1
XS Rating Curve= 0 ,0
Exp/Cntr(USF)=0,0
Exp/Cntr=0.3,0.1

Type RM Length L Ch R = 1 ,26903   ,272.1,278.6,286.3
XS GIS Cut Line= 3
2162103.76463992425178.6247323362161643.93362569425197.017972906
2161548.51869023425170.577689587
#Sta/Elev= 30
       0 2892.75    17.8  2884.9    42.8 2869.77    59.6 2855.98    71.6 2847.42
    83.7 2837.16    94.4 2826.79   111.7 2816.06   123.7 2812.12   144.5  2811.9
   167.9 2811.01   176.2 2811.77   183.7  2813.9   199.7 2810.75   207.8 2812.36
   227.8 2814.07   303.8 2811.21   309.7 2814.36   319.8 2823.24   323.8 2825.68
   327.9 2826.55   351.9 2825.31   379.9 2825.33   395.9 2830.67   407.9 2832.65
   439.9 2832.64   468.2 2835.87   501.5 2845.59   538.8 2847.16   559.2  2853.5
#Mann= 7 ,-1,0
       0      .1       0      50     .08       0   144.5    .045       0
   176.2     .08       0     250      .1       0     350     .06       0
   550.2      .1       0
#XS Ineff= 2 , 0
                          230.14         2833.64
Permanent Ineff=
       F       F
Bank Sta=144.5,176.2
XS Rating Curve= 0 ,0
Exp/Cntr(USF)=0,0
Exp/Cntr=0.3,0.1

Type RM Length L Ch R = 1 ,26625   ,280.1,274.6,262.8
XS GIS Cut Line= 3
2162111.81168267425061.3678237072162017.54632475425045.273738209
 2161683.0192619 424829.15316152
#Sta/Elev= 30
       0 2864.82     7.7 2862.43      24 2854.56    80.8 2820.46      93 2815.34
   125.6 2812.72   140.1 2812.84   157.4 2810.74   168.7 2810.35   187.7 2806.71
   206.8 2804.65   221.1 2804.22   229.8  2802.4   240.1 2798.71   255.8 2800.15
   261.4 2799.48   268.7 2798.43   284.7 2799.21   299.2 2799.64   306.8 2801.26
   319.5  2802.2   335.4 2813.72   354.4 2818.46   373.5 2820.79   390.7 2818.59
   403.4 2821.04   435.4 2831.23   454.4 2840.44     483 2851.06   493.9  2853.8
#Mann= 5 ,-1,0
       0      .1       0   261.4    .045       0   284.7      .1       0
  285.63     .06       0  345.63      .1       0
Bank Sta=261.4,284.7
XS Rating Curve= 0 ,0
Exp/Cntr(USF)=0,0
Exp/Cntr=0.3,0.1

Type RM Length L Ch R = 1 ,26350   ,468.3,474.5,490.1
XS GIS Cut Line= 3
2162187.68380002424778.5717499542162053.18322835424718.793718104
2161724.40405318424692.353434785
#Sta/Elev= 30
       0 2836.52    38.9 2830.28    82.6 2819.71   115.8  2814.2   121.9 2811.02
   130.8 2803.56   140.1 2799.47   148.2  2794.4   153.3 2792.88   164.5 2791.13
   188.3 2791.01   201.6 2789.19   229.4 2789.09   252.5    2788   257.3 2789.11
   260.6 2791.62   268.6 2802.98   272.6  2806.6   276.6 2807.14   284.6 2807.38
   300.7 2805.38   324.8    2806   336.8 2804.55   387.3 2804.24   405.9 2807.45
   425.1 2814.54   441.1 2823.69   454.2 2833.01   473.2 2848.95     477 2850.83
#Mann= 5 ,-1,0
       0     .12       0      40      .1       0   229.4    .045       0
   257.3     .06       0  347.19      .1       0
Bank Sta=229.4,257.3
XS Rating Curve= 0 ,0
Exp/Cntr(USF)=0,0
Exp/Cntr=0.3,0.1

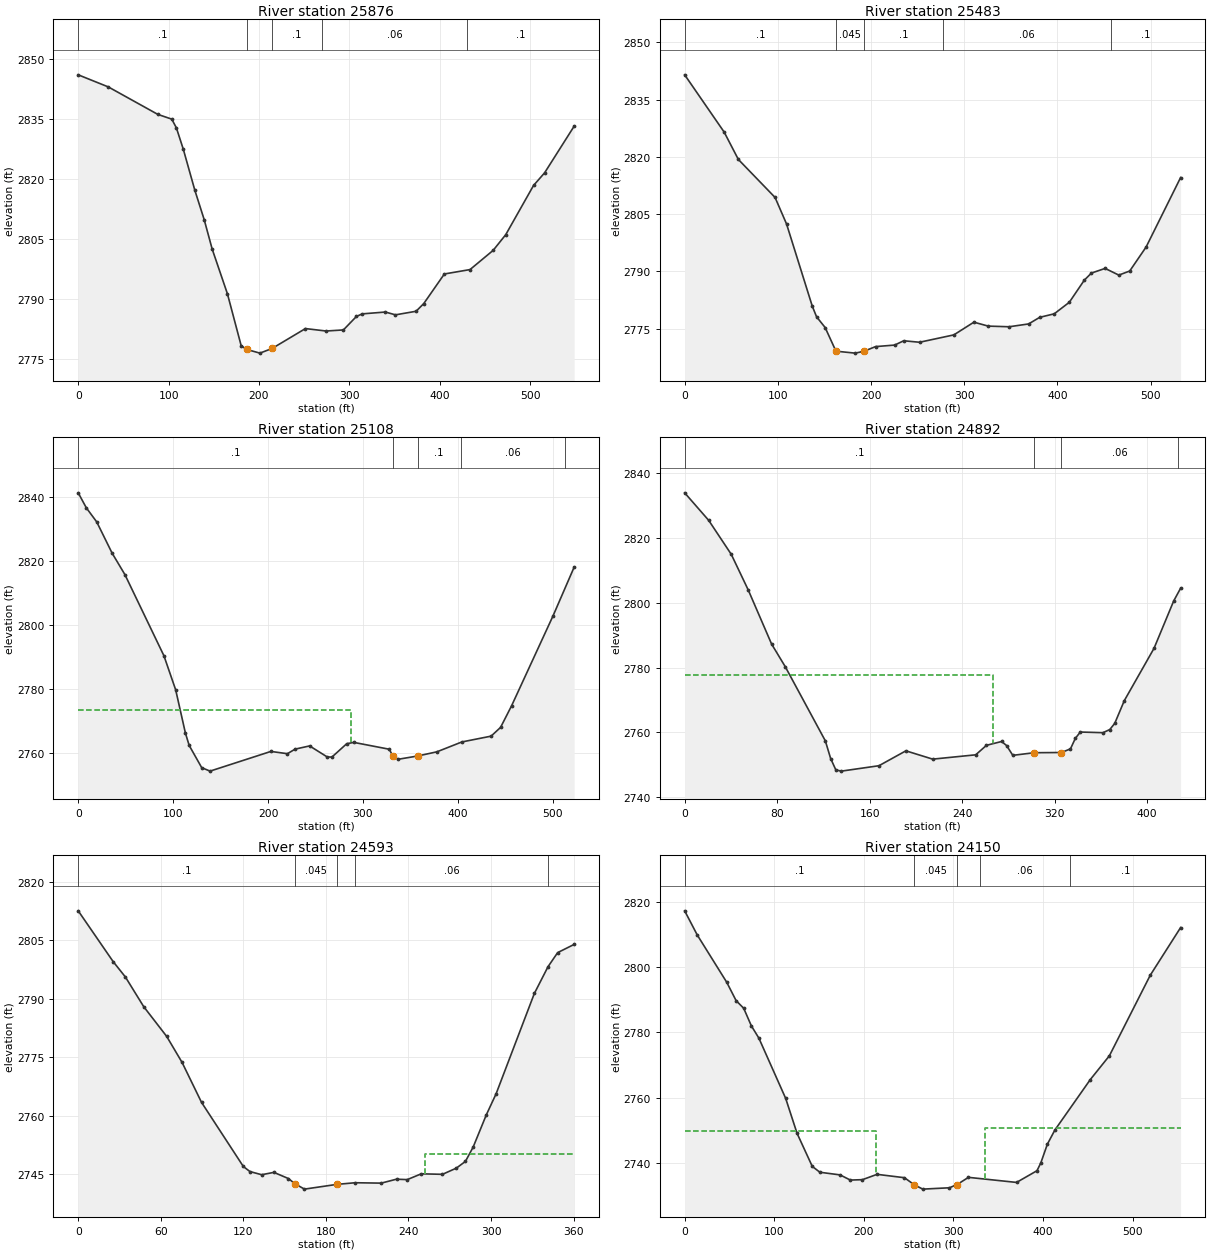
Type RM Length L Ch R = 1 ,25876   ,397.3,392.5,390.8
XS GIS Cut Line= 2
2162480.82607159424590.0410341192162053.18322835 424246.31735098
#Sta/Elev= 30
       0 2845.94    33.3 2842.92    88.1 2836.06   103.5 2834.88   108.6 2832.71
   116.3 2827.34   129.1 2817.07   139.4 2809.77   148.2 2802.45   165.1 2791.26
   180.3 2778.32   186.5 2777.38     201 2776.46   214.5 2777.62   251.4 2782.59
   274.2 2781.98   293.4 2782.25   307.8 2785.61   314.2 2786.26   339.8 2786.72
     351 2786.02   373.8 2786.91   382.3 2788.83   405.1 2796.22   433.5 2797.32
   459.1 2802.12     473 2806.03   503.8 2818.33     516 2821.47   548.7 2833.12
#Mann= 5 ,-1,0
       0      .1       0   186.5    .045       0   214.5      .1       0
     270     .06       0     430      .1       0
Bank Sta=186.5,214.5
XS Rating Curve= 0 ,0
Exp/Cntr(USF)=0,0
Exp/Cntr=0.3,0.1

Type RM Length L Ch R = 1 ,25483   ,374.4,375.4,375.5
XS GIS Cut Line= 3
2162715.33988885424293.4500299382162649.81396932424208.381292305
 2162280.7995804423998.008603294
#Sta/Elev= 30
       0 2841.51    42.4 2826.49    57.6 2819.33      97 2809.37   109.3 2802.42
   136.9 2780.89   141.5  2778.1   150.7 2775.29   162.3 2769.09   182.9 2768.58
   192.1 2769.04   204.8 2770.29   225.3 2770.69     235 2771.82     252 2771.43
   288.8 2773.36   310.3 2776.69   325.7 2775.66   348.1 2775.49     369 2776.23
   380.9 2777.96   396.5 2778.88   412.7 2781.91   428.8 2787.71   436.4 2789.56
   451.1 2790.78   465.8 2789.03   477.5  2790.1   495.1  2796.4   532.1  2814.6
#Mann= 5 ,-1,0
       0      .1       0   162.3    .045       0   192.1      .1       0
  277.38     .06       0  457.38      .1       0
Bank Sta=162.3,192.1
XS Rating Curve= 0 ,0
Exp/Cntr(USF)=0,0
Exp/Cntr=0.3,0.1

Type RM Length L Ch R = 1 ,25108   ,202.7,215.6,226.9
XS GIS Cut Line= 3
2163070.55934734424054.3379025382162979.74272203423971.568319976
2162637.16861643423765.793941107
#Sta/Elev= 30
       0 2841.45     8.6 2836.72    19.5 2832.34    35.7 2822.56    49.2 2815.83
    90.3 2790.41   102.7 2779.71   112.9 2766.23   116.9 2762.31   130.1 2755.35
   138.9 2754.26     203 2760.43   220.4 2759.72   228.5 2761.15   243.8 2762.16
   262.4 2758.69   267.3 2758.67   282.9 2762.85   290.4 2763.26   327.7 2761.12
   331.3 2759.08     337 2757.97   357.5 2758.99   377.9 2760.31   404.2  2763.4
     435 2765.22     445 2767.97   456.6 2774.74   500.4    2803   522.5 2818.17
#Mann= 5 ,-1,0
       0      .1       0   331.3    .045       0   357.5      .1       0
  402.88     .06       0  512.88      .1       0
#XS Ineff= 2 , 0
          287.72 2773.54
Permanent Ineff=
       F       F
Bank Sta=331.3,357.5
XS Rating Curve= 0 ,0
Exp/Cntr(USF)=0,0
Exp/Cntr=0.3,0.1

Type RM Length L Ch R = 1 ,24892   ,302.8,298.6,285
XS GIS Cut Line= 3
2163196.91775001423915.7454403712162966.91448748423779.810385873
2162911.73654901423627.572757962
#Sta/Elev= 30
       0 2833.91    20.8 2825.41    40.3 2814.94      55 2803.94    75.2 2787.26
    87.1 2780.23   121.7  2757.4   126.3 2751.95   130.8 2748.43   135.6 2748.06
   168.1 2749.73   191.4 2754.32   214.6 2751.76   251.8 2753.09   261.1 2756.02
   274.2  2757.2   278.5 2755.96   283.9 2752.93   302.42753.736     3262753.804
   333.8 2754.93     338 2758.16   342.3 2760.12   361.9 2759.92   367.8 2760.88
   372.1 2762.79   380.4 2769.82   406.1 2785.95   423.1 2800.55   429.1 2804.49
#Mann= 4 ,-1,0
       0      .1       0   302.4    .045       0     326     .06       0
  427.17      .1       0
#XS Ineff= 2 , 0
          266.67 2777.82
Permanent Ineff=
       F       F
Bank Sta=302.4,326
XS Rating Curve= 0 ,0
Exp/Cntr(USF)=0,0
Exp/Cntr=0.3,0.1

Type RM Length L Ch R = 1 ,24593   ,428.3,443.3,452.9
XS GIS Cut Line= 2
2163346.45889979423775.4057557532163095.87090811423516.433779218
#Sta/Elev= 30
       0  2812.6    25.4 2799.56    34.3 2795.61    47.6    2788    64.3 2780.36
    75.5 2773.67    89.6 2763.44     120 2746.97   124.8 2745.67   133.3 2744.86
   142.2 2745.46   152.8 2743.87   157.42742.564   164.4 2741.16   187.82742.369
   201.2  2742.8   220.2  2742.7   231.3 2743.71   239.1  2743.6   249.3 2745.09
   264.7 2744.96   274.8 2746.55   281.4 2748.28     287 2751.95   296.6 2760.25
   303.7 2765.65   331.5 2791.41   341.4 2798.25   348.4 2801.87   360.4 2803.98
#Mann= 5 ,-1,0
       0      .1       0   157.4    .045       0   187.8      .1       0
   201.2     .06       0   341.4      .1       0
#XS Ineff= 2 , 0
                           252.1         2750.29
Permanent Ineff=
       F       F
Bank Sta=157.4,187.8
XS Rating Curve= 0 ,0
Exp/Cntr(USF)=0,0
Exp/Cntr=0.3,0.1

Type RM Length L Ch R = 1 ,24150   ,359.9,348.8,341
XS GIS Cut Line= 2
2163576.03230427 423643.209219812163388.69374292423122.351249985
#Sta/Elev= 30
       0 2817.19      14 2809.82    46.9 2795.37    57.4 2789.74    65.9 2787.39
    74.4 2782.04    82.8 2778.28   112.7 2759.87   125.4 2749.19   142.4 2739.07
   150.9 2737.28   173.4 2736.47   184.9 2734.89   198.4 2735.01   214.7 2736.64
   245.3 2735.61   255.9 2733.51   265.7 2732.12   295.4 2732.53     304 2733.51
   316.7 2735.72   370.4 2734.17   393.2 2737.75   397.5 2740.16   404.8 2745.87
   413.2  2750.2   452.7 2765.61     474 2772.88   519.6  2797.5   553.5 2812.08
#Mann= 5 ,-1,0
       0      .1       0   255.9    .045       0     304      .1       0
     330     .06       0     430      .1       0
#XS Ineff= 2 , 0
          213.16 2749.99  334.77         2750.77
Permanent Ineff=
       F       F
Bank Sta=255.9,304
XS Rating Curve= 0 ,0
Exp/Cntr(USF)=0,0
Exp/Cntr=0.3,0.1