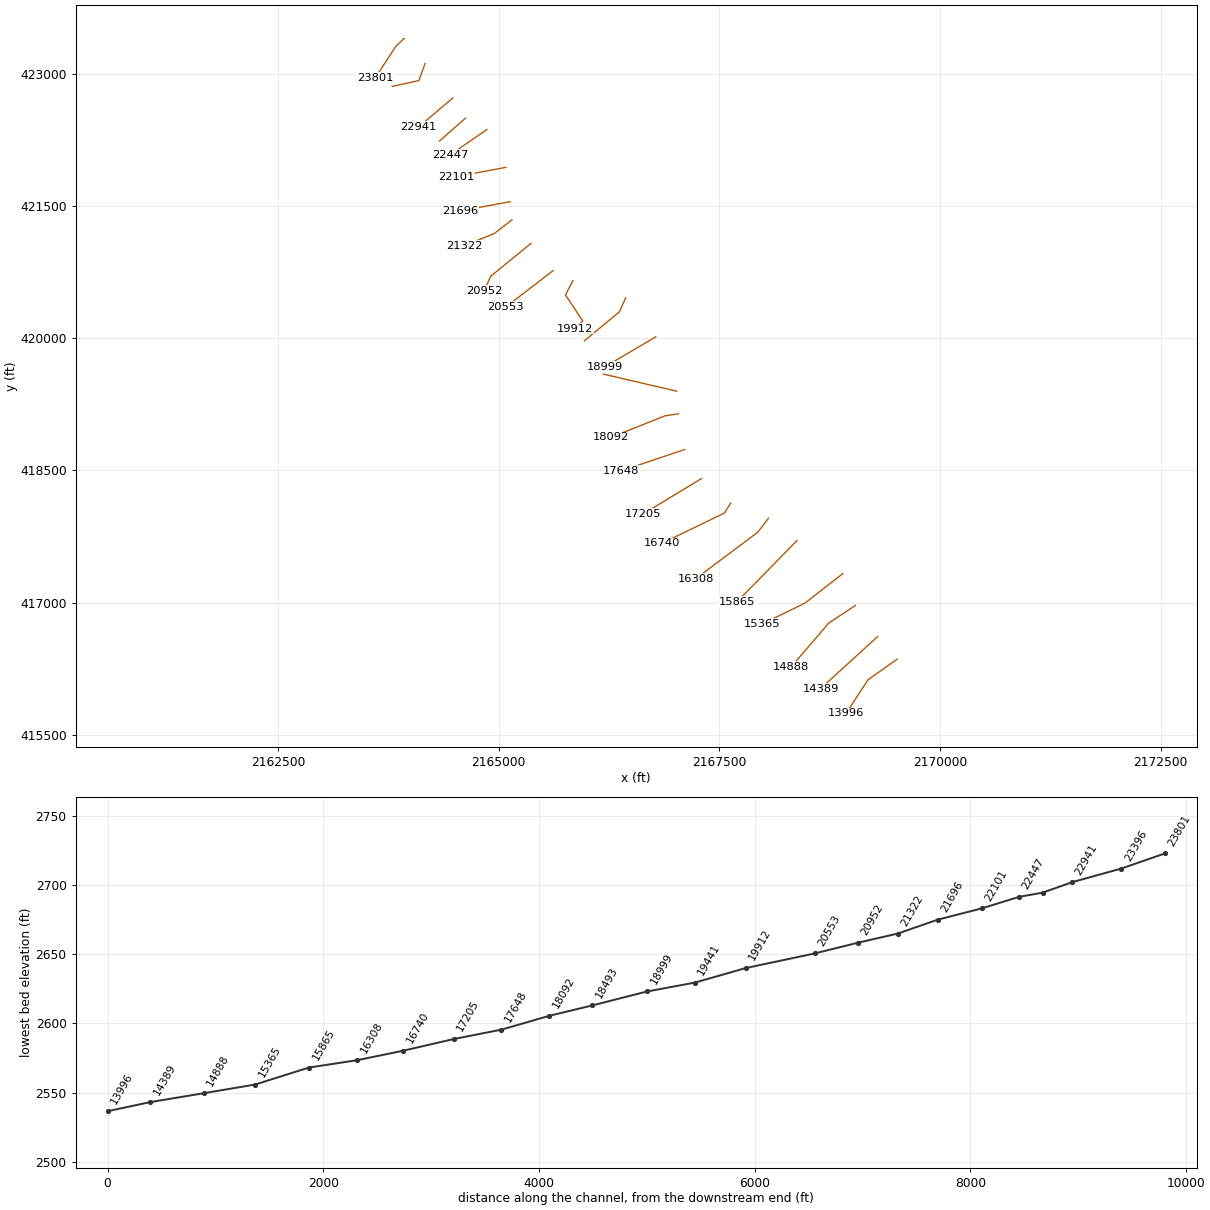
HEC-RAS study HLLSCK.prj: HLLSCK

--- HLLSCK.g01 (geometry) --- (continued)

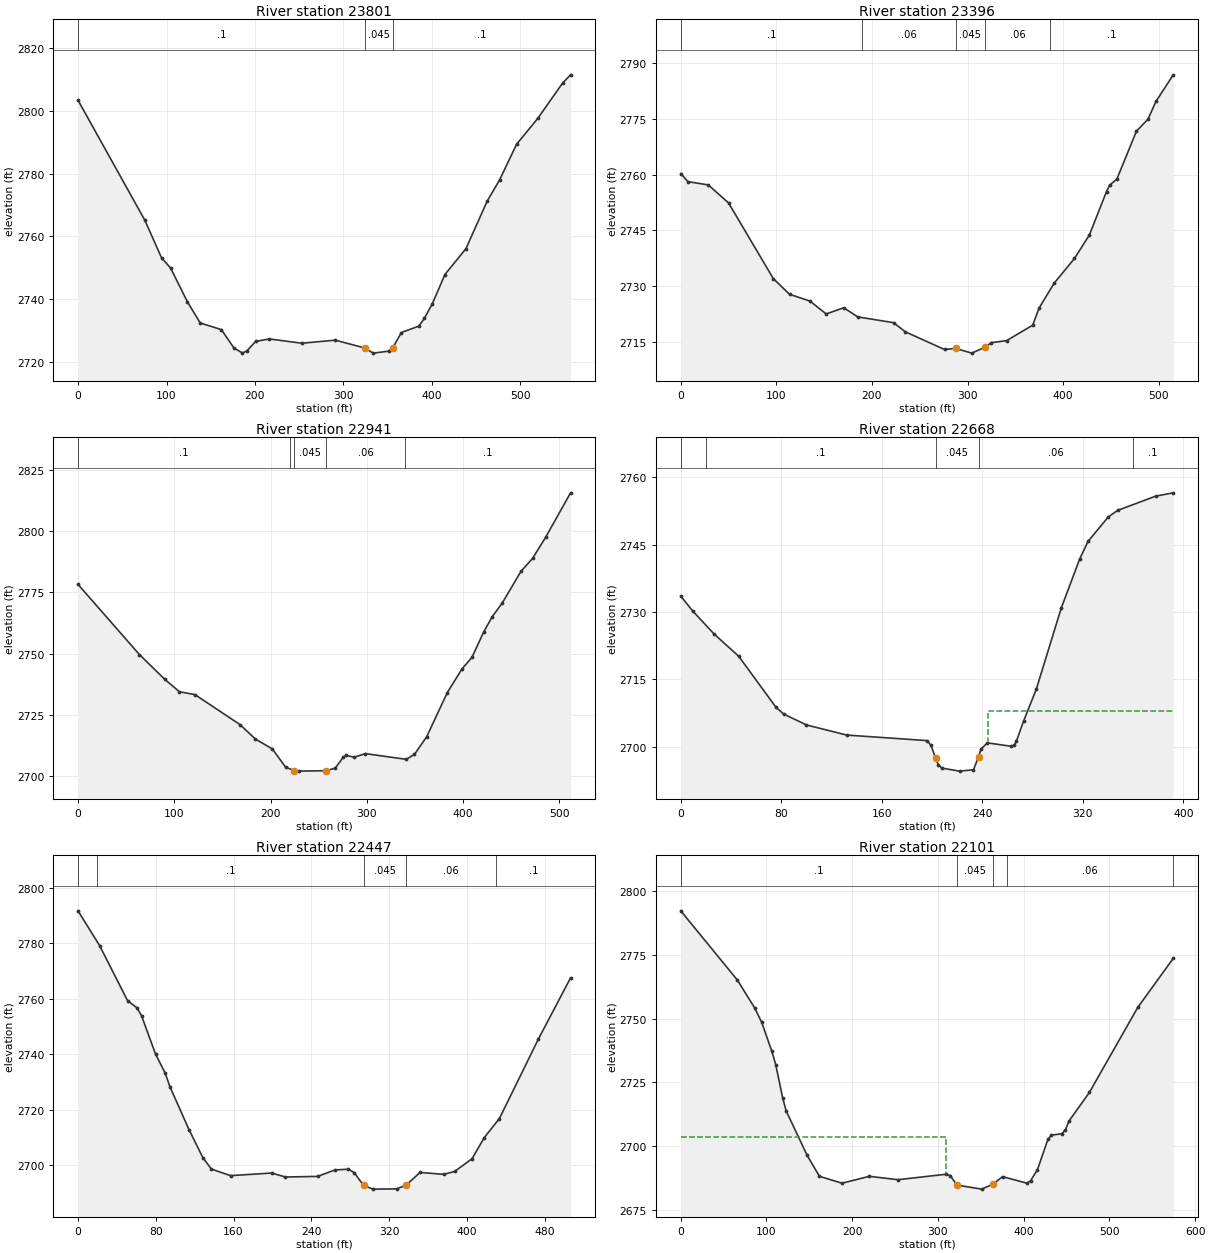
Type RM Length L Ch R = 1 ,23801   ,417.3,405.2,386.1
XS GIS Cut Line= 3
2163929.89164104423401.0698496112163834.09351308423310.380955137
2163602.90069759422954.011919108
#Sta/Elev= 30
       0 2803.33    75.5 2765.16    94.5 2753.13   104.6 2749.96   123.5 2739.27
   138.1 2732.46     162 2730.35   176.3 2724.47   185.8 2722.93   190.6  2723.5
   200.7  2726.6   216.3 2727.38     253 2726.02   290.7    2727   324.1 2724.51
   333.6 2722.87   351.1 2723.49   355.9 2724.62   365.5 2729.43   385.3 2731.47
   391.6    2734   400.4 2738.52   414.7 2747.89   438.5 2756.13   462.3 2771.15
   476.6 2778.05   495.7 2789.33   519.6 2797.55   547.7 2808.79   556.7 2811.43
#Mann= 3 ,-1,0
       0      .1       0   324.1    .045       0   355.9      .1       0
Bank Sta=324.1,355.9
XS Rating Curve= 0 ,0
Exp/Cntr(USF)=0,0
Exp/Cntr=0.3,0.1

Type RM Length L Ch R = 1 ,23396   ,447.1,455.3,465.6
XS GIS Cut Line= 3
2164166.19369002423116.2300824622164095.94172952422922.079209786
2163794.49695352422855.659174397
#Sta/Elev= 30
       0  2760.3     7.5 2758.11    28.8 2757.24      50 2752.39    96.8 2732.02
   113.8 2727.77   135.1 2725.97   152.1 2722.49   170.5 2724.15   185.1  2721.7
   222.6 2720.14   234.9 2717.67   275.9 2712.92   287.6 2713.21   304.4 2711.94
   317.8 2713.49     325 2714.77   340.8  2715.3   368.1 2719.46   374.8 2724.08
   390.5 2730.76   411.8 2737.43   427.4 2743.75   445.3 2755.44   448.7  2757.2
   456.1 2758.78   476.6  2771.7   488.7 2774.94     497  2779.7   515.1 2786.88
#Mann= 5 ,-1,0
       0      .1       0     190     .06       0   287.6    .045       0
   317.8     .06       0  386.47      .1       0
Bank Sta=287.6,317.8
XS Rating Curve= 0 ,0
Exp/Cntr(USF)=0,0
Exp/Cntr=0.3,0.1

Type RM Length L Ch R = 1 ,22941   ,272.4,273,273.5
XS GIS Cut Line= 2
 2164480.9224731422724.862797015  2164090.066111422394.934044304
#Sta/Elev= 30
       0 2778.26    63.8 2749.62      90 2739.57   105.3 2734.47   121.4 2733.31
   168.5    2721   184.2 2715.17   201.8 2711.15   215.6  2703.7   224.5  2702.3
     229 2702.09   257.5 2702.26   267.1 2703.29   275.6 2707.86   278.4 2708.47
     287 2707.81   298.4 2709.23   340.9  2706.9   349.4 2708.91   362.2  2716.2
   383.5 2734.13   398.8  2743.8   409.1  2748.5   421.2 2758.79   430.2 2765.14
   440.3 2770.52   460.1 2783.64   472.1 2788.89   485.7 2797.54   511.5 2815.63
#Mann= 5 ,-1,0
       0      .1       0     220     .06       0   224.5    .045       0
   257.5     .06       0     340      .1       0
Bank Sta=224.5,257.5
XS Rating Curve= 0 ,0
Exp/Cntr(USF)=0,0
Exp/Cntr=0.3,0.1

Type RM Length L Ch R = 1 ,22668   ,223.5,220.6,216.8
XS GIS Cut Line= 2
2164623.10258086 422495.445197682164329.33157953422235.842530351
#Sta/Elev= 30
       0 2733.56     9.5 2730.25    26.4 2725.15    46.2 2720.13    75.9 2708.74
      82 2707.26   100.1 2704.84     132 2702.59   196.1 2701.35   199.2 2700.28
   202.8  2697.5   204.9    2696   207.7 2695.23   221.9 2694.55     233 2694.85
   237.1 2697.79     239 2699.48   244.1 2700.85   263.2 2700.08   265.5 2700.38
   267.2 2701.24   272.9 2705.72     283  2712.8   302.8 2730.84   317.5  2741.8
   324.2 2745.75   340.2 2751.17   347.7 2752.65   377.9 2755.82     392 2756.57
#Mann= 5 ,-1,0
       0     .12       0      20      .1       0   202.8    .045       0
   237.1     .06       0     360      .1       0
#XS Ineff= 2 , 0
                          244.76         2707.85
Permanent Ineff=
       F       F
Bank Sta=202.8,237.1
XS Rating Curve= 0 ,0
Exp/Cntr(USF)=0,0
Exp/Cntr=0.3,0.1

Type RM Length L Ch R = 1 ,22447   ,356.3,346.3,334.4
XS GIS Cut Line= 2
2164866.03094752422366.194605914 2164448.7343021422078.800222019
#Sta/Elev= 30
       0 2791.76    22.2 2779.21      51 2759.36    60.5 2756.84    65.3 2753.98
    79.7 2740.14    89.7 2733.25    94.5 2728.37   114.2 2712.86   128.5 2702.73
   137.2 2698.67   156.9  2696.3   199.3 2697.24   213.4 2695.81   246.5 2696.03
   264.5 2698.38   278.2 2698.61     284 2697.42   293.7 2692.81   303.4 2691.44
   327.7 2691.52   337.4 2692.82   351.9 2697.46   376.2 2696.76   387.5 2697.82
   405.4 2702.42   417.9    2710   433.5 2716.88   473.7  2745.6   506.7 2767.58
#Mann= 5 ,-1,0
       0     .12       0      20      .1       0   293.7    .045       0
   337.4     .06       0     430      .1       0
Bank Sta=293.7,337.4
XS Rating Curve= 0 ,0
Exp/Cntr(USF)=0,0
Exp/Cntr=0.3,0.1

Type RM Length L Ch R = 1 ,22101   ,405.3,404.9,402.3
XS GIS Cut Line= 2
2165081.00194667421937.402185143 2164516.5593767421830.491474334
#Sta/Elev= 30
       0 2792.32      66 2765.19    86.3 2754.19    94.5 2748.53   106.2 2737.27
   110.8 2731.99   118.9 2718.93     123  2713.8   147.4  2696.4   161.8 2688.15
   188.1 2685.44     220 2688.14   253.3 2686.82     309 2688.94   314.3 2688.46
   322.2  2684.7     351 2683.12   363.7 2684.96   375.4 2688.02   403.9 2685.44
     408 2686.37   416.1 2690.75   428.3 2702.65   432.4 2704.31   444.6 2704.85
   448.7 2706.33   452.7 2709.75   476.7 2721.07   533.1 2754.41   574.5 2773.67
#Mann= 5 ,-1,0
       0      .1       0   322.2    .045       0   363.7      .1       0
     380     .06       0  574.48      .1       0
#XS Ineff= 2 , 0
          309.57 2703.39
Permanent Ineff=
       F       F
Bank Sta=322.2,363.7
XS Rating Curve= 0 ,0
Exp/Cntr(USF)=0,0
Exp/Cntr=0.3,0.1

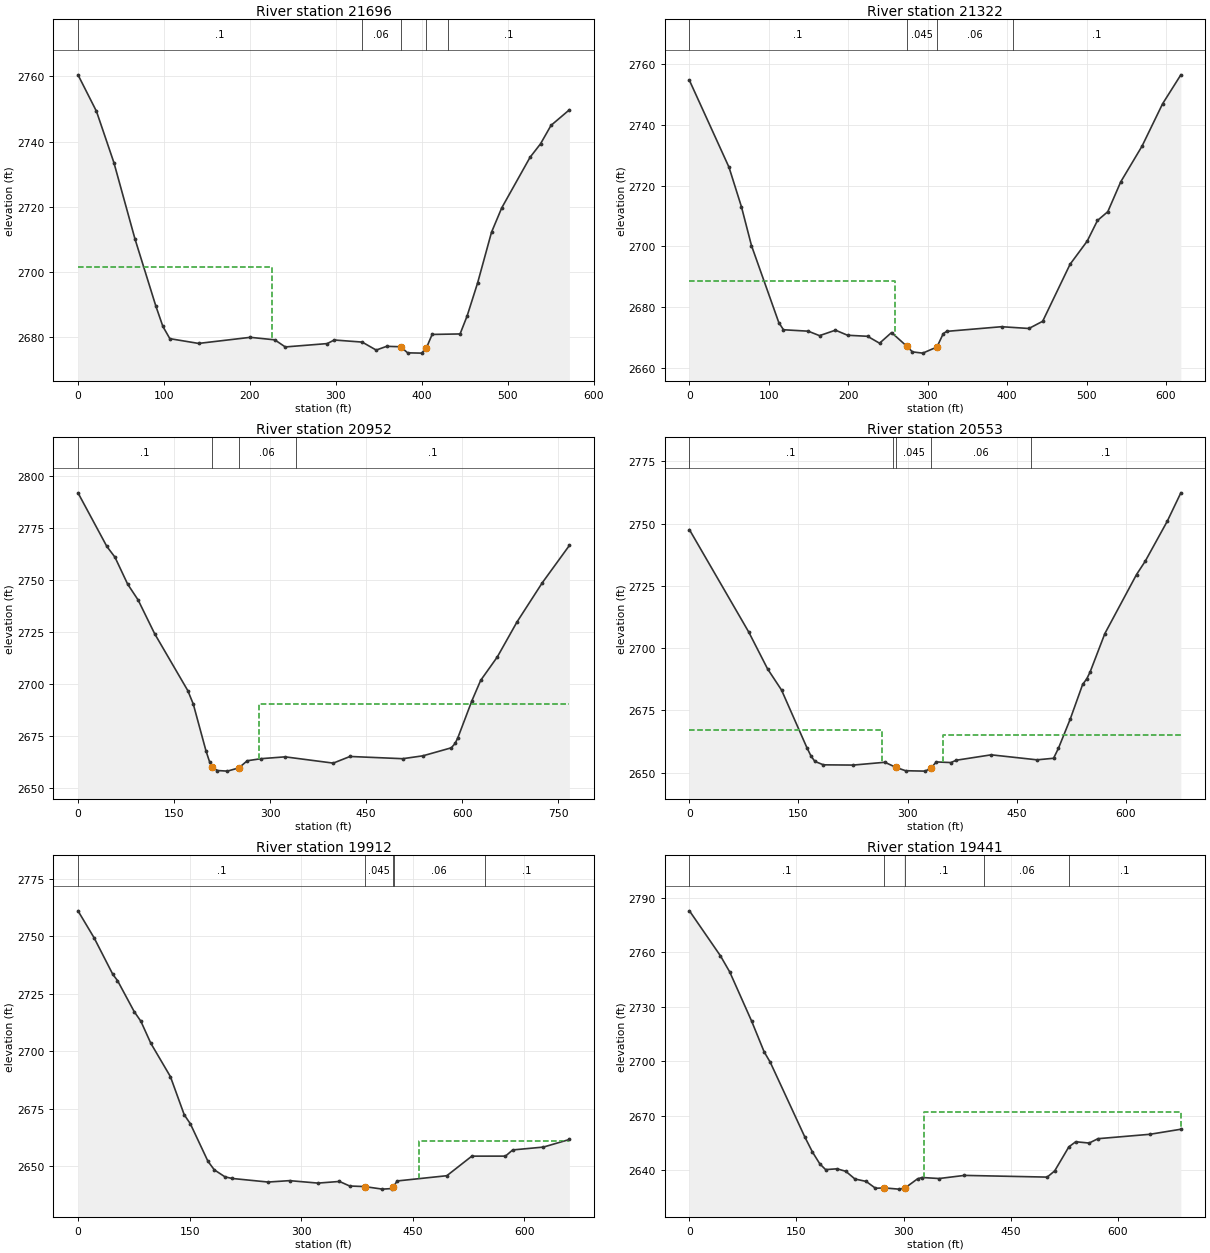
Type RM Length L Ch R = 1 ,21696   ,368,374.4,374
XS GIS Cut Line= 2
2165129.28420317421547.6954005812164567.14078827421443.083844843
#Sta/Elev= 30
       0 2760.48    21.5 2749.28    41.8 2733.52    66.2 2710.19    90.6 2689.48
    98.8 2683.22   106.9 2679.47   140.3 2678.01   200.5 2679.88     229 2679.11
   241.2 2676.93     290 2677.96   298.2 2679.06   330.7 2678.42     347 2675.97
   359.2 2677.12   375.4 2676.99   383.6 2675.12   399.9 2675.03   405.42676.623
   412.1 2680.77   444.6 2680.92   452.8 2686.44     465 2696.58   481.2 2712.16
   493.1 2719.64     526 2735.15   538.2 2739.29   550.4 2744.95   571.8 2749.74
#Mann= 5 ,-1,0
       0      .1       0     330     .06       0   375.4    .045       0
   405.4     .06       0     430      .1       0
#XS Ineff= 2 , 0
          226.09 2701.48
Permanent Ineff=
       F       F
Bank Sta=375.4,405.4
XS Rating Curve= 0 ,0
Exp/Cntr(USF)=0,0
Exp/Cntr=0.3,0.1

Type RM Length L Ch R = 1 ,21322   ,366.4,369.7,379.6
XS GIS Cut Line= 3
  2165150.085314421341.052441139  2164946.129637421184.473936696
2164610.82473462421048.778750139
#Sta/Elev= 30
       0 2754.64    49.8 2726.08    65.5 2713.05    78.1 2700.32   112.5 2674.99
   118.4 2672.61   149.6 2672.14   163.8 2670.67   183.9 2672.47   199.1  2670.8
   224.3 2670.46   239.4 2668.18   254.5 2671.69     274 2667.12   280.8 2665.33
   293.8 2664.92   311.72666.939   319.6 2671.34     324 2672.08     393 2673.61
   427.5 2673.03   444.8  2675.4   479.3 2694.15   500.9 2701.78   513.8 2708.55
   526.8 2711.44   543.1 2721.26   569.9    2733   595.8 2746.94   618.8 2756.47
#Mann= 4 ,-1,0
       0      .1       0     274    .045       0   311.7     .06       0
  407.13      .1       0
#XS Ineff= 2 , 0
          259.03 2688.77
Permanent Ineff=
       F       F
Bank Sta=274,311.7
XS Rating Curve= 0 ,0
Exp/Cntr(USF)=0,0
Exp/Cntr=0.3,0.1

Type RM Length L Ch R = 1 ,20952   ,397.9,399.3,397.7
XS GIS Cut Line= 3
2165364.90762975421073.696756768 2164909.3343101420701.858097111
2164835.53427078420538.646471689
#Sta/Elev= 30
       0 2791.75    45.1 2766.02    57.7  2760.9    77.6 2747.93    93.9 2740.35
   119.7 2724.18   171.5 2696.87     180 2690.45   199.9 2667.94   205.6 2662.61
   209.6 2660.09   217.8 2658.58   233.3 2658.29   251.1 2659.85   264.3 2663.26
   285.5 2664.25   323.4 2665.14   398.5 2662.13   424.7 2665.32   506.9 2664.25
   538.5 2665.63   582.8 2669.47   588.8 2671.58   593.2  2674.4   615.1 2692.12
   628.7 2701.83   654.7 2713.06   685.4 2729.83   724.9 2748.63   767.2 2766.52
#Mann= 4 ,-1,0
       0      .1       0   209.6    .045       0   251.1     .06       0
     340      .1       0
#XS Ineff= 2 , 0
                           282.9         2690.49
Permanent Ineff=
       F       F
Bank Sta=209.6,251.1
XS Rating Curve= 0 ,0
Exp/Cntr(USF)=0,0
Exp/Cntr=0.3,0.1

Type RM Length L Ch R = 1 ,20553   ,601.9,640.9,679
XS GIS Cut Line= 2
2165617.42571301420766.3367639452165081.27158119420354.584407808
#Sta/Elev= 30
       0  2747.6    81.6 2706.45   107.5 2691.65   126.7 2683.15   161.5 2660.05
   167.2 2656.65   172.6 2654.47   184.3  2653.1   225.2    2653   268.9 2654.13
   284.3 2652.04   297.4 2650.73   324.4 2650.57   332.6 2651.89   339.5 2654.27
   359.7 2654.01   366.9 2654.94   415.1 2657.12   478.1 2655.11   500.9 2655.74
   507.6 2659.74   523.8 2671.46   540.9 2685.41   546.6 2687.67   551.3  2690.5
   571.5 2705.87     615 2729.56     627 2734.93   657.2 2750.93     676 2762.41
#Mann= 5 ,-1,0
       0      .1       0     280     .06       0   284.3    .045       0
   332.6     .06       0     470      .1       0
#XS Ineff= 2 , 0
          265.12 2666.96  349.19            2665
Permanent Ineff=
       F       F
Bank Sta=284.3,332.6
XS Rating Curve= 0 ,0
Exp/Cntr(USF)=0,0
Exp/Cntr=0.3,0.1

Type RM Length L Ch R = 1 ,19912   ,499.2,471,429.6
XS GIS Cut Line= 4
 2165839.9471991420652.4478143752165756.37023149420488.447726994
2165951.90879721 420195.139878412165865.17798177420106.832139052
#Sta/Elev= 30
       0 2760.97    21.6 2749.27    46.9 2733.29    53.1 2730.66    75.5 2717.18
    84.5 2712.97    97.9 2703.38   124.2  2688.9   142.8  2672.3     151 2668.39
   174.7 2652.06   183.2 2648.37   197.6 2645.31   207.2 2644.62   255.5 2643.06
   284.4 2643.67   322.6  2642.6   351.4 2643.32   365.1 2641.34   385.1 2641.09
   409.1 2639.98   421.7 2640.22     424 2641.06   428.9 2643.53   495.7 2645.81
   529.3 2654.32   574.5 2654.33   584.2 2657.02   625.5 2658.26   660.4 2661.56
#Mann= 5 ,-1,0
       0      .1       0   385.1    .045       0     424      .1       0
  424.07     .06       0  546.58      .1       0
#XS Ineff= 2 , 0
                          458.76         2660.79
Permanent Ineff=
       F       F
Bank Sta=385.1,424
XS Rating Curve= 0 ,0
Exp/Cntr(USF)=0,0
Exp/Cntr=0.3,0.1

Type RM Length L Ch R = 1 ,19441   ,448.8,442.4,438.1
XS GIS Cut Line= 3
2166437.60136368420456.9092486522166368.21671133 420299.21685694
2165970.83188422419969.639758262
#Sta/Elev= 30
       0 2782.93    43.4 2758.14    56.5  2749.2    87.1 2722.16   104.6 2705.25
   113.3 2699.38   161.7 2658.23   172.3 2649.99   182.7 2643.41   190.8 2640.24
   206.8 2640.68   219.1 2639.31   231.9 2635.07   247.6 2633.74   260.7 2629.96
   273.2 2630.15   293.1 2629.48   301.6 2629.97   319.6 2635.15   325.9 2635.89
   349.9 2635.33   385.4 2637.05   501.3 2636.11   511.8 2639.52   531.7  2652.8
   541.3  2655.6   560.1 2654.89   572.5 2657.29   645.3 2659.72   688.6  2662.5
#Mann= 5 ,-1,0
       0      .1       0   273.2    .045       0   301.6      .1       0
  412.28     .06       0  532.28      .1       0
#XS Ineff= 2 , 0
                           328.7          2672.2
Permanent Ineff=
       F       F
Bank Sta=273.2,301.6
XS Rating Curve= 0 ,0
Exp/Cntr(USF)=0,0
Exp/Cntr=0.3,0.1

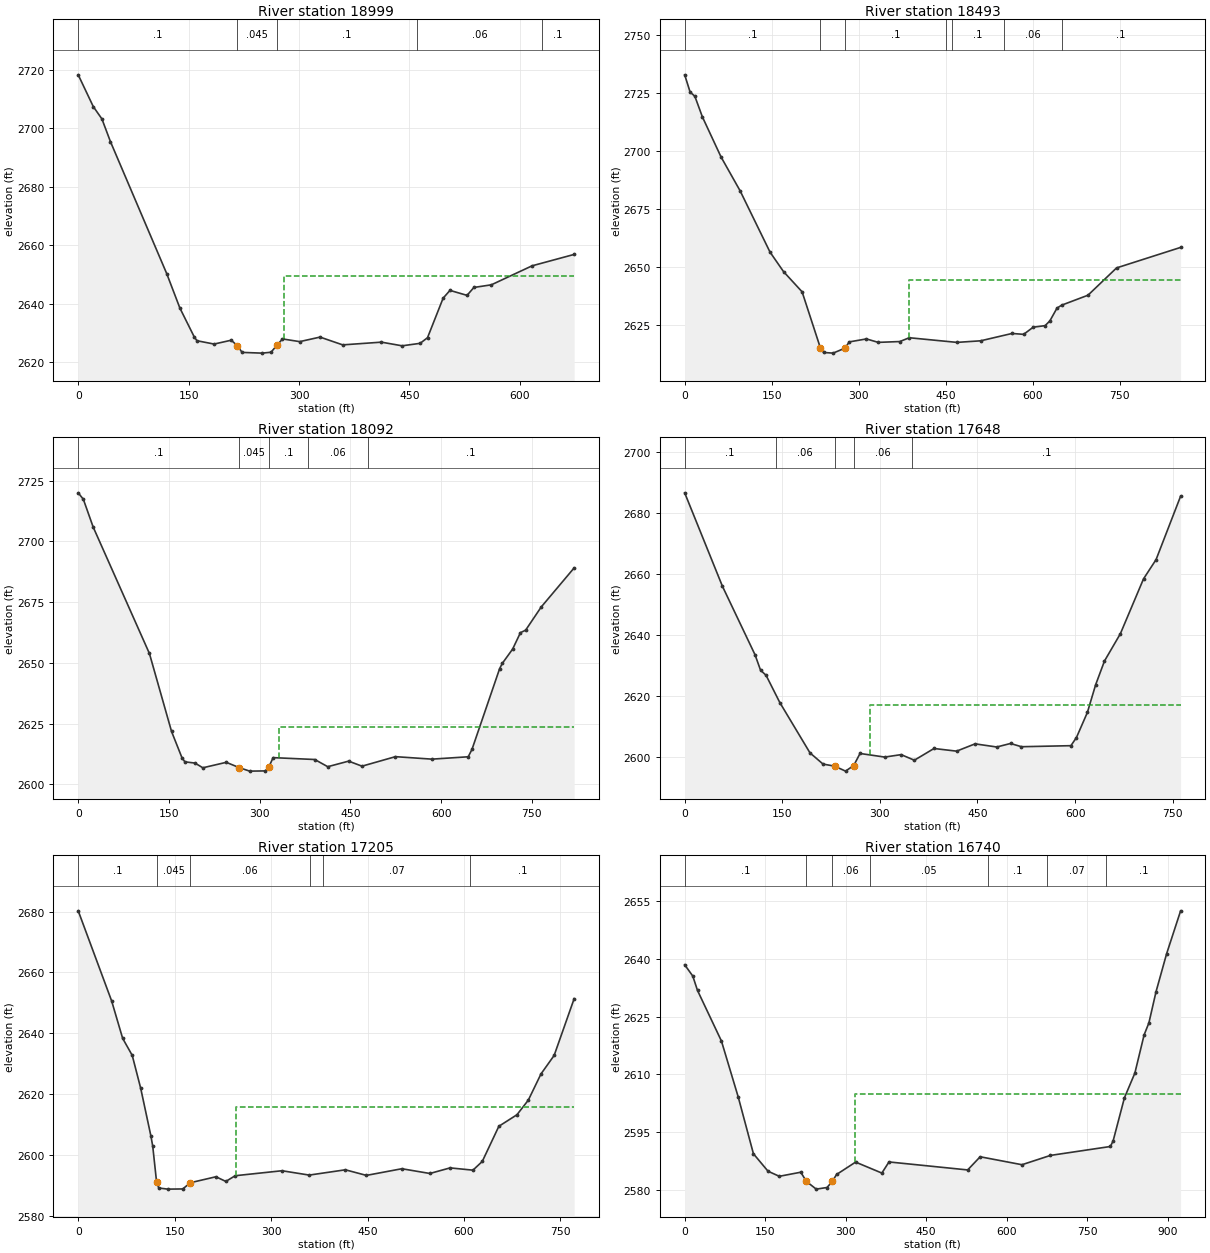
Type RM Length L Ch R = 1 ,18999   ,523,506,482.4
XS GIS Cut Line= 2
2166779.16438201420014.2219282652166198.85638051 419672.02943825
#Sta/Elev= 30
       0 2718.19    20.5 2707.32    32.2 2703.12    43.8 2695.35   120.2 2650.28
   138.1  2638.5   157.8 2628.54   161.4 2627.32   184.6 2626.19   207.8  2627.5
   216.2 2625.65   222.6 2623.34   249.6 2623.09   261.9 2623.39   269.8 2625.74
   277.5 2627.94   300.9 2627.02   328.5 2628.57   359.3 2625.91   411.9 2626.84
     440 2625.59   464.5 2626.44   474.5 2628.36   495.7 2641.87     505 2644.53
   528.2 2642.83   537.5 2645.53   561.2 2646.43   616.6 2652.93   673.7 2656.82
#Mann= 5 ,-1,0
       0      .1       0   216.2    .045       0   269.8      .1       0
     460     .06       0     630      .1       0
#XS Ineff= 2 , 0
                          279.32         2649.47
Permanent Ineff=
       F       F
Bank Sta=216.2,269.8
XS Rating Curve= 0 ,0
Exp/Cntr(USF)=0,0
Exp/Cntr=0.3,0.1

Type RM Length L Ch R = 1 ,18493   ,383.4,400.7,417.7
XS GIS Cut Line= 2
 2167017.2798935419397.6446766712166184.66406526419591.606318477
#Sta/Elev= 30
       0 2732.75     9.3 2725.39    17.6 2723.48    30.5 2714.67    62.7 2697.41
    95.6 2682.83   147.1 2656.49   170.4  2648.1   202.4 2639.41   233.7 2615.45
   239.3 2613.32   255.8 2613.03   276.3 2615.17   283.7 2617.86   313.3 2619.14
   333.6 2617.66   370.8 2618.01   387.2 2619.65   469.3 2617.65   510.2 2618.33
   564.3 2621.49   584.3 2621.11   600.8 2624.19   621.3 2624.85   629.5 2626.89
   641.8  2632.4     650 2633.68   695.2 2637.94   744.5 2649.69   854.9 2658.51
#Mann= 7 ,-1,0
       0      .1       0   233.7    .045       0   276.3      .1       0
     450     .06       0     460      .1       0     550     .06       0
     650      .1       0
#XS Ineff= 2 , 0
                          387.44          2644.5
Permanent Ineff=
       F       F
Bank Sta=233.7,276.3
XS Rating Curve= 0 ,0
Exp/Cntr(USF)=0,0
Exp/Cntr=0.3,0.1

Type RM Length L Ch R = 1 ,18092   ,445.8,443.7,440.5
XS GIS Cut Line= 3
2167036.63128083  419141.05384672166888.67298737419119.638830542
2166265.69069912418872.392734895
#Sta/Elev= 30
       0 2719.95     8.5 2717.29    24.7 2705.89   117.7 2653.87   154.3 2621.79
   171.6 2610.94   176.4 2609.31   193.1  2608.8     206 2606.86   244.7 2609.11
   266.2 2606.93   283.4 2605.49   309.3 2605.58   315.1 2607.18   322.2 2611.04
     391 2610.27   412.5 2607.31     447  2609.6   469.1 2607.53   524.4 2611.44
   584.7 2610.42   644.7 2611.39   650.9 2614.42   696.6 2647.62   700.9 2649.76
   718.1 2655.68     731 2662.43   739.6 2663.47   765.4 2673.01   819.8 2689.08
#Mann= 5 ,-1,0
       0      .1       0   266.2    .045       0   315.1      .1       0
   379.5     .06       0   479.5      .1       0
#XS Ineff= 2 , 0
                          332.37         2623.67
Permanent Ineff=
       F       F
Bank Sta=266.2,315.1
XS Rating Curve= 0 ,0
Exp/Cntr(USF)=0,0
Exp/Cntr=0.3,0.1

Type RM Length L Ch R = 1 ,17648   ,441.9,443.7,445.7
XS GIS Cut Line= 2
2167106.71678825418736.1153593412166384.44669782418492.762902996
#Sta/Elev= 30
       0 2686.61      58 2656.03   108.2 2633.56   116.6 2628.54   125.1 2626.87
   146.2 2617.96   192.6 2601.47   212.7  2597.8   230.6 2597.13   247.2  2595.5
   259.8 2597.34   269.5 2601.28   307.4  2600.1   332.7  2600.9     353 2599.07
   383.2 2602.91   417.9 2602.04   446.3 2604.43   479.6  2603.4   500.8 2604.55
   517.6 2603.49   593.6 2603.83   602.1  2606.5   618.9 2614.71   631.6 2623.77
   645.2 2631.56   669.6 2640.48   705.2 2658.45   724.5 2664.76   762.2 2685.52
#Mann= 5 ,-1,0
       0      .1       0     140     .06       0   230.6    .045       0
   259.8     .06       0     350      .1       0
#XS Ineff= 2 , 0
                          285.22         2617.03
Permanent Ineff=
       F       F
Bank Sta=230.6,259.8
XS Rating Curve= 0 ,0
Exp/Cntr(USF)=0,0
Exp/Cntr=0.3,0.1

Type RM Length L Ch R = 1 ,17205   ,467.3,465,462.2
XS GIS Cut Line= 2
2167295.23096429418405.5442073392166636.07676694418005.005532391
#Sta/Elev= 30
       0 2680.27      52  2650.6    69.1 2638.31      84 2632.71    97.2 2621.86
   113.1 2606.12   115.9 2602.81   121.9    2591   125.3 2589.06   139.3 2588.69
   162.6 2588.75   174.3 2590.79   214.2 2592.76   229.6 2591.22   244.1  2593.1
   316.9 2594.74   359.3 2593.31   415.5 2595.05   448.2 2593.21   503.3  2595.4
   546.9 2593.84   578.4 2595.68   613.9 2594.93   628.4  2597.8   654.2 2609.37
   682.3 2613.16     700 2617.97   719.7 2626.59   740.2 2632.69   771.3 2651.37
#Mann= 6 ,-1,0
       0      .1       0   121.9    .045       0   174.3     .06       0
     360      .1       0     380     .07       0     610      .1       0
#XS Ineff= 2 , 0
                          246.02         2615.82
Permanent Ineff=
       F       F
Bank Sta=121.9,174.3
XS Rating Curve= 0 ,0
Exp/Cntr(USF)=0,0
Exp/Cntr=0.3,0.1

Type RM Length L Ch R = 1 ,16740   ,425.6,431.5,436.1
XS GIS Cut Line= 3
  2167628.243886418130.0522654712167556.85587798 418014.78049471
2166846.96034421417671.632416682
#Sta/Elev= 30
       0  2638.4    15.1 2635.48    23.9 2631.75    68.5 2618.65    99.8 2604.15
   128.1 2589.46   155.3 2584.94   176.3 2583.62   216.3 2584.68   226.8  2582.3
   245.1  2580.3   265.2 2580.72   275.1  2582.3     283 2584.09   318.5  2587.3
   367.4 2584.46   380.7 2587.34   527.3 2585.27   550.6 2588.68   628.5 2586.62
   681.5 2589.03   793.2 2591.34   798.3 2592.77   819.4 2603.95   838.8 2610.33
   856.1 2620.25     865 2623.35   878.3 2631.43     898 2641.26   924.1 2652.37
#Mann= 7 ,-1,0
       0      .1       0   226.8    .045       0   275.1     .06       0
  345.59     .05       0  565.59      .1       0  675.59     .07       0
  785.59      .1       0
#XS Ineff= 2 , 0
                          317.87         2604.87
Permanent Ineff=
       F       F
Bank Sta=226.8,275.1
XS Rating Curve= 0 ,0
Exp/Cntr(USF)=0,0
Exp/Cntr=0.3,0.1

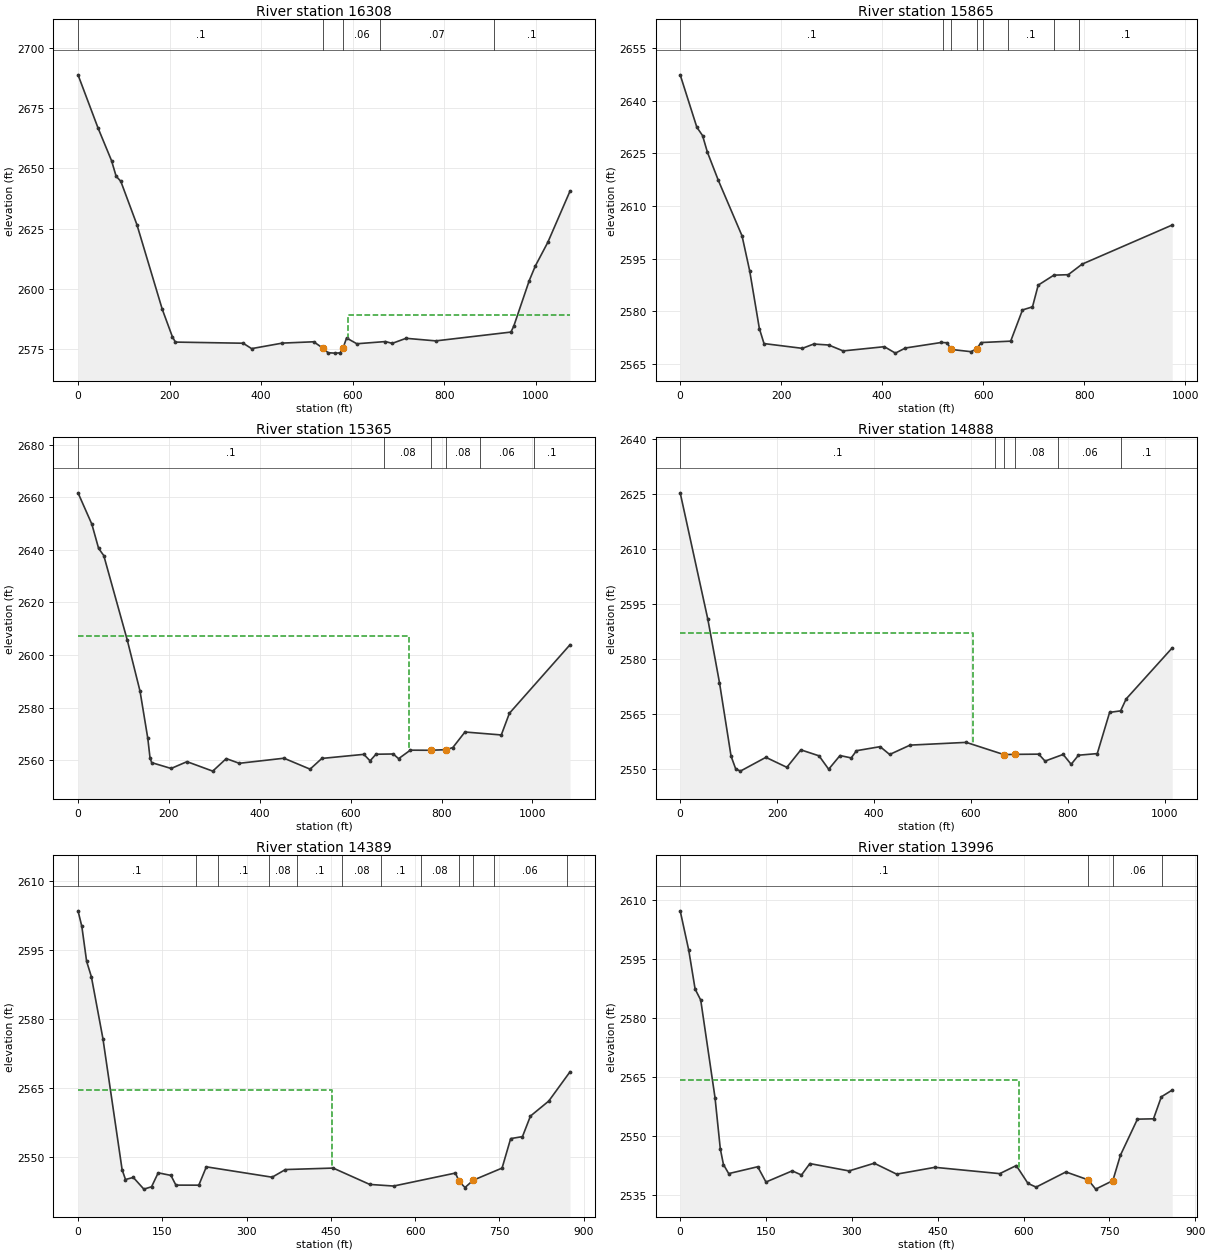
Type RM Length L Ch R = 1 ,16308   ,438.4,443,445.9
XS GIS Cut Line= 3
2168055.54276457417955.2778198752167934.40731964417797.369114868
2167233.55224536417271.727809162
#Sta/Elev= 30
       0 2688.85    43.8 2666.76    73.2 2653.26    83.3 2646.76    93.4  2644.7
   128.7 2626.68   184.1 2591.56     206 2580.27   212.7 2577.96   360.8 2577.49
   379.3 2575.25   446.5 2577.54     515 2578.09     535 2575.44   546.5 2573.53
   561.8 2573.38   572.7 2573.48   579.12575.503   586.8 2579.65   609.2 2577.27
   671.8 2578.18   686.5 2577.43   716.8 2579.53   781.8 2578.46     946 2582.12
   952.2 2584.62     986  2603.5   999.3 2609.57  1026.5 2619.35  1075.1 2640.64
#Mann= 5 ,-1,0
       0      .1       0     535    .045       0   579.1     .06       0
  659.02     .07       0  909.02      .1       0
#XS Ineff= 2 , 0
                          589.06          2589.4
Permanent Ineff=
       F       F
Bank Sta=535,579.1
XS Rating Curve= 0 ,0
Exp/Cntr(USF)=0,0
Exp/Cntr=0.3,0.1

Type RM Length L Ch R = 1 ,15865   ,510.3,500.2,489.6
XS GIS Cut Line= 2
2168377.84957342417702.1912652752167696.46269566417005.662456891
#Sta/Elev= 30
       0 2647.34      33 2632.42    44.3 2630.05    53.9 2625.33    75.4 2617.36
   122.5 2601.51   137.7 2591.51   156.8 2575.13     166 2570.86     242  2569.5
   264.4 2570.73   294.1 2570.45   322.7 2568.77   404.3 2569.97   426.2 2568.14
     446  2569.6   517.2 2571.17   528.6 2571.09   536.5 2569.19   576.1 2568.55
   587.4 2569.44   595.9 2571.15   654.5 2571.55   677.9 2580.43   697.7 2581.31
     709 2587.49     740 2590.33   768.5 2590.46     796 2593.47   974.4  2604.6
#Mann= 8 ,-1,0
       0      .1       0     520     .06       0   536.5    .045       0
   587.4     .06       0     600     .08       0     650      .1       0
     740     .07       0     790      .1       0
Bank Sta=536.5,587.4
XS Rating Curve= 0 ,0
Exp/Cntr(USF)=0,0
Exp/Cntr=0.3,0.1

Type RM Length L Ch R = 1 ,15365   ,464.4,477.2,483.7
XS GIS Cut Line= 3
2168897.00148029 417327.969265742168468.70115713 416992.68365922
2167984.15937738416756.902168183
#Sta/Elev= 30
       0 2661.68    30.5 2649.73    45.3 2640.55    56.7 2637.81   108.4 2605.67
   136.5 2586.23   153.6 2568.24   158.5 2560.82   162.1 2559.06   204.9 2556.84
   239.8 2559.43   296.5 2555.83   326.2 2560.59   354.9 2558.81   453.2 2560.74
   510.7 2556.58   536.6 2560.66     629 2562.21   642.7 2559.74   655.7 2562.26
   693.6 2562.35   705.5 2560.57   731.3  2563.8     7772563.766   809.82563.998
   824.8 2564.79   851.5 2570.71   931.5 2569.59   949.3 2577.83  1082.8 2603.91
#Mann= 6 ,-1,0
       0      .1       0  673.93     .08       0     777    .045       0
   809.8     .08       0  883.93     .06       0 1003.93      .1       0
#XS Ineff= 2 , 0
          728.12 2607.24
Permanent Ineff=
       F       F
Bank Sta=777,809.8
XS Rating Curve= 0 ,0
Exp/Cntr(USF)=0,0
Exp/Cntr=0.3,0.1

Type RM Length L Ch R = 1 ,14888   ,502,498.7,494.3
XS GIS Cut Line= 3
2169039.76825468416966.7260638762168739.09277529416767.717832909
2168312.95558506416270.197255492
#Sta/Elev= 30
       0 2625.43    57.1 2590.94    81.1 2573.68     105 2553.65   114.6 2550.15
   124.2 2549.55   176.9 2553.31   220.2 2550.59   249.1 2555.35   286.6 2553.72
   306.5 2550.07   329.9  2553.8     353 2553.15   363.9 2555.12   412.7 2556.22
   432.4 2554.09   474.5 2556.64   590.4 2557.39   668.32554.052   691.62554.124
   740.1 2554.18   753.1 2552.29   790.5  2554.1     807 2551.41   822.1 2553.89
   860.9 2554.33   886.4 2565.57   909.1 2565.98   920.5 2569.23  1015.6 2583.15
#Mann= 6 ,-1,0
       0      .1       0  650.57     .08       0   668.3    .045       0
   691.6     .08       0  780.57     .06       0  910.57      .1       0
#XS Ineff= 2 , 0
          605.22  2587.1
Permanent Ineff=
       F       F
Bank Sta=668.3,691.6
XS Rating Curve= 0 ,0
Exp/Cntr(USF)=0,0
Exp/Cntr=0.3,0.1

Type RM Length L Ch R = 1 ,14389   ,387.8,392.7,403.7
XS GIS Cut Line= 2
2169292.85480928416614.1353937932168646.07805864416023.600099729
#Sta/Elev= 30
       0 2603.51     6.8 2600.12    15.3 2592.55    23.8 2589.19    44.3 2575.79
    78.5  2547.3    84.5 2545.18    98.4 2545.63   117.2 2543.09   130.9  2543.6
   142.7 2546.63   165.4 2546.07   174.2 2543.96     215 2543.95   228.4 2547.93
   345.5 2545.68   369.2 2547.34   454.2 2547.66   519.3 2544.11   561.8 2543.76
   671.8 2546.58     678 2544.85   688.8 2543.43   703.3 2545.02   754.8 2547.66
   770.1 2554.06   791.1 2554.49   805.3 2558.95   837.9 2562.21   875.8 2568.57
#Mann= 12 ,-1,0
       0      .1       0     210     .08       0     250      .1       0
     340     .08       0     390      .1       0     470     .08       0
     540      .1       0     610     .08       0     678    .045       0
   703.3      .1       0     740     .06       0     870      .1       0
#XS Ineff= 2 , 0
          452.17 2564.52
Permanent Ineff=
       F       F
Bank Sta=678,703.3
XS Rating Curve= 0 ,0
Exp/Cntr(USF)=0,0
Exp/Cntr=0.3,0.1

Type RM Length L Ch R = 1 ,13996   ,575.6,569.4,561.1
XS GIS Cut Line= 3
 2169513.4943697416356.7225733042169184.69816202416125.267348157
2168933.77474036415742.392816841
#Sta/Elev= 30
       0 2607.14      15 2597.12    26.1 2587.28    35.9  2584.5    60.9 2559.73
    70.1 2546.78    75.6 2542.78    84.8 2540.48   135.5 2542.22   149.9 2538.34
   195.8 2541.17     212 2540.12   226.6 2543.02   295.1 2541.16   339.1 2543.11
   378.3 2540.34   445.2 2542.07   558.5 2540.47   587.4 2542.52   607.8 2537.99
     622 2537.05   674.1  2540.9   713.1 2538.89   726.1 2536.54   756.1 2538.69
   769.4 2545.15   799.1 2554.29   827.2 2554.38   840.9 2559.96   859.9 2561.67
#Mann= 4 ,-1,0
       0      .1       0   713.1    .045       0   756.1     .06       0
  842.09     .12       0
#XS Ineff= 2 , 0
           591.3 2564.34
Permanent Ineff=
       F       F
Bank Sta=713.1,756.1
XS Rating Curve= 0 ,0
Exp/Cntr(USF)=0,0
Exp/Cntr=0.3,0.1