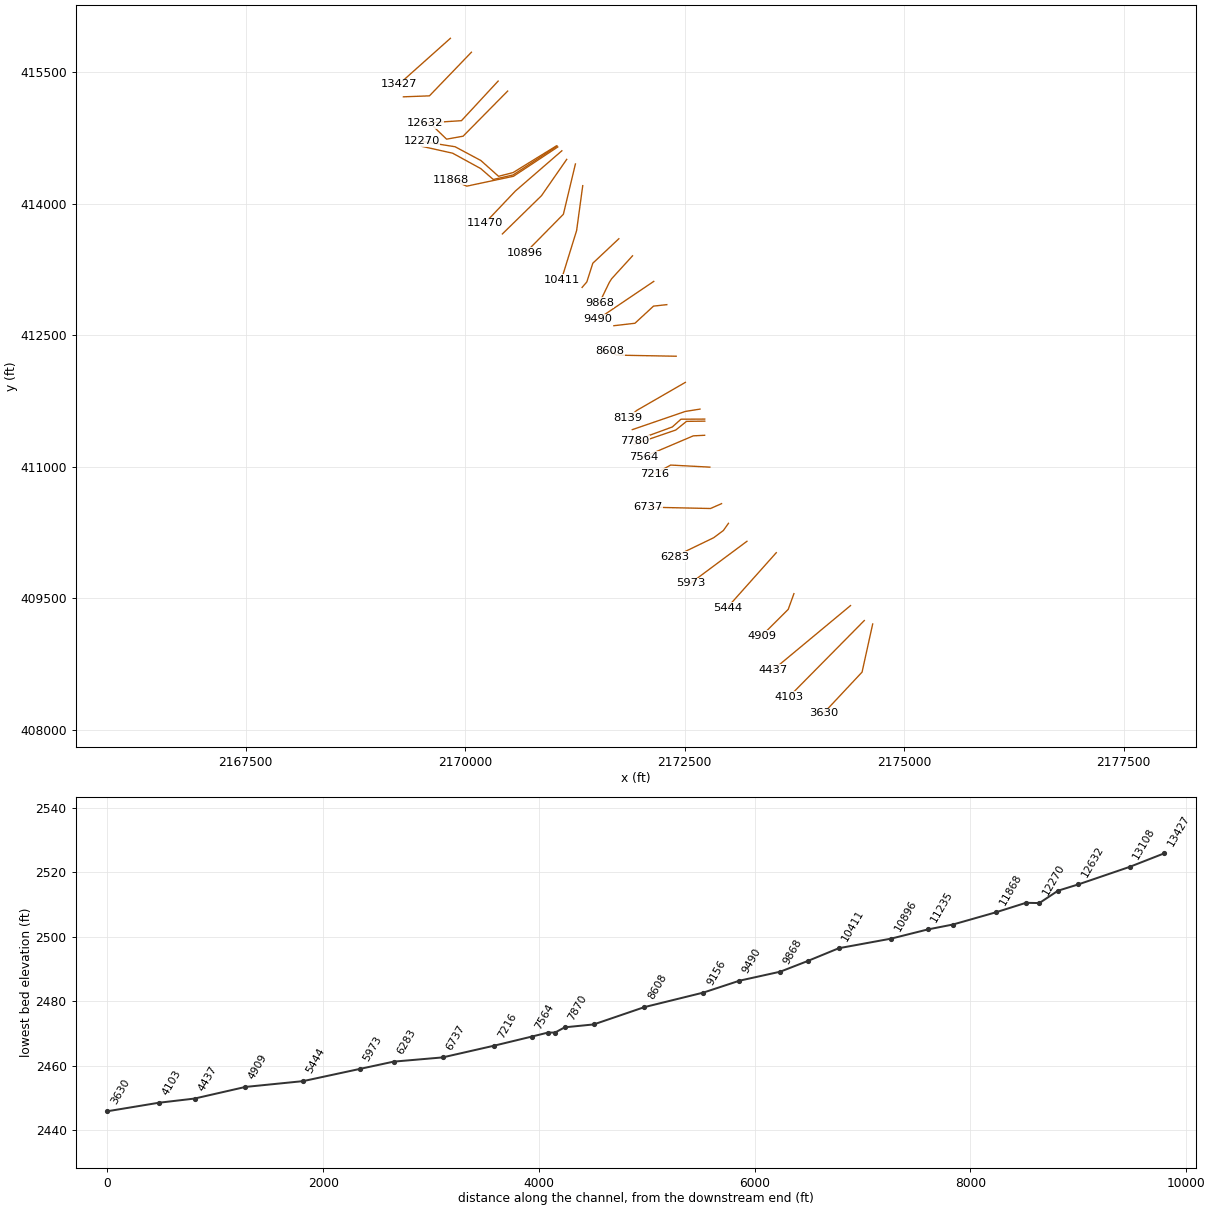
HEC-RAS study HLLSCK.prj: HLLSCK

--- HLLSCK.g01 (geometry) --- (continued)

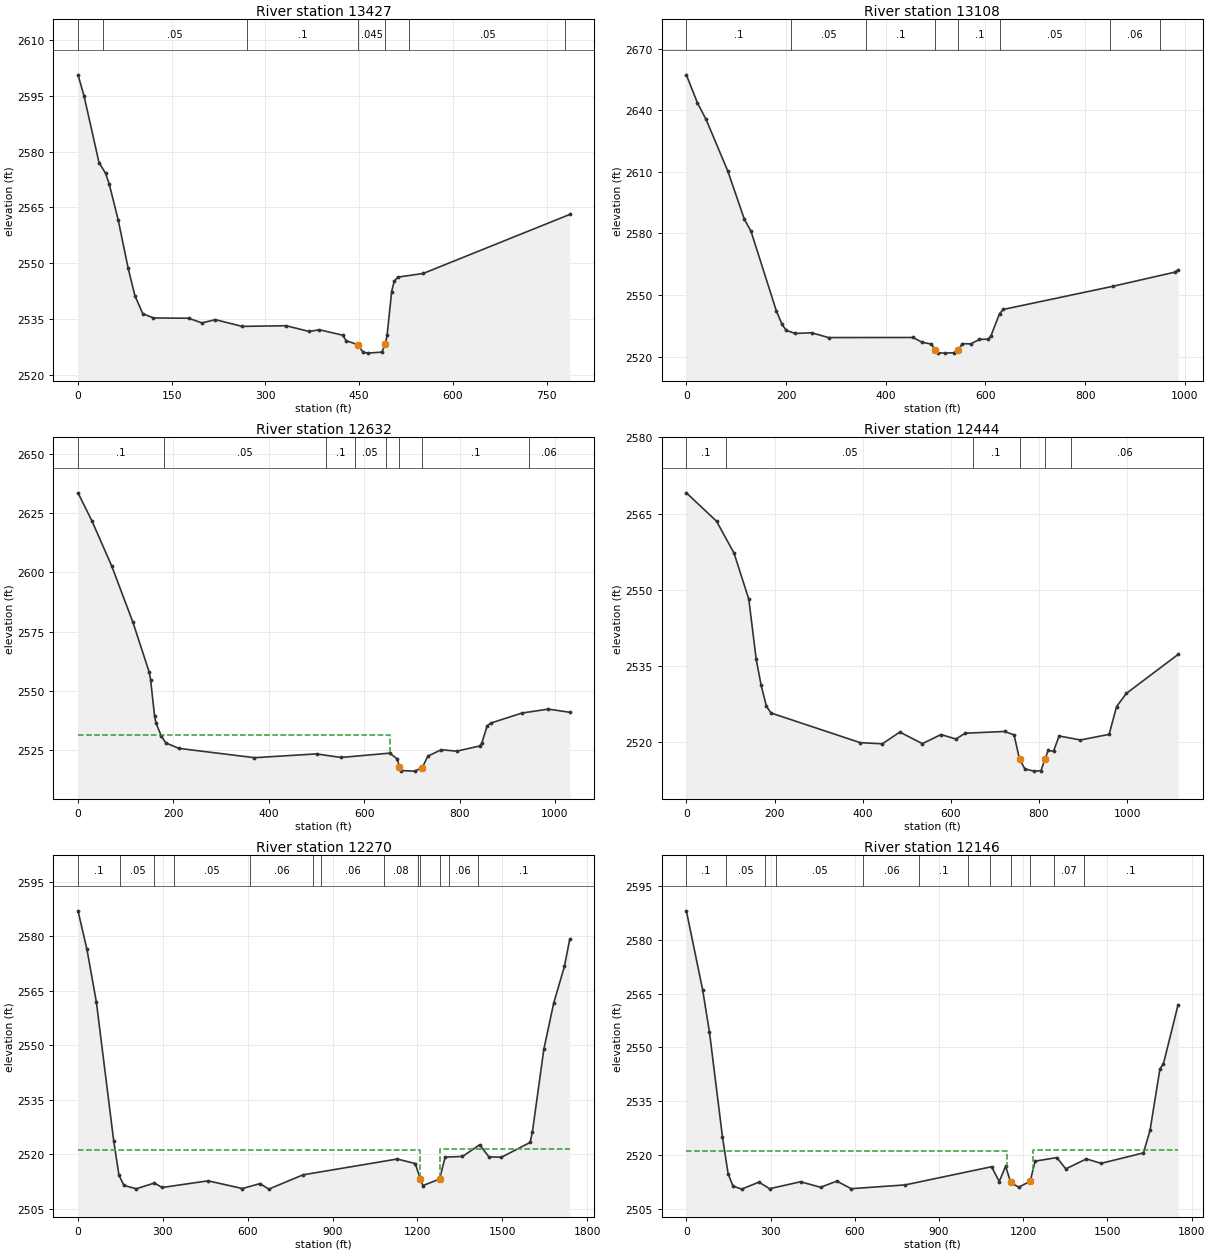
Type RM Length L Ch R = 1 ,13427   ,317,318.8,320.9
XS GIS Cut Line= 2
2169832.08947956415883.5786470312169245.39065663415359.396911796
#Sta/Elev= 30
       0 2600.62     9.6    2595    33.6 2577.05    44.1 2574.19    49.8 2571.38
    64.3 2561.67    80.3 2548.65    91.1 2541.28   103.6  2536.5   120.6 2535.32
   176.9 2535.25   198.4    2534   219.8 2534.87   262.7 2533.06   333.1 2533.24
     370 2531.69   386.1 2532.16   423.6  2530.7     429 2529.24   447.9 2528.13
   455.8 2526.18   463.4 2525.88   486.1 2526.15   491.7 2528.27   494.6 2530.67
   501.9 2542.43   505.9 2545.13   511.6 2546.28   552.4 2547.28   786.8 2563.12
#Mann= 7 ,-1,0
       0      .1       0      40     .05       0     270      .1       0
   447.9    .045       0   491.7      .1       0     530     .05       0
     780     .06       0
Bank Sta=447.9,491.7
XS Rating Curve= 0 ,0
Exp/Cntr(USF)=0,0
Exp/Cntr=0.3,0.1

Type RM Length L Ch R = 1 ,13108   ,498.8,476.2,455.3
XS GIS Cut Line= 3
2170071.58266959415725.0877532782169593.53028868415227.567175861
2169297.18107517415216.751511135
#Sta/Elev= 30
       0 2657.27    22.2 2643.61    39.6 2635.53    83.1 2610.41   116.4 2586.89
   129.7 2581.05   180.6 2542.21   191.9 2535.72   200.4 2532.77   218.5  2531.3
   251.3 2531.62   285.2 2529.28     455 2529.32   472.5 2527.03   491.8 2526.09
   499.1 2523.25   504.7 2521.85   518.7  2521.7     537  2521.9   545.5 2523.45
     554 2526.29   570.7  2526.2     588 2528.38   605.3 2528.49   611.1 2530.12
   628.4 2540.99     636 2542.99   855.1 2554.23   979.4 2561.11   986.5 2562.29
#Mann= 8 ,-1,0
       0      .1       0     210     .05       0     360      .1       0
   499.1    .045       0   545.5      .1       0     630     .05       0
  849.97     .06       0  949.97     .07       0
Bank Sta=499.1,545.5
XS Rating Curve= 0 ,0
Exp/Cntr(USF)=0,0
Exp/Cntr=0.3,0.1

Type RM Length L Ch R = 1 ,12632   ,183.7,187.8,190.8
XS GIS Cut Line= 3
2170375.97254435415396.3059483372169958.36428938414944.617596328
2169543.56442758414917.940020447
#Sta/Elev= 30
       0 2633.51    29.2 2621.67    70.4 2602.82   115.3 2578.88   149.3 2557.95
   152.1 2554.85   160.6 2539.43   163.4 2536.58   174.7 2531.03     184 2528.18
   211.3 2525.85     370 2521.92     500 2523.52   551.2 2522.01   653.4 2523.84
   669.5 2521.37   673.8 2517.98   677.5 2516.51   705.5 2516.26   721.6 2517.68
   733.4 2522.58   761.6 2525.28   793.7 2524.66   841.8 2526.84   846.4 2528.01
   857.8 2535.34   865.2 2536.49   930.8 2540.74   986.1 2542.39  1030.8 2541.05
#Mann= 8 ,-1,0
       0      .1       0     180     .05       0     520      .1       0
     580     .05       0  645.16      .1       0   673.8    .045       0
   721.6      .1       0  945.16     .06       0
#XS Ineff= 2 , 0
          654.76 2531.66
Permanent Ineff=
       F       F
Bank Sta=673.8,721.6
XS Rating Curve= 0 ,0
Exp/Cntr(USF)=0,0
Exp/Cntr=0.3,0.1

Type RM Length L Ch R = 1 ,12444   ,199.6,173.6,148.7
XS GIS Cut Line= 4
2170484.15789267415282.0192741962169976.87015798414767.695038706
2169788.98968137414733.671087193 2169643.7041285414874.066231372
#Sta/Elev= 30
       0  2569.1    68.5 2563.51   108.1 2557.24   141.6 2548.17   158.5 2536.29
   169.7 2531.17   181.6 2527.08   192.2 2525.75   394.5 2519.91   444.7 2519.69
   484.2    2522   535.4 2519.72   577.6 2521.51   611.5 2520.63   632.3 2521.77
   721.8 2522.12   743.4 2521.44   755.72516.688   767.8 2514.76   788.2 2514.31
   804.4 2514.38   813.32516.656   820.7 2518.38   832.9 2518.23   845.6 2521.23
   893.9 2520.44     959 2521.55   975.8 2526.99   997.9  2529.6  1115.4 2537.28
#Mann= 6 ,-1,0
       0      .1       0      90     .05       0     650      .1       0
   755.7    .045       0   813.3      .1       0  872.41     .06       0
Bank Sta=755.7,813.3
XS Rating Curve= 0 ,0
Exp/Cntr(USF)=0,0
Exp/Cntr=0.5,0.3

Type RM Length L Ch R = 1 ,12270   ,125.8,124,125.2
XS GIS Cut Line= 6
2171039.56852439 414657.381563832170546.38183124414352.787642394
2170380.73439165414310.1925864992170179.54879565414490.068802185
2169885.70044643414647.474308026  2169505.776525414707.881162091
#Sta/Elev= 30
       0    2587    31.7 2576.37    65.1 2561.84   126.2 2523.77     145 2514.25
   162.5 2511.49   205.9 2510.57     270 2512.14   297.3 2510.92     460 2512.75
   581.2 2510.64   643.6 2511.99   674.5 2510.47   795.7  2514.4  1128.7 2518.75
  1192.3 2517.51  1210.4 2513.33  1219.5 2511.44  1278.5 2513.24  1298.2 2519.28
  1359.5 2519.46  1420.3 2522.67  1452.7 2519.36  1497.2 2519.24  1598.5 2523.31
  1606.6 2526.16  1647.1 2548.91  1681.7 2561.52    1720 2571.75  1738.6 2579.15
#Mann= 13 ,-1,0
       0      .1       0     150     .05       0     270     .06       0
     340     .05       0  609.66     .06       0   830.7      .1       0
   860.7     .06       0 1080.57     .08       0 1200.57     .06       0
  1210.4    .045       0  1278.5      .1       0 1310.57     .06       0
 1413.92      .1       0
#XS Ineff= 2 , 0
         1208.96  2521.3 1279.61          2521.5
Permanent Ineff=
       F       F
Bank Sta=1210.4,1278.5
XS Rating Curve= 0 ,0
Exp/Cntr(USF)=0,0
Exp/Cntr=0.5,0.3

Type RM Length L Ch R = 1 ,12146   ,246.7,278.2,302.5
XS GIS Cut Line= 6
 2171048.7413322414654.6465283962170546.38183124414325.968533127
2170320.78579447414273.907909255 2170177.9764584414398.308283512
2169857.94995019414573.8083704872169501.24090451414653.385530746
#Sta/Elev= 30
       0 2588.04      58 2566.06    82.4  2554.2   128.6 2525.09   148.8 2514.81
   166.2  2511.4   196.7 2510.55   258.6  2512.5   296.2 2510.67     407  2512.6
   478.2 2511.06     536 2512.78   587.2 2510.67   779.6 2511.73  1087.2 2516.78
  1114.5 2512.67  1137.4 2516.92  1155.6  2512.4  1183.8 2511.09    1225 2512.75
  1242.3 2518.34  1319.8 2519.34  1351.8 2516.19  1424.9 2518.96  1477.7 2517.73
  1628.5 2520.64  1651.9 2526.94  1687.2 2544.07  1699.5 2545.45  1751.7 2561.87
#Mann= 12 ,-1,0
       0      .1       0     140     .05       0     280     .06       0
     320     .05       0  630.33     .06       0  830.33      .1       0
 1001.85     .06       0 1081.25      .1       0  1155.6    .045       0
    1225     .06       0 1311.25     .07       0 1416.24      .1       0
#XS Ineff= 2 , 0
         1141.59  2521.3 1234.64          2521.5
Permanent Ineff=
       F       F
Bank Sta=1155.6,1225
XS Rating Curve= 0 ,0
Exp/Cntr(USF)=0,0
Exp/Cntr=0.5,0.3

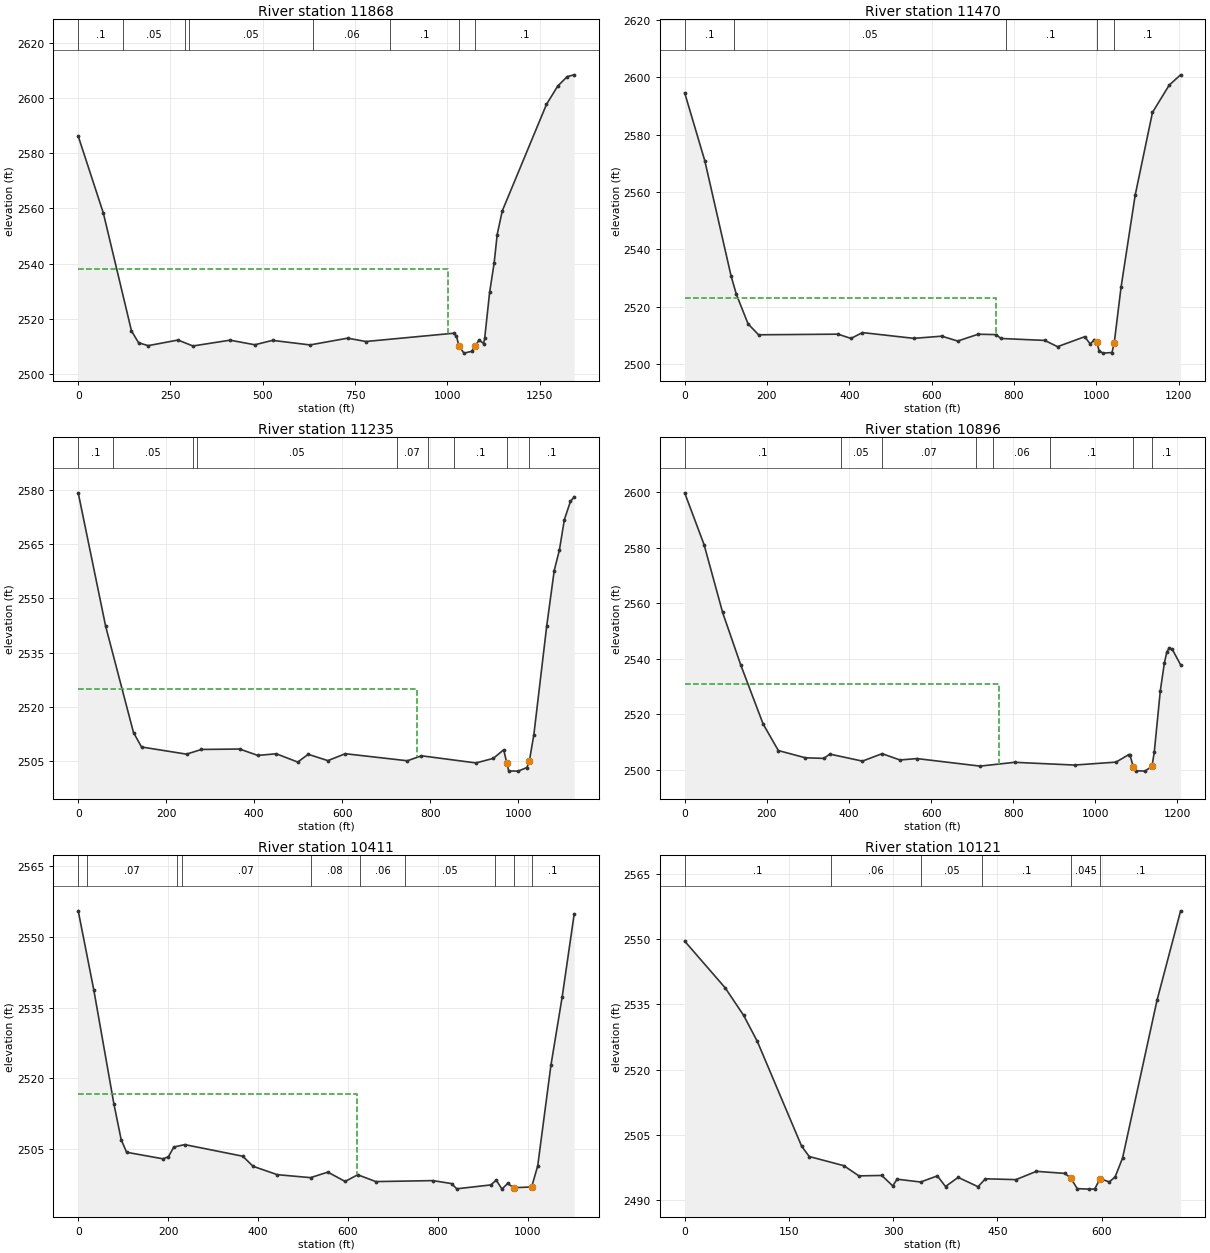
Type RM Length L Ch R = 1 ,11868   ,382.1,398,414.6
XS GIS Cut Line= 4
2171055.05508451414644.8841823592170550.22633643414310.538287364
2170018.79000419414198.1018860922169838.95329878414272.957622969
#Sta/Elev= 30
       0 2586.21    68.1 2558.33   144.3 2515.67   163.5 2511.37   189.5 2510.32
   270.3 2512.35   310.7  2510.2   411.3  2512.3   478.4 2510.64   526.4 2512.23
     628 2510.58   729.9 2513.03   779.3 2511.82  1016.7 2514.81  1024.6  2513.8
  1031.6 2510.09  1045.1 2507.61  1065.5 2508.25  1075.9 2510.26    1086  2512.4
  1098.2 2511.08  1101.1 2512.91  1114.5 2529.62  1126.8 2540.28    1135 2550.56
  1148.7  2559.1  1268.5 2597.69  1298.9 2604.33  1324.8 2607.77  1343.5 2608.41
#Mann= 8 ,-1,0
       0      .1       0     120     .05       0     290     .06       0
     300     .05       0  635.51     .06       0  845.51      .1       0
  1031.6    .045       0  1075.9      .1       0
#XS Ineff= 2 , 0
         1002.32 2538.14
Permanent Ineff=
       F       F
Bank Sta=1031.6,1075.9
XS Rating Curve= 0 ,0
Exp/Cntr(USF)=0,0
Exp/Cntr=0.3,0.1

Type RM Length L Ch R = 1 ,11470   ,235.9,235,234
XS GIS Cut Line= 3
2171101.47393331414601.2604222592170572.67127024414142.822629674
2170225.11145539413776.072395606
#Sta/Elev= 30
       0 2594.54      49  2570.8   112.9 2530.62   125.7 2524.27   154.1    2514
   179.6 2510.21   372.6 2510.43   404.1 2508.94     432 2510.98   556.8 2508.97
   624.8 2509.73   663.5 2508.03   713.1 2510.41   757.2 2510.27   768.2 2508.93
     875 2508.25     906 2506.07   972.2 2509.55   985.5 2506.98   995.6 2508.54
  1001.3 2507.74  1006.9 2504.72  1016.2 2503.82  1038.3 2504.03  1043.8  2507.4
  1060.3 2526.73  1094.7 2558.88  1136.7 2587.71  1177.4 2597.24  1205.1 2600.81
#Mann= 5 ,-1,0
       0      .1       0     120     .05       0  779.86      .1       0
  1001.3    .045       0  1043.8      .1       0
#XS Ineff= 2 , 0
           757.7  2523.2
Permanent Ineff=
       F       F
Bank Sta=1001.3,1043.8
XS Rating Curve= 0 ,0
Exp/Cntr(USF)=0,0
Exp/Cntr=0.3,0.1

Type RM Length L Ch R = 1 ,11235   ,337.2,338.5,338.2
XS GIS Cut Line= 3
 2171156.8226108414503.4326237422170869.40485157414089.118318357
2170424.24158666413653.081028138
#Sta/Elev= 30
       0 2579.15    62.4 2542.29   125.7 2512.93   143.9 2508.95   246.2 2506.97
   280.2 2508.27   367.1 2508.38   408.2 2506.62   450.3 2507.07   499.1 2504.78
   522.8 2506.93   567.6 2505.18   607.1 2507.09   748.3 2505.14   780.3 2506.52
   904.3 2504.54   943.5  2505.8   967.2 2508.17   974.6  2504.4   978.6 2502.34
  1000.1 2502.28  1019.9 2503.27  1025.5 2505.02  1035.8 2512.36  1065.1 2542.44
  1082.1 2557.68  1093.9 2563.36  1105.1 2571.72  1118.9 2576.76  1127.4 2578.04
#Mann= 9 ,-1,0
       0      .1       0      80     .05       0     260     .06       0
     270     .05       0  724.25     .07       0  794.25     .06       0
  854.25      .1       0   974.6    .045       0  1025.5      .1       0
#XS Ineff= 2 , 0
          769.86 2525.06
Permanent Ineff=
       F       F
Bank Sta=974.6,1025.5
XS Rating Curve= 0 ,0
Exp/Cntr(USF)=0,0
Exp/Cntr=0.3,0.1

Type RM Length L Ch R = 1 ,10896   ,466.6,485.8,497.1
XS GIS Cut Line= 3
2171255.94691693414451.0634421912171118.77936321413877.344932479
2170685.52074766413437.061492404
#Sta/Elev= 30
       0 2599.82    47.2 2581.15    92.4 2556.67   136.6 2537.71   191.1 2516.41
   228.1 2506.86   293.9 2504.25   339.2 2504.04   353.2 2505.59   432.9 2503.05
   480.7 2505.74   524.3 2503.46   565.4 2503.97   719.2 2501.25   803.4 2502.62
   949.3 2501.63  1050.3 2502.69  1081.2 2505.39    1084 2505.32  1092.5 2500.94
  1098.2 2499.59  1120.8 2499.44  1137.8 2501.19  1143.4 2506.21  1158.2 2528.47
  1168.1 2538.49  1173.8 2542.27  1179.4 2543.81  1186.7 2543.54  1207.6 2537.77
#Mann= 8 ,-1,0
       0      .1       0     380     .05       0     480     .07       0
  709.89     .05       0  749.89     .06       0  889.89      .1       0
  1092.5    .045       0  1137.8      .1       0
#XS Ineff= 2 , 0
          764.25 2530.95
Permanent Ineff=
       F       F
Bank Sta=1092.5,1137.8
XS Rating Curve= 0 ,0
Exp/Cntr(USF)=0,0
Exp/Cntr=0.3,0.1

Type RM Length L Ch R = 1 ,10411   ,289.7,289.7,289
XS GIS Cut Line= 3
2171339.26759334414203.7719474572171269.56664288413691.830483738
2171096.51600726413131.819399012
#Sta/Elev= 30
       0 2555.57    34.9 2538.65    79.3 2514.59    95.5 2506.98   107.6 2504.29
   188.3  2502.9   200.5 2503.32   212.5 2505.39   236.8 2505.92   365.9 2503.45
   388.8 2501.31   442.6 2499.53   516.7  2498.9   555.1 2500.07   593.5 2498.09
   621.6 2499.51   661.8 2498.06   788.6 2498.27   830.1 2497.64   841.8 2496.53
   917.2 2497.35   929.7 2498.35   942.3 2496.46   954.8 2497.66   968.5 2496.76
  1008.32496.921  1021.8 2501.42  1051.1 2522.73  1076.3 2537.36  1102.8 2554.84
#Mann= 10 ,-1,0
       0      .1       0      20     .07       0     220     .05       0
     230     .07       0  516.66     .08       0  626.66     .06       0
  726.66     .05       0  926.66      .1       0   968.5    .045       0
  1008.3      .1       0
#XS Ineff= 2 , 0
          619.13 2516.64
Permanent Ineff=
       F       F
Bank Sta=968.5,1008.3
XS Rating Curve= 0 ,0
Exp/Cntr(USF)=0,0
Exp/Cntr=0.3,0.1

Type RM Length L Ch R = 1 ,10121   ,257.4,252.7,249.7
XS GIS Cut Line= 4
2171750.64644111413598.461526196 2171453.9634235413319.027918391
2171386.15904953413106.4464137442171332.27301255413043.484989514
#Sta/Elev= 30
       0 2549.58    58.3 2538.82    84.7 2532.52   104.5  2526.5   168.2 2502.39
   179.2 2499.98     229 2497.87   250.7 2495.52   283.6 2495.62   299.4 2493.21
   305.6 2494.76   339.4 2494.11   363.6 2495.52   375.3 2493.07   393.5 2495.18
   422.1 2493.03   432.7 2494.85   476.7 2494.66   506.1 2496.57   547.3 2496.09
   555.6 2494.98   564.8 2492.59   581.6 2492.47     590  2492.5   597.7 2494.88
     611 2494.13   619.4 2495.29   630.1 2499.65   679.7 2535.99   713.6 2556.56
#Mann= 6 ,-1,0
       0      .1       0     210     .06       0     340     .05       0
  427.56      .1       0   555.6    .045       0   597.7      .1       0
Bank Sta=555.6,597.7
XS Rating Curve= 0 ,0
Exp/Cntr(USF)=0,0
Exp/Cntr=0.3,0.1

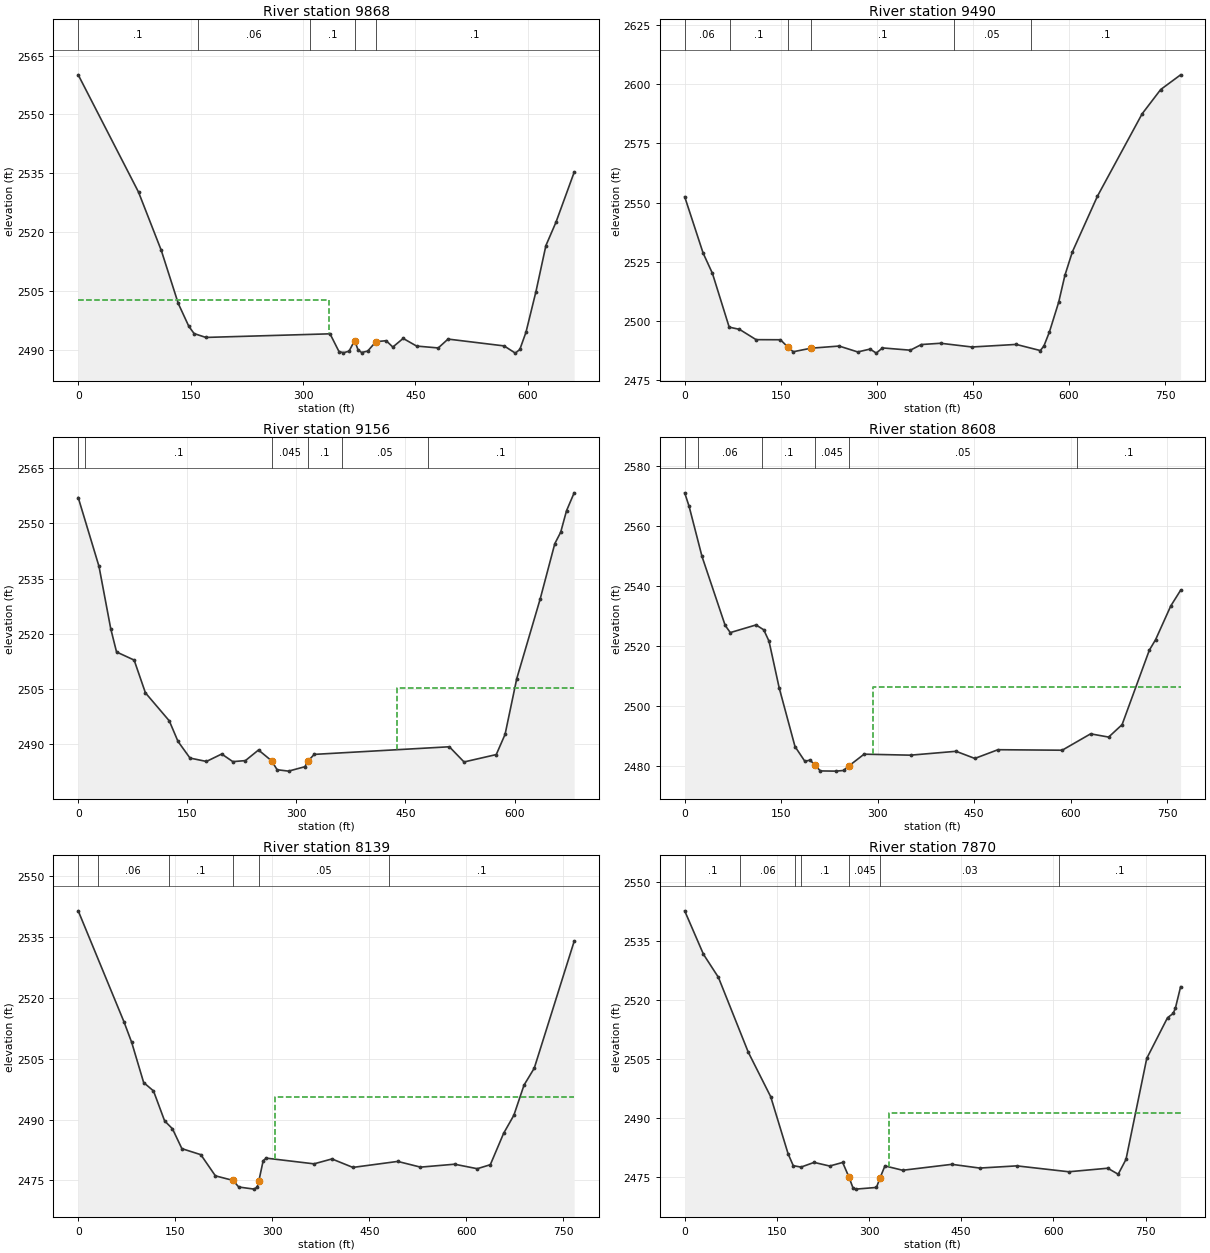
Type RM Length L Ch R = 1 ,9868    ,380.9,378.8,362.1
XS GIS Cut Line= 4
 2171906.3487608413403.6496721052171668.13196672413141.768958083
2171641.31285745413099.173902188 2171529.3036364412867.267486758
#Sta/Elev= 30
       0  2560.1    80.5 2530.21   110.9 2515.34   133.5 2501.85   147.7 2495.98
   154.7 2494.16   170.4 2493.18   336.1  2494.1     348 2489.59     354 2489.29
   361.4 2489.66   368.9 2492.36   373.6 2489.96   378.3 2489.34   386.3 2489.69
   397.3 2492.09     411 2492.35   419.9 2490.73   433.7 2492.93   451.6 2490.98
   480.5  2490.5   493.6 2492.76   568.4 2491.02   583.4 2489.18   589.4 2490.12
   597.6  2494.5   610.9 2504.85   624.2 2516.59   637.6 2522.52   661.9 2535.26
#Mann= 5 ,-1,0
       0      .1       0     160     .06       0     310      .1       0
   368.9    .045       0   397.3      .1       0
#XS Ineff= 2 , 0
          334.78 2502.61
Permanent Ineff=
       F       F
Bank Sta=368.9,397.3
XS Rating Curve= 0 ,0
Exp/Cntr(USF)=0,0
Exp/Cntr=0.3,0.1

Type RM Length L Ch R = 1 ,9490    ,326.6,333.7,334.5
XS GIS Cut Line= 2
2172148.05145969413112.1092342722171506.45670137412678.545367296
#Sta/Elev= 30
       0 2552.46    28.8 2528.64    43.3  2520.1    69.5 2497.36    85.6 2496.42
   111.5 2492.07   149.5 2492.03   161.32488.903   169.5 2486.96   197.1 2488.46
   241.2 2489.37   270.2 2486.88   289.5 2488.09   299.2 2486.38   308.8 2488.58
   352.3 2487.62   369.6 2490.01   399.6 2490.55   448.6 2488.97   517.7 2490.06
   555.3 2487.47   560.9 2489.37   569.6 2495.38     584 2507.91   593.7 2519.24
   605.3 2529.12   644.5 2552.67   714.3 2587.48   743.3 2597.75   774.4 2603.95
#Mann= 6 ,-1,0
       0     .06       0      70      .1       0   161.3    .045       0
   197.1      .1       0     420     .05       0     540      .1       0
Bank Sta=161.3,197.1
XS Rating Curve= 0 ,0
Exp/Cntr(USF)=0,0
Exp/Cntr=0.3,0.1

Type RM Length L Ch R = 1 ,9156    ,564.9,548,517.6
XS GIS Cut Line= 4
2172296.58153593412846.8563246632172145.09218961412830.028103111
 2171933.5875026412634.4847854712171693.78729556412606.634395036
#Sta/Elev= 30
       0 2557.05    28.6 2538.32    44.7 2521.42    52.7 2515.08    76.9 2512.88
    92.4 2503.98   125.2 2496.37   137.2 2490.78   153.7 2486.25   176.3 2485.33
   197.3 2487.35   212.6 2485.28   229.9 2485.56   247.9 2488.44   265.92485.508
   273.5 2483.08   289.2  2482.7   311.7  2483.9   315.62485.358   324.5 2487.25
   510.3 2489.32   530.5 2485.19   574.8  2487.2   586.9 2492.68     603 2507.85
   635.2 2529.49   655.3 2544.52   663.4 2547.63   671.4 2553.46   681.9 2558.33
#Mann= 6 ,-1,0
       0     .06       0      10      .1       0   265.9    .045       0
   315.6      .1       0  362.42     .05       0  480.47      .1       0
#XS Ineff= 2 , 0
                          438.47         2505.26
Permanent Ineff=
       F       F
Bank Sta=265.9,315.6
XS Rating Curve= 0 ,0
Exp/Cntr(USF)=0,0
Exp/Cntr=0.3,0.1

Type RM Length L Ch R = 1 ,8608    ,453.3,468.6,482.6
XS GIS Cut Line= 3
2172403.07122856412258.6126908482171726.50428688412271.072141931
2171647.31116776412322.164476846
#Sta/Elev= 30
       0 2570.95     6.9 2566.43    26.9 2549.76    62.9 2526.78    70.9 2524.36
   110.9 2526.91   122.9 2525.29   131.1 2521.49   146.9 2505.94   171.5 2486.37
   186.9 2481.43   194.9 2481.88   202.9 2480.09   210.9 2478.25   234.9 2478.18
   246.9 2478.39   254.9 2479.86   278.9 2483.83   351.1  2483.5   421.8 2484.79
     451 2482.41     487 2485.32   586.8 2485.15     631 2490.61     659 2489.53
   679.9 2493.67   722.3 2518.52     732 2522.01   755.6 2533.25   770.9 2538.48
#Mann= 6 ,-1,0
       0      .1       0      20     .06       0     120      .1       0
   202.9    .045       0   254.9     .05       0     610      .1       0
#XS Ineff= 2 , 0
                          292.95         2506.22
Permanent Ineff=
       F       F
Bank Sta=202.9,254.9
XS Rating Curve= 0 ,0
Exp/Cntr(USF)=0,0
Exp/Cntr=0.3,0.1

Type RM Length L Ch R = 1 ,8139    ,273.3,269.1,263
XS GIS Cut Line= 3
2172507.79211769411960.6070106982171953.70205323411640.174493814
2171857.14227101411558.064065448
#Sta/Elev= 30
       0 2541.51    70.8  2514.1    82.7 2509.03   101.2 2499.12   116.4 2497.06
   133.6 2489.66   145.7 2487.72   160.3 2482.81   189.6 2481.32   212.1  2476.1
   239.4 2474.97   248.2 2473.34   272.2 2472.82   276.8 2473.34   279.32474.858
     286 2479.84   290.7 2480.47   364.6 2479.06   392.3 2480.27   424.7 2478.18
     494 2479.66   529.2 2478.25   581.9 2478.97     617 2477.86   637.2 2478.85
   657.8 2486.61   673.6 2491.06   689.3  2498.5   705.1 2502.67   766.8 2533.98
#Mann= 6 ,-1,0
       0      .1       0      30     .06       0     140      .1       0
   239.4    .045       0   279.3     .05       0     480      .1       0
#XS Ineff= 2 , 0
                          304.54         2495.61
Permanent Ineff=
       F       F
Bank Sta=239.4,279.3
XS Rating Curve= 0 ,0
Exp/Cntr(USF)=0,0
Exp/Cntr=0.3,0.1

Type RM Length L Ch R = 1 ,7870    ,80.9,90.1,103.1
XS GIS Cut Line= 3
2172674.39701764411655.7345171362172507.42032821411629.170043817
2171904.02729139411421.714156943
#Sta/Elev= 30
       0 2542.75    30.6 2531.68    54.9 2525.82   103.5 2506.77     140 2495.44
   168.3 2480.92   176.7 2477.89   189.4 2477.53   210.6 2478.72     236  2477.8
   257.1 2478.71   267.5 2474.92     274  2472.2   278.3 2471.92   312.1 2472.35
   317.72474.697   325.9 2477.83   354.8 2476.72   434.8 2478.23   480.1 2477.28
   540.5 2477.84   625.1 2476.34   688.5 2477.24   705.5 2475.71   718.2 2479.49
     752  2505.2   785.8 2515.55   794.9 2516.62   798.5 2517.93   807.1 2523.44
#Mann= 7 ,-1,0
       0      .1       0      90     .06       0  179.08     .07       0
  189.08      .1       0   267.5    .045       0   317.7     .03       0
  609.08      .1       0
#XS Ineff= 2 , 0
                          332.37         2491.35
Permanent Ineff=
       F       F
Bank Sta=267.5,317.7
XS Rating Curve= 0 ,0
Exp/Cntr(USF)=0,0
Exp/Cntr=0.3,0.1

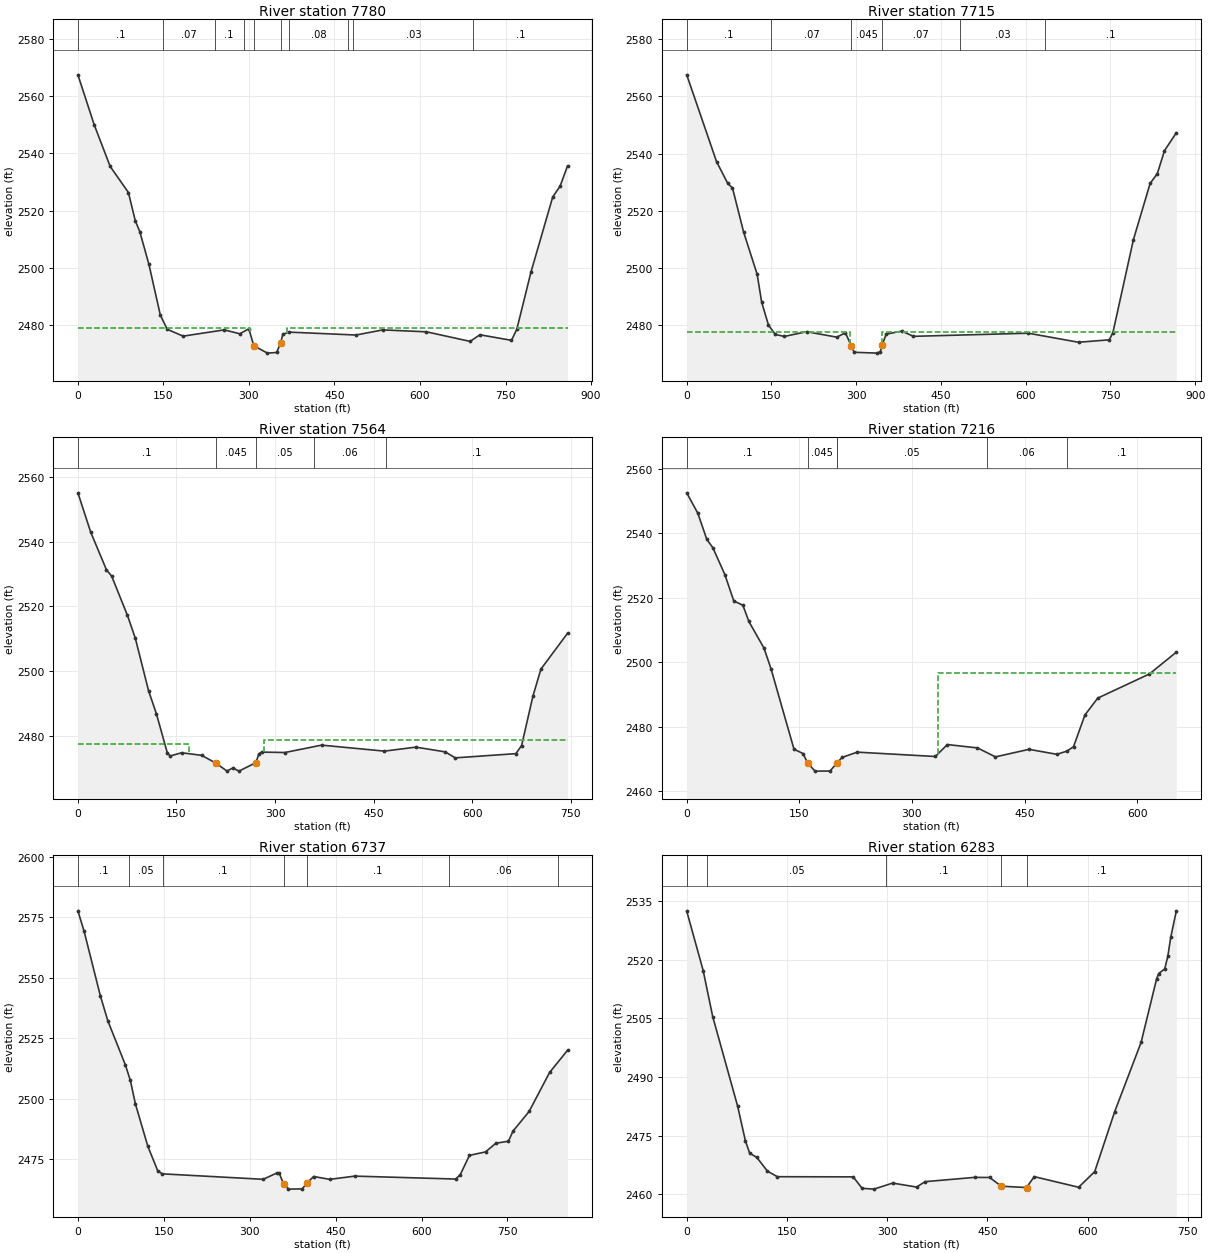
Type RM Length L Ch R = 1 ,7780    ,59.1,64.9,57.8
XS GIS Cut Line= 4
 2172728.7909392 411541.886774342172458.08630633 411540.62179942
2172359.41826257411452.0735550232171931.85673963411295.216664948
#Sta/Elev= 30
       0 2567.46    28.6 2550.02    56.6 2535.48    88.6 2526.37   100.6 2516.55
   108.6 2512.67   124.5 2501.33   144.6 2483.55   156.6 2478.62   184.6 2476.22
   256.6 2478.41     284 2477.05   299.8 2478.79   308.5 2472.86   332.4 2470.29
   348.5 2470.52   355.5 2473.76   359.3 2476.83     370 2477.63   487.7 2476.61
   534.6  2478.4   611.3 2477.73   687.9 2474.39     705  2476.7   760.4 2474.76
   769.7 2478.55   794.6 2498.59   832.8 2524.84   845.6 2528.53   858.7 2535.64
#Mann= 10 ,-1,0
       0      .1       0     150     .07       0     240      .1       0
  290.71     .07       0   308.5    .045       0   355.5     .07       0
  370.71     .08       0  473.28     .07       0  483.28     .03       0
  693.28      .1       0
#XS Ineff= 2 , 0
          301.47    2479  366.15            2479
Permanent Ineff=
       F       F
Bank Sta=308.5,355.5
XS Rating Curve= 0 ,0
Exp/Cntr(USF)=0,0
Exp/Cntr=0.5,0.3

Type RM Length L Ch R = 1 ,7715    ,163.5,151.3,144.6
XS GIS Cut Line= 4
2172728.89011819411518.4592544992172520.69997752411515.774262418
2172399.41333381411417.4489877352171924.33026835411254.145095824
#Sta/Elev= 30
       0 2567.53    52.7 2537.24    72.7 2529.56      81    2528   100.7 2512.59
   124.7 2497.81   132.7 2488.05   144.7 2480.09   156.7 2476.84   172.7 2476.12
   212.3 2477.77   265.5 2475.88     281 2477.38   291.3 2472.77   296.4 2470.59
   337.6 2470.29   342.8 2470.82   345.7 2473.01   353.1 2476.92   380.5 2477.98
   401.4 2476.16   604.6 2477.25   693.5 2474.09     748 2474.94   754.3 2477.39
   790.7 2509.93   820.3 2529.59     833    2533   845.7 2541.02   866.7 2547.29
#Mann= 6 ,-1,0
       0      .1       0     150     .07       0   291.3    .045       0
   345.7     .07       0  484.34     .03       0  634.34      .1       0
#XS Ineff= 2 , 0
          288.98 2477.79  346.54         2477.52
Permanent Ineff=
       F       F
Bank Sta=291.3,345.7
XS Rating Curve= 0 ,0
Exp/Cntr(USF)=0,0
Exp/Cntr=0.5,0.3

Type RM Length L Ch R = 1 ,7564    ,359.2,347.5,339.2
XS GIS Cut Line= 3
2172727.52596428411357.2004360262172598.49852245411350.875561426
2172031.78975831411109.265351714
#Sta/Elev= 30
       0 2555.11    19.4    2543    43.4 2531.34    51.4 2529.35    75.4 2517.22
    87.5 2510.07   107.5 2493.94   119.5 2486.77   136.1 2474.69   140.4 2473.72
   157.8 2474.72   188.2 2473.93     210 2471.53   226.8 2469.07   236.1 2470.05
     245 2469.04   270.9 2471.66   275.5 2474.39   279.6 2474.92   315.2  2474.8
   370.9 2477.08   466.5 2475.23   514.4 2476.46   559.1    2475   574.3 2473.14
   666.6 2474.45   675.3 2476.96   692.6 2492.26   704.7 2500.58   745.2 2511.67
#Mann= 5 ,-1,0
       0      .1       0     210    .045       0   270.9     .05       0
  359.18     .06       0  469.18      .1       0
#XS Ineff= 2 , 0
          168.44 2477.35  283.04         2478.57
Permanent Ineff=
       F       F
Bank Sta=210,270.9
XS Rating Curve= 0 ,0
Exp/Cntr(USF)=0,0
Exp/Cntr=0.5,0.3

Type RM Length L Ch R = 1 ,7216    ,478.4,478.8,480.1
XS GIS Cut Line= 3
2172786.90765102410993.9526494972172340.63818247411017.606508254
2172160.86885592410918.260301475
#Sta/Elev= 30
       0 2552.56    14.8 2546.22    26.8 2538.09    34.8 2535.53    50.8  2527.2
    62.7 2519.03    74.8 2517.69    82.8 2512.65   102.9  2504.4   112.2 2498.05
   142.9 2473.04   154.9 2471.69   161.32468.659     171 2466.23     191 2466.27
   199.7 2468.66     207 2470.48   227.1 2472.12   331.2 2470.77   347.2 2474.47
   387.3 2473.44   411.3 2470.65     456 2472.99   493.1 2471.45   506.4 2472.42
   515.3 2473.81   530.5 2483.65   547.6 2488.88   616.5 2496.38   652.3 2503.14
#Mann= 6 ,-1,0
       0      .1       0   161.3    .045       0   199.7      .1       0
     200     .05       0     400     .06       0   506.9      .1       0
#XS Ineff= 2 , 0
                          334.32          2496.7
Permanent Ineff=
       F       F
Bank Sta=161.3,199.7
XS Rating Curve= 0 ,0
Exp/Cntr(USF)=0,0
Exp/Cntr=0.3,0.1

Type RM Length L Ch R = 1 ,6737    ,442.9,454.2,463.5
XS GIS Cut Line= 3
 2172920.0956401410577.5541001042172793.78403434410522.204070613
  2172077.072114410537.815617392
#Sta/Elev= 30
       0 2577.66    10.9 2569.15    39.2 2542.52    52.3 2532.16    82.9 2513.94
    91.6 2507.52   100.4 2497.82   122.2 2480.22   139.5 2470.09   147.5  2468.9
   323.6 2466.64   347.6 2469.29   351.6 2469.05     359 2464.81   367.6 2462.58
   391.6 2462.68   399.6 2465.05   411.6  2467.8   439.6 2466.62   483.6 2467.96
   659.6 2466.75   667.6 2468.57   683.6 2476.54   711.7 2477.98   729.7 2481.55
   751.7  2482.4   759.7  2486.6   787.7 2494.68   823.6 2510.86   854.8 2519.98
#Mann= 7 ,-1,0
       0      .1       0      90     .05       0  147.91      .1       0
     359    .045       0   399.6      .1       0  647.91     .06       0
  837.91      .1       0
Bank Sta=359,399.6
XS Rating Curve= 0 ,0
Exp/Cntr(USF)=0,0
Exp/Cntr=0.3,0.1

Type RM Length L Ch R = 1 ,6283    ,306.1,310.3,312.9
XS GIS Cut Line= 4
2172998.43620424410353.1425565822172940.85208102410271.467522731
2172829.81872162410188.6529267662172384.64440418 409973.51410493
#Sta/Elev= 30
       0 2532.47    24.6 2517.25    38.9 2505.45    76.2 2482.52    87.7 2473.72
    94.2 2470.48   104.9 2469.39   120.7  2465.9   135.7 2464.45   249.2 2464.41
   262.5 2461.48   280.3 2461.27   308.2 2462.82   344.1  2461.8   356.7 2463.18
     431 2464.28   453.5 2464.25   470.82462.018   508.6 2461.68   520.2 2464.47
   586.6 2461.75   610.7 2465.75   640.6  2481.1   680.1 2498.83   703.5  2515.2
   706.5 2516.48   715.5 2517.68   720.1 2520.87   724.6 2525.85   732.9 2532.54
#Mann= 5 ,-1,0
       0      .1       0      30     .05       0  298.45      .1       0
   470.8    .045       0   508.6      .1       0
Bank Sta=470.8,508.6
XS Rating Curve= 0 ,0
Exp/Cntr(USF)=0,0
Exp/Cntr=0.3,0.1

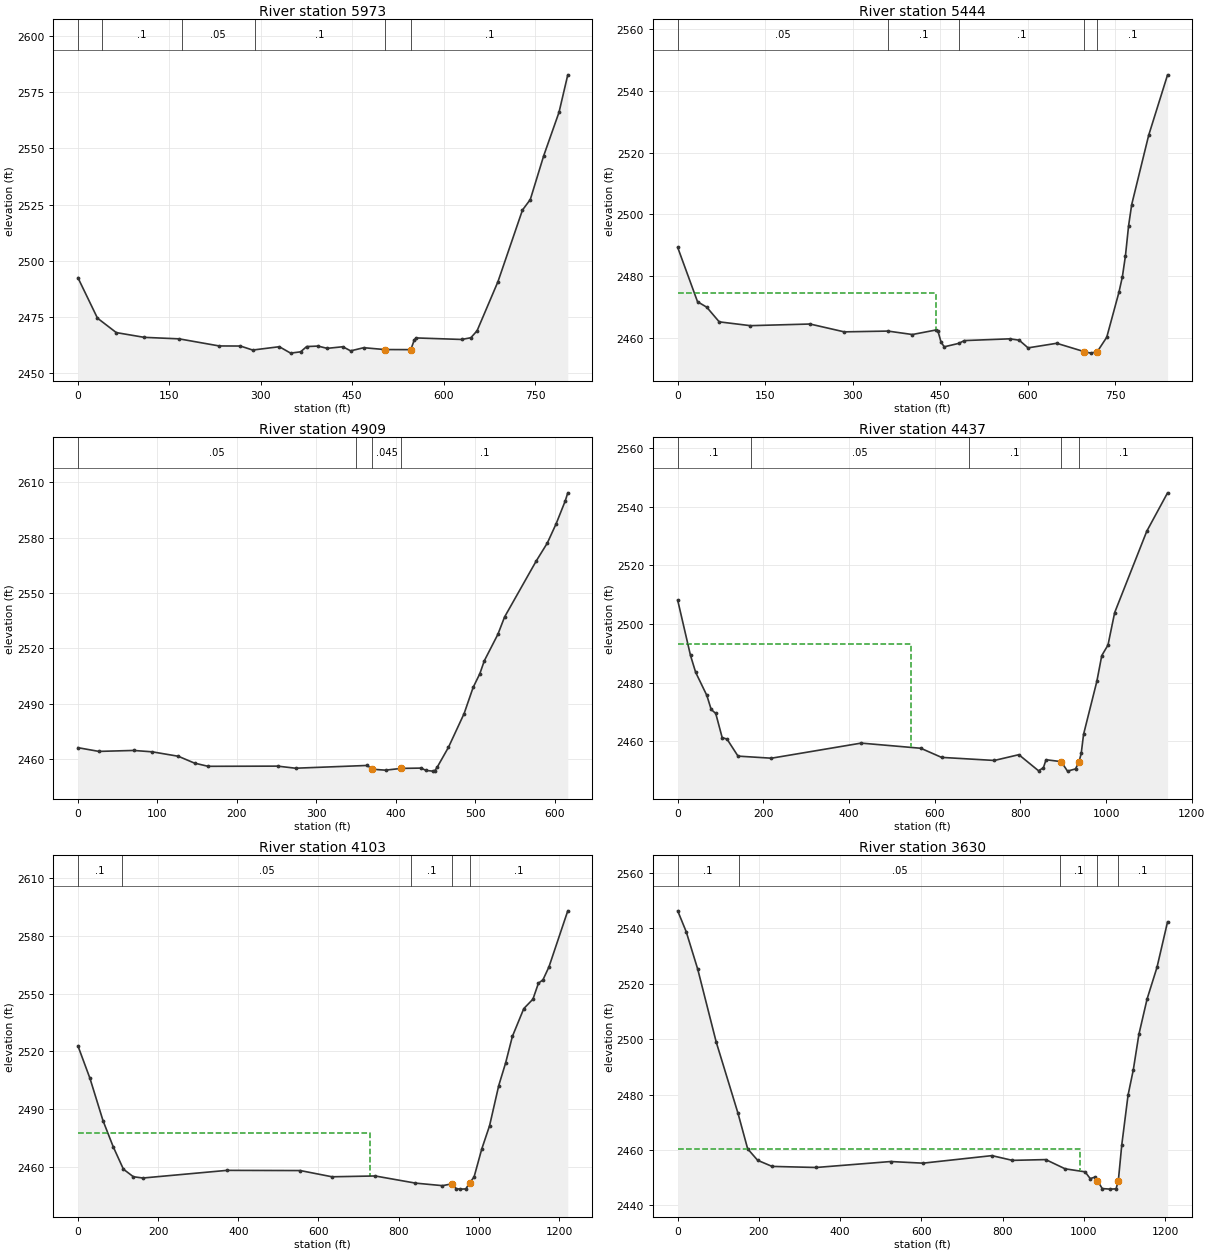
Type RM Length L Ch R = 1 ,5973    ,523.8,529.3,533.1
XS GIS Cut Line= 2
  2173209.178497410148.3630326492172564.57331778409668.458736229
#Sta/Elev= 30
       0 2492.55    32.1 2474.56      63 2468.15   108.8 2466.04   166.1 2465.37
   231.7 2462.22   266.6 2462.18   286.7  2460.4   330.4 2461.88   348.9 2459.03
   365.3 2459.61   375.3 2461.95   393.8 2462.16   408.9 2461.15   434.6 2461.86
   447.4 2460.04   468.9 2461.44   503.2 2460.62   546.1 2460.58   551.8  2464.9
   554.7 2465.78   629.6  2465.1   644.6 2465.87   654.8 2468.96   689.1 2490.81
   729.3 2522.61   742.1 2527.26   764.2 2546.79   789.2    2566   803.6 2582.66
#Mann= 6 ,-1,0
       0     .05       0      40      .1       0     170     .05       0
     290      .1       0   503.2    .045       0   546.1      .1       0
Bank Sta=503.2,546.1
XS Rating Curve= 0 ,0
Exp/Cntr(USF)=0,0
Exp/Cntr=0.3,0.1

Type RM Length L Ch R = 1 ,5444    ,537.4,534.4,533.7
XS GIS Cut Line= 2
2173543.10548411410018.3217724592172984.33265886409391.315379602
#Sta/Elev= 30
       0 2489.36      34 2471.82    49.8 2470.06    71.2 2465.32   124.6 2464.09
   226.9 2464.62   285.5 2462.09   360.5 2462.34   402.4 2461.23   443.3 2462.71
   446.2 2462.33   451.6 2458.74     457 2457.26   481.7 2458.36   491.4 2459.27
   569.5 2459.84   585.5  2459.4   600.7 2456.92   649.8  2458.4     697  2455.7
   708.3 2455.22   719.5 2455.73   735.6 2460.34   756.5 2474.86   762.4 2479.86
   767.7 2486.68   773.1  2496.4   778.4 2503.19   807.5 2525.57   839.9  2545.1
#Mann= 5 ,-1,0
       0     .05       0   360.5      .1       0   481.7      .1       0
     697    .045       0   719.5      .1       0
#XS Ineff= 2 , 0
           443.2 2474.49
Permanent Ineff=
       F       F
Bank Sta=697,719.5
XS Rating Curve= 0 ,0
Exp/Cntr(USF)=0,0
Exp/Cntr=0.3,0.1

Type RM Length L Ch R = 1 ,4909    ,473.1,472.1,471.3
XS GIS Cut Line= 3
2173744.06219962409551.0865751372173679.23310525409372.368531196
2173377.86542331409071.000849256
#Sta/Elev= 30
       0 2466.13    26.4 2464.11    70.1 2464.63    93.5 2463.88   126.3 2461.48
   146.7 2457.76   163.8 2456.03   251.2 2456.13   273.8    2455   364.2  2456.5
   369.9 2454.46     387 2453.94   406.7  2454.9     432 2455.07   437.8 2453.81
   446.3 2453.42     449  2453.7   451.9 2455.45   466.2 2466.34   485.9 2484.64
   497.2 2498.76   505.7 2506.27   511.3 2513.25   528.4 2527.61   536.8 2536.99
   576.4 2567.17   590.6 2577.09   601.8 2587.64   613.1 2599.88   616.3 2604.27
#Mann= 4 ,-1,0
       0     .05       0  350.11      .1       0   369.9    .045       0
   406.7      .1       0
Bank Sta=369.9,406.7
XS Rating Curve= 0 ,0
Exp/Cntr(USF)=0,0
Exp/Cntr=0.3,0.1

Type RM Length L Ch R = 1 ,4437    ,331.4,333.8,336.1
XS GIS Cut Line= 2
2174388.41790978409415.1135939042173509.27574973408683.778420716
#Sta/Elev= 30
       0 2508.12    29.9 2489.27    41.9 2483.53      68 2475.64    78.2 2470.84
    88.8  2469.5   103.8 2461.26   115.2 2460.72   140.8 2454.93   218.8 2454.22
   428.3 2459.37   567.5 2457.61     616  2454.5   739.2 2453.45   796.4 2455.42
   842.3 2449.94   853.7 2450.95   859.9  2453.7   895.2 2453.05     910 2449.81
   928.7 2450.57   936.9 2452.95   942.1 2455.94   947.5 2462.37   978.5 2480.44
     990 2489.24  1004.5 2492.82  1020.1  2503.9  1095.1 2531.68  1143.6 2544.76
#Mann= 5 ,-1,0
       0      .1       0     170     .05       0     680      .1       0
   895.2    .045       0   936.9      .1       0
#XS Ineff= 2 , 0
          544.93 2493.18
Permanent Ineff=
       F       F
Bank Sta=895.2,936.9
XS Rating Curve= 0 ,0
Exp/Cntr(USF)=0,0
Exp/Cntr=0.3,0.1

Type RM Length L Ch R = 1 ,4103    ,468.1,473,467.9
XS GIS Cut Line= 2
2174545.29420796409244.5639433712173687.15224245408374.756369577
#Sta/Elev= 30
       0 2522.91    30.1 2505.98    62.6 2484.05      88 2470.52   113.5 2458.86
   138.3 2454.93   162.1 2454.27   371.8 2458.24   554.7 2458.14   633.8 2454.91
   741.4 2455.33     842 2451.62   909.4  2450.3   933.8 2451.29   943.1 2448.77
   953.6  2448.5   967.7 2448.61   976.9 2451.76   988.1 2454.76  1007.3 2469.31
  1026.8 2481.41  1049.7 2502.28  1066.8 2513.96  1083.7 2527.78  1112.2 2542.23
    1135 2547.13  1148.7 2555.41    1160 2557.16  1174.9 2563.86  1221.9 2592.98
#Mann= 5 ,-1,0
       0      .1       0     110     .05       0     830      .1       0
   933.8    .045       0   976.9      .1       0
#XS Ineff= 2 , 0
          729.36 2477.44
Permanent Ineff=
       F       F
Bank Sta=933.8,976.9
XS Rating Curve= 0 ,0
Exp/Cntr(USF)=0,0
Exp/Cntr=0.3,0.1

Type RM Length L Ch R = 1 ,3630    ,393.1,392,389
XS GIS Cut Line= 3
 2174640.9035235409205.4357182972174519.95233942408656.458876557
2174079.96483094408186.089188079
#Sta/Elev= 30
       0 2546.32      21 2538.76    49.4 2525.22    94.8 2498.98   148.5 2473.24
   172.3 2460.41   196.9 2456.28   232.4 2454.08   340.8 2453.69   524.4 2455.84
   603.9 2455.25   773.7 2457.97   824.1 2456.26   906.2 2456.54   954.1  2453.2
    1003 2452.13  1015.8 2449.67  1028.4 2450.28  1033.52448.917  1045.4 2446.08
  1065.2 2445.88  1079.4 2445.99    1085 2448.96  1093.5 2461.93  1108.9 2479.79
  1121.8 2488.92  1135.6 2501.74  1155.8 2514.52  1180.1 2525.89  1206.2 2542.37
#Mann= 5 ,-1,0
       0      .1       0     150     .05       0  942.14      .1       0
  1033.5    .045       0    1085      .1       0
#XS Ineff= 2 , 0
          990.23 2460.44
Permanent Ineff=
       F       F
Bank Sta=1033.5,1085
XS Rating Curve= 0 ,0
Exp/Cntr(USF)=0,0
Exp/Cntr=0.3,0.1