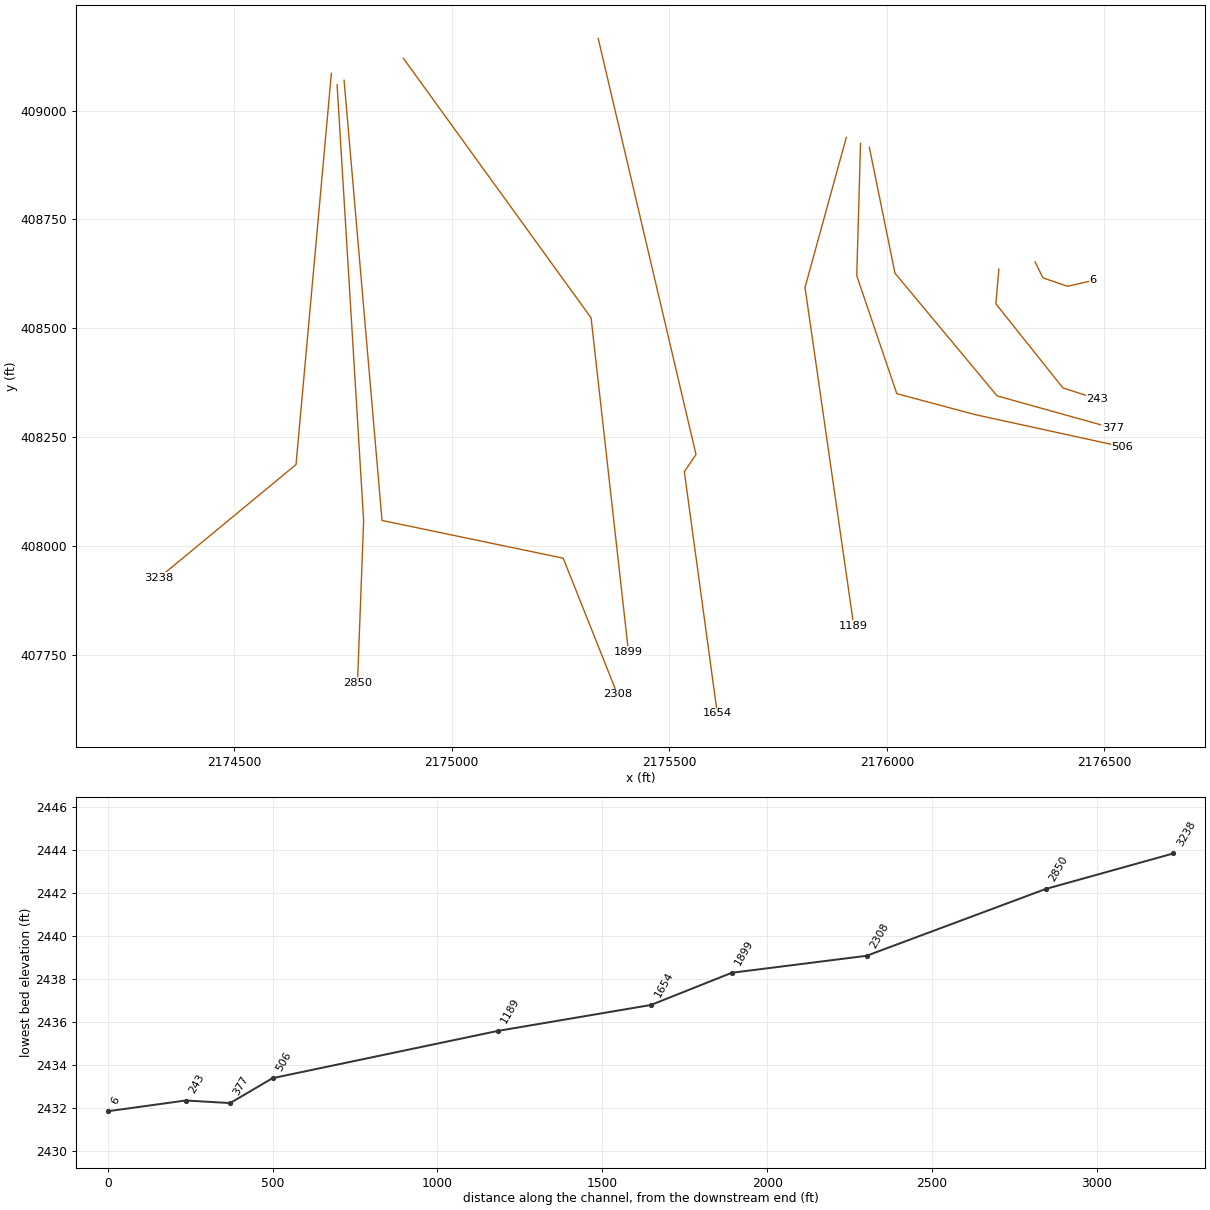
HEC-RAS study HLLSCK.prj: HLLSCK

--- HLLSCK.g01 (geometry) --- (continued)

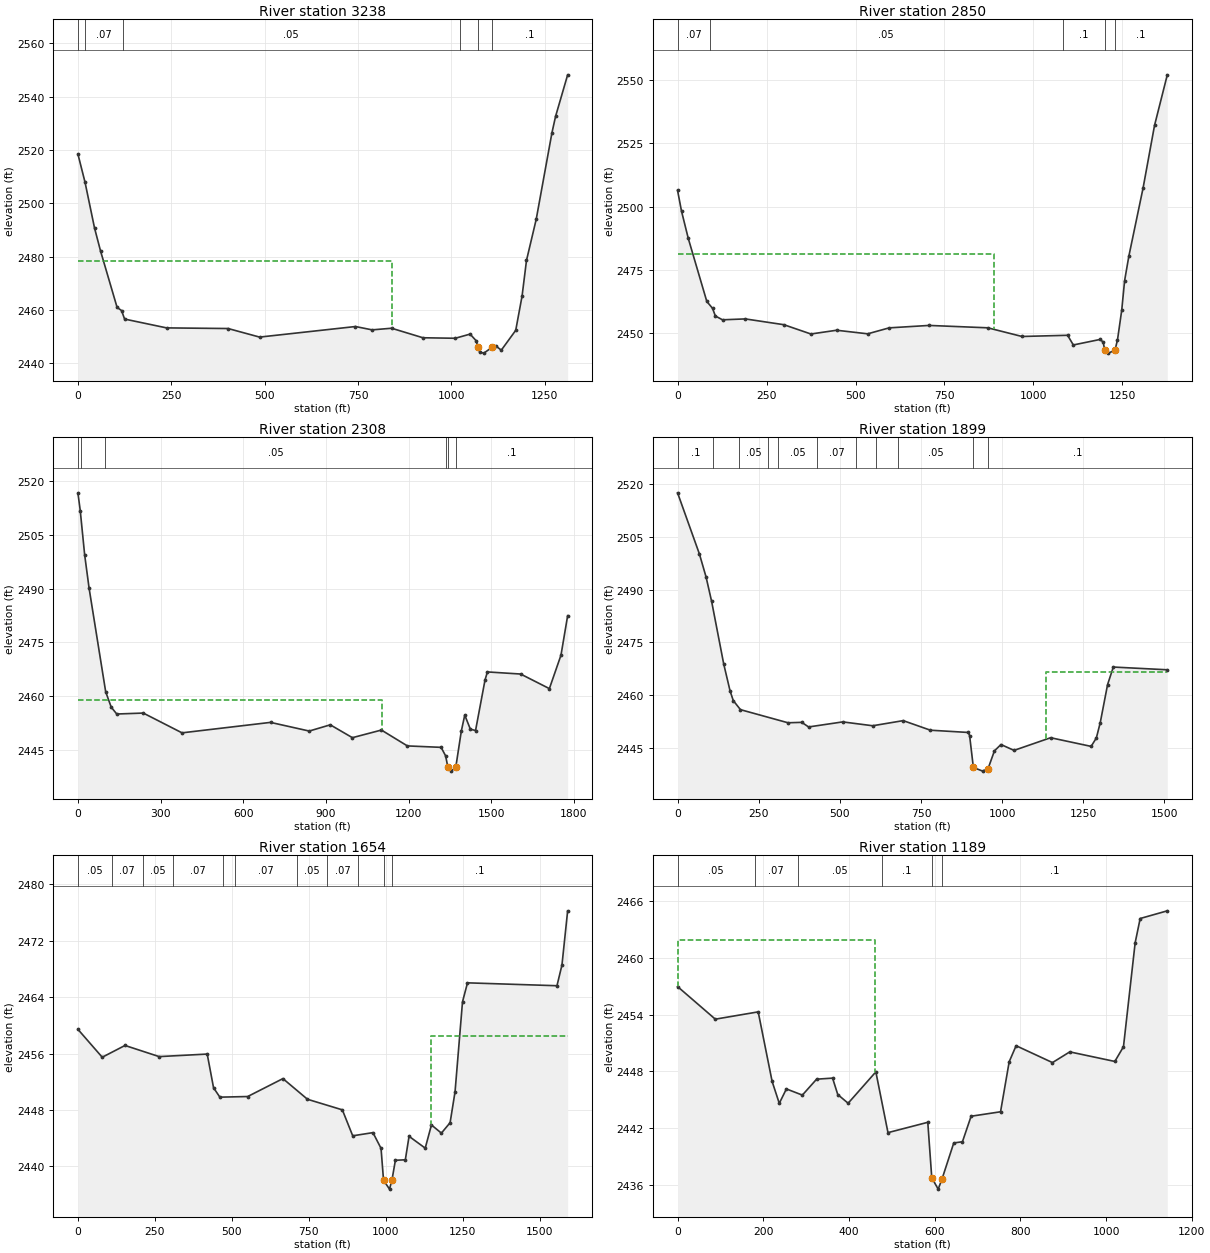
Type RM Length L Ch R = 1 ,3238    ,364.7,388,406.6
XS GIS Cut Line= 3
2174723.41986465409085.6365430422174642.15249325408186.650191198
2174327.22269696407926.369818928
#Sta/Elev= 30
       0 2518.47      19 2507.95    44.6  2490.7    60.7 2482.09   104.9    2461
   116.9  2459.8     125 2456.62   237.4 2453.31   402.1 2453.07   486.4 2449.86
   743.1 2453.82   787.7 2452.57   839.9 2453.18   923.8 2449.61  1010.2 2449.42
    1050 2450.98  1066.1 2448.52  1071.3 2445.99  1075.6 2444.18  1086.8 2443.85
  1109.7 2446.09  1118.2 2446.64  1133.5 2444.95  1172.2  2452.4  1189.2 2465.27
    1201  2478.6    1227 2493.99  1269.1 2526.41  1278.8 2532.56  1311.2 2548.17
#Mann= 6 ,-1,0
       0      .1       0      20     .07       0     120     .05       0
 1022.65     .12       0  1071.3    .045       0  1109.7      .1       0
#XS Ineff= 2 , 0
             840 2478.42
Permanent Ineff=
       F       F
Bank Sta=1071.3,1109.7
XS Rating Curve= 0 ,0
Exp/Cntr(USF)=0,0
Exp/Cntr=0.3,0.1

Type RM Length L Ch R = 1 ,2850    ,471.6,542.9,573.2
XS GIS Cut Line= 3
2174736.54587231409059.2360265212174797.51533856 408058.01127102
2174783.44154259407685.258822746
#Sta/Elev= 30
       0  2506.4    11.1 2498.22    30.1 2487.46    82.2 2462.58    98.2 2459.88
   106.3 2456.83   126.3 2455.34   190.4 2455.69   298.6 2453.41   374.7 2449.74
   446.9 2451.22   534.2 2449.81   594.6 2452.16   706.7 2453.12   871.7 2452.18
   967.8 2448.76    1096 2449.23    1112 2445.41    1188 2447.61    1196 2446.46
  1200.1 2443.54  1209.6 2442.19  1228.9 2443.26  1236.1 2447.37  1248.1  2459.2
  1256.1 2470.76  1268.1 2480.49  1308.1 2507.39  1340.2 2532.04  1376.1 2552.01
#Mann= 5 ,-1,0
       0     .07       0      90     .05       0 1083.08      .1       0
  1200.1    .045       0  1228.9      .1       0
#XS Ineff= 2 , 0
           888.7 2481.48
Permanent Ineff=
       F       F
Bank Sta=1200.1,1228.9
XS Rating Curve= 0 ,0
Exp/Cntr(USF)=0,0
Exp/Cntr=0.3,0.1

Type RM Length L Ch R = 1 ,2308    ,452,408.6,367.1
XS GIS Cut Line= 4
2174752.62242849409069.6207678992174839.79481515408058.140660834
2175256.13983953407971.4646142962175380.71284861 407658.63714146
#Sta/Elev= 30
       0 2516.79     8.5 2511.84    24.5 2499.48    40.6 2490.15   100.8 2461.24
   120.9 2456.94     141 2455.03   237.3 2455.29   377.8 2449.77     699 2452.69
   839.5 2450.27   915.8 2452.01   996.1 2448.42  1101.4 2450.55  1195.6 2446.12
    1318 2445.72  1334.3 2443.35  1342.5 2440.22    1355 2439.08  1371.4 2440.25
  1391.5 2450.32  1403.8 2454.72  1424.2 2450.79    1443 2450.42  1477.4 2464.54
    1486 2466.78  1606.6 2466.19  1710.9 2462.12    1753 2471.46  1777.2 2482.49
#Mann= 6 ,-1,0
       0      .1       0      10     .07       0     100     .05       0
 1335.23      .1       0  1342.5    .045       0  1371.4      .1       0
#XS Ineff= 2 , 0
         1103.94 2459.02
Permanent Ineff=
       F       F
Bank Sta=1342.5,1371.4
XS Rating Curve= 0 ,0
Exp/Cntr(USF)=0,0
Exp/Cntr=0.3,0.1

Type RM Length L Ch R = 1 ,1899    ,272.2,245.2,229
XS GIS Cut Line= 3
2174888.72452195409120.3067222342175320.20430357408523.739834057
 2175406.1825615407755.935360557
#Sta/Elev= 30
       0  2517.6    67.3 2500.18    87.8 2493.63     105 2486.64   142.2 2468.83
   161.8 2461.14   171.7 2458.39   193.8 2455.81   340.3 2452.07   382.8 2452.19
   403.7 2450.88   508.9 2452.32   601.2 2451.22   695.2 2452.68   779.1 2449.95
   895.8 2449.31   899.8 2448.41   911.4 2439.33   940.1 2438.29   956.7    2439
   976.3 2444.07   996.4 2445.87  1036.7  2444.2  1149.4 2447.81  1274.2 2445.34
  1290.3 2447.74  1302.3  2452.1  1324.9 2462.96  1342.6 2467.95  1508.9 2467.17
#Mann= 11 ,-1,0
       0      .1       0     110     .07       0     190     .05       0
     280     .07       0     310     .05       0     430     .07       0
     550     .05       0     610     .07       0     680     .05       0
   911.4    .045       0   956.7      .1       0
#XS Ineff= 2 , 0
                         1134.69          2466.4
Permanent Ineff=
       F       F
Bank Sta=911.4,956.7
XS Rating Curve= 0 ,0
Exp/Cntr(USF)=0,0
Exp/Cntr=0.3,0.1

Type RM Length L Ch R = 1 ,1654    ,439.6,464.8,487.8
XS GIS Cut Line= 4
2175336.47843669409166.078209211 2175561.3170549408209.607884583
2175534.49794564408170.1680180142175610.22248945407614.854696712
#Sta/Elev= 30
       0 2459.45      79 2455.49     153 2457.16   263.9 2455.58     420 2455.94
   440.6 2451.16   461.1 2449.83   551.5 2449.92   665.9 2452.46   745.7 2449.53
   858.9 2448.03   892.6 2444.35   958.3  2444.8   984.6 2442.57   992.7 2438.04
  1012.1 2436.79  1020.1 2438.09  1031.2 2440.88  1063.5 2440.95  1075.6 2444.28
  1128.1  2442.6  1148.3 2445.89  1180.6 2444.73  1208.9 2446.21    1225  2450.6
  1249.2 2463.35  1265.4 2466.04    1556 2465.63  1572.2 2468.56  1590.7 2476.25
#Mann= 11 ,-1,0
       0     .05       0     110     .07       0     210     .05       0
     310     .07       0     470     .05       0     510     .07       0
     710     .05       0     810     .07       0     910      .1       0
   992.7    .045       0  1020.1      .1       0
#XS Ineff= 2 , 0
                         1147.05         2458.54
Permanent Ineff=
       F       F
Bank Sta=992.7,1020.1
XS Rating Curve= 0 ,0
Exp/Cntr(USF)=0,0
Exp/Cntr=0.3,0.1

Type RM Length L Ch R = 1 ,1189    ,607.5,683,613.5
XS GIS Cut Line= 3
2175906.64343756408938.0750962412175811.82999833408593.686181355
2175923.83921939  407815.9320126
#Sta/Elev= 30
       0 2456.95    88.1 2453.51   188.2 2454.28   220.7 2446.94   237.4 2444.63
     254 2446.15   291.3  2445.5   324.5 2447.18   361.8 2447.29   373.9 2445.56
   398.1 2444.64   462.8 2447.95   491.1 2441.54     584 2442.63   593.32436.766
   608.3 2435.58   617.1 2436.63   644.6 2440.45   664.9 2440.58   685.1 2443.27
   753.8 2443.74     774 2449.02   790.1 2450.71     875 2448.93   915.4 2450.06
  1020.5 2449.05  1040.7  2450.6    1068 2461.58  1079.7 2464.13    1143 2464.94
#Mann= 6 ,-1,0
       0     .05       0     180     .07       0     280     .05       0
   477.2      .1       0   593.3    .045       0   617.1      .1       0
#XS Ineff= 2 , 0
          460.29 2461.88
Permanent Ineff=
       F       F
Bank Sta=593.3,617.1
XS Rating Curve= 0 ,0
Exp/Cntr(USF)=0,0
Exp/Cntr=0.3,0.1

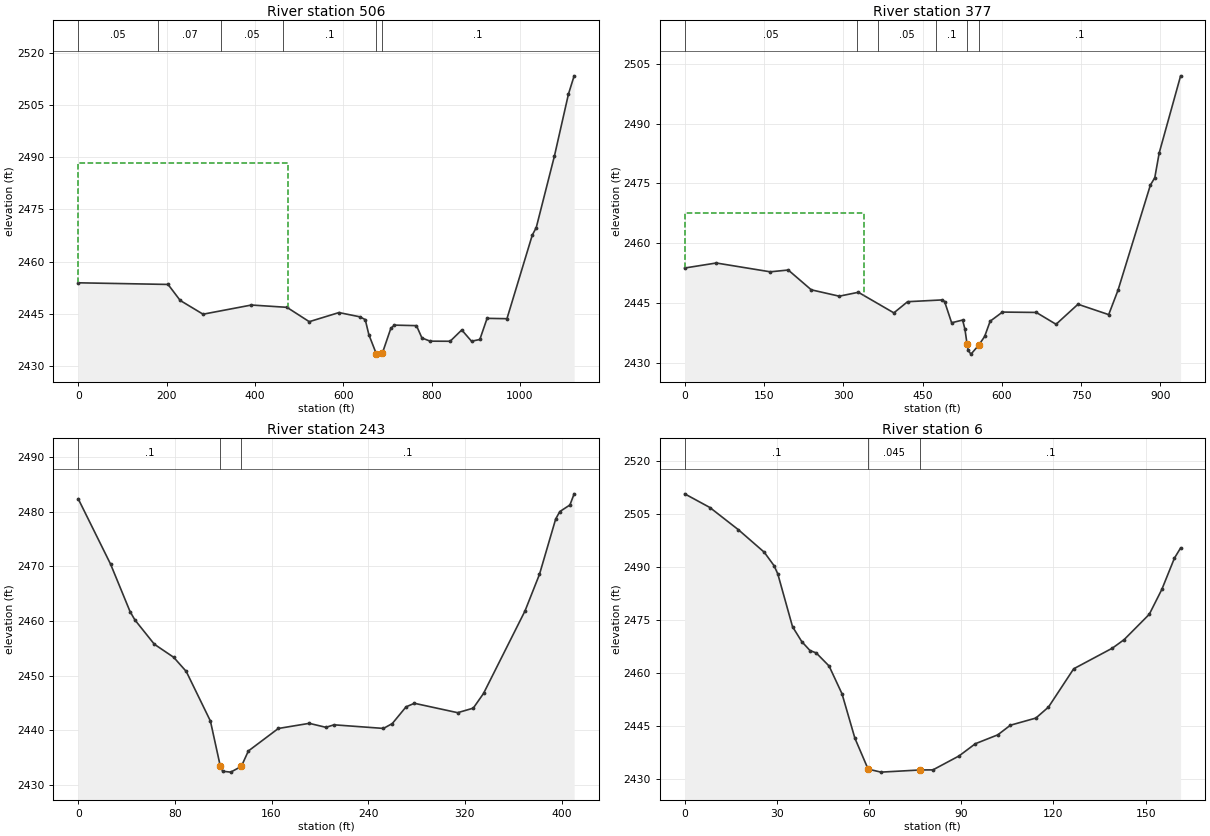
Type RM Length L Ch R = 1 ,506     ,146.4,128.5,108.7
XS GIS Cut Line= 5
2175939.38863924408924.4854734142175930.71201811408620.596782456
2176022.64611909408349.5944006982176200.99679286408301.788001131
2176540.78336521 408227.63819786
#Sta/Elev= 30
       0 2453.89   203.4 2453.42   230.8 2448.82   282.6 2444.86   392.1  2447.5
   472.4 2446.84     523 2442.71   590.2 2445.33   637.5 2444.11   649.7 2443.31
     658 2438.93   674.6 2433.54   686.5 2433.38   688.32433.592   707.7 2440.82
   715.9 2441.72   765.7 2441.57     778 2438.04   796.4 2437.11   841.9 2437.08
   868.2 2440.33   890.3 2437.09   909.1 2437.59   925.5 2443.67   970.5 2443.57
  1027.8  2467.6  1036.8 2469.77  1077.9 2490.32  1109.7 2508.16  1122.6 2513.41
#Mann= 6 ,-1,0
       0     .05       0     180     .07       0  324.01     .05       0
  464.01      .1       0   674.6    .045       0   688.3      .1       0
#XS Ineff= 2 , 0
           474.2 2488.45
Permanent Ineff=
       F       F
Bank Sta=674.6,688.3
XS Rating Curve= 0 ,0
Exp/Cntr(USF)=0,0
Exp/Cntr=0.3,0.1

Type RM Length L Ch R = 1 ,377     ,134.3,134.7,135.1
XS GIS Cut Line= 4
2175959.60617843408915.8227630112176018.57468262408626.290970513
2176253.24068166408344.4057824912176519.24828029408270.230551834
#Sta/Elev= 30
       0  2453.8    59.8 2455.06   161.9 2452.85     196  2453.3   239.5 2448.34
   292.5 2446.74   328.6 2447.72   395.8 2442.56   421.8 2445.36   487.7 2445.81
   491.8  2445.4   505.1 2440.08   525.9 2440.76   530.3 2438.46   534.42434.688
   536.3 2433.16   541.7 2432.22   556.12434.414   567.6 2436.65     578 2440.47
   601.3 2442.76   665.3 2442.67   702.7  2439.7   744.2 2444.72   802.3 2442.12
   819.9 2448.23   881.2 2474.59   889.5 2476.43   897.9 2482.66   938.4 2501.97
#Mann= 6 ,-1,0
       0     .05       0  325.48      .1       0  365.48     .05       0
  475.48      .1       0   534.4    .045       0   556.1      .1       0
#XS Ineff= 2 , 0
           340.1 2467.68
Permanent Ineff=
       F       F
Bank Sta=534.4,556.1
XS Rating Curve= 0 ,0
Exp/Cntr(USF)=0,0
Exp/Cntr=0.3,0.1

Type RM Length L Ch R = 1 ,243     ,223.9,236.5,239.2
XS GIS Cut Line= 4
2176257.22424883408635.9191410152176250.43610844408555.969931979
2176404.30062394408362.8850497792176483.49559516408337.240963862
#Sta/Elev= 30
       0 2482.37    26.8  2470.4    42.9 2461.73    46.9  2460.2      63 2455.75
      79 2453.36    89.4 2450.77   109.4 2441.69   117.6 2433.41   119.6  2432.5
   126.2 2432.34     135 2433.39   140.8 2436.21   165.6 2440.33   191.2 2441.27
     205 2440.54   211.7    2441   252.6 2440.34   259.9 2441.23   271.3 2444.29
   278.2 2444.94     314 2443.22   326.9 2444.05   335.4 2446.74   369.7 2461.83
   381.7 2468.54   395.1 2478.66   398.5 2480.03   406.9 2481.24   410.4 2483.28
#Mann= 3 ,-1,0
       0      .1       0   117.6    .045       0     135      .1       0
Bank Sta=117.6,135
XS Rating Curve= 0 ,0
Exp/Cntr(USF)=0,0
Exp/Cntr=0.3,0.1

Type RM Length L Ch R = 1 ,6       ,,,
XS GIS Cut Line= 4
2176340.55455868408652.4763950762176358.33225242408615.750069429
2176415.21785193408596.2147632162176474.09993035408609.944826049
#Sta/Elev= 30
       0  2510.8     8.2 2506.92    17.5  2500.6    25.9 2494.23    29.1  2490.4
    30.3 2488.09    35.1  2473.1    38.1 2468.88    40.8 2466.32    42.8 2465.67
      47 2461.94    51.2 2454.07    55.4 2441.45    59.7 2432.69    63.9 2431.84
    76.6 2432.45    80.8 2432.48    89.3 2436.44    94.6  2439.9   101.9 2442.42
     106 2445.15   114.3 2447.18   118.4  2450.3   126.6 2461.16   139.2 2467.02
     143 2469.42   151.2 2476.62   155.3 2483.71   159.4 2492.58   161.4 2495.45
#Mann= 3 ,-1,0
       0      .1       0    59.7    .045       0    76.6      .1       0
Bank Sta=59.7,76.6
XS Rating Curve= 0 ,0
Exp/Cntr(USF)=0,0
Exp/Cntr=0.3,0.1
LCMann Table=0

Chan Stop Cuts=-1
Use User Specified Reach Order=0
Composite Channel Slope=5